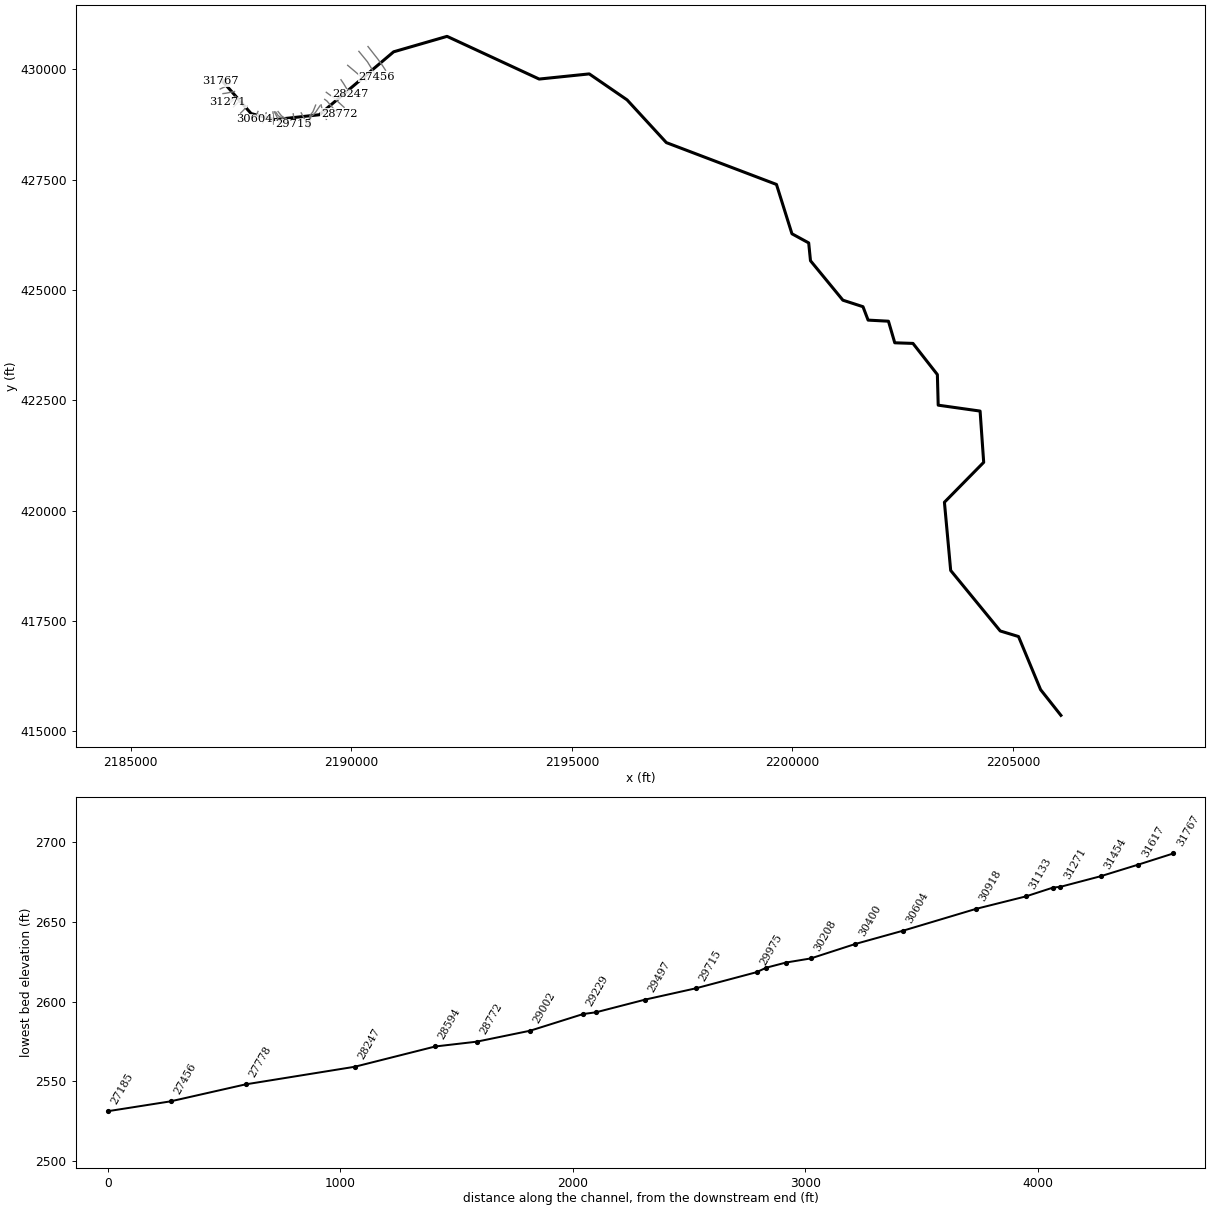
--- STMPNGCRK.prj (project) ---

Proj Title=STMPNGCRK
Current Plan=p01
Default Exp/Contr=0,0
English Units
Geom File=g01
Flow File=f01
Plan File=p01
Background Map Layer=Inundation Boundary (01pct Value_0)
Background Map Layer=Inundation Boundary (01pct Value_0)
BEGIN DESCRIPTION:
Stream Name: Stamping Creek
Flood Zone: Detailed from XS 122-27778 and Enhanced Approximate from 27778-31767
Pocahontas County, WV
HEC-RAS Version: RAS 6.1
Vertical Datum: NAVD88
Projection: NAD 1983 StatePlane West Virginia S FIPS 4702 (US Feet)
Terrain: 1-meter LIDAR (FEMA Region III 3DEP collected 2016-2018)
Land Use: 2016 NLCD
Hydrologic Method:
WV SIR2010-5033 regression equations
Model Notes:
channel burning applied at structure XS based on survey
Zone AE- 0-27778
Zone A- 27778-31767
END DESCRIPTION:
DSS File=dss
DSS Export Rating Curves= 0
DSS Export Rating Curve Sorted= 0
DSS Export Volume Flow Curves= 0
DXF OffsetX= 0
DXF OffsetY= 0
DXF ScaleX= 0
DXF ScaleY= 0

--- STMPNGCRK.p01 (plan) ---

Plan Title=Floodplain
Program Version=6.10
Short Identifier=Floodplain
Geom File=g01
Flow File=f01
Subcritical Flow
K Sum by GR= 0
Std Step Tol= 0.01
Critical Tol= 0.01
Num of Std Step Trials= 20
Max Error Tol= 0.3
Flow Tol Ratio= 0.001
Split Flow NTrial= 30
Split Flow Tol= 0.02
Split Flow Ratio= 0.02
Log Output Level= 0
Friction Slope Method= 1
Unsteady Friction Slope Method= 2
Unsteady Bridges Friction Slope Method= 1
Parabolic Critical Depth
Global Vel Dist= 0 , 0 , 0
Global Log Level= 0
CheckData=True
Encroach Param=-1 ,5,5, 2
Encroach River=STMPNGCRK
Encroach Reach=Main
Encroach Node=27778
       1   313.2   346.4
Encroach Node=27456
       1   424.3     459
Encroach Node=27185
       1   493.6   523.7
Encroach Node=26921
       1     430   464.2
Encroach Node=26683
       1     372   404.5
Encroach Node=26478
       1   191.5   240.6
Encroach Node=26144
       1   149.6   185.8
Encroach Node=25912
       1   141.3     194
Encroach Node=25560
       1   447.5   502.3
Encroach Node=25171
       1   408.2   444.4
Encroach Node=24804
       1   258.8     302
Encroach Node=24513
       1   175.5   212.5
Encroach Node=24257
       1   200.5   235.2
Encroach Node=24198
       1      94   134.3
Encroach Node=24059
       1   141.1   184.7
Encroach Node=23894
       1   167.4   199.5
Encroach Node=23753
       1   150.1   185.5
Encroach Node=23608
       1   155.6   211.9
Encroach Node=23308
       1     165     214
Encroach Node=23034
       1   210.7   248.2
Encroach Node=22795
       1     231   273.7
Encroach Node=22573
       1     223   262.9
Encroach Node=22337
       1   229.2   283.2
Encroach Node=22033
       1   141.3   173.9
Encroach Node=21793
       1    49.2    93.4
Encroach Node=21503
       1   127.5   168.1
Encroach Node=21388
       1     294     342
Encroach Node=21348
       1   292.2   335.8
Encroach Node=21238
       1   259.1   303.5
Encroach Node=21179
       1   258.8   296.3
Encroach Node=21158
       1   260.1   293.4
Encroach Node=21006
       1   259.7   293.7
Encroach Node=20788
       1     109     149
Encroach Node=20576
       1   163.3   215.6
Encroach Node=20232
       1   240.6   306.3
Encroach Node=19909
       1     266   310.8
Encroach Node=19673
       1    99.2     149
Encroach Node=19486
       1     191     251
Encroach Node=19252
       1   262.6     310
Encroach Node=18996
       1   208.2   248.2
Encroach Node=18723
       1     222   259.3
Encroach Node=18380
       1   231.7   278.6
Encroach Node=18134
       1   240.4     335
Encroach Node=17853
       1   236.3   279.5
Encroach Node=17588
       1     154   205.8
Encroach Node=17354
       1   120.4     174
Encroach Node=17110
       1   101.4   148.5
Encroach Node=16907
       1   107.5   151.8
Encroach Node=16700
       1   185.6   233.7
Encroach Node=16366
       1      82   137.5
Encroach Node=15906
       1   228.1   276.8
Encroach Node=15428
       1   371.3   450.6
Encroach Node=14964
       1   221.4     290
Encroach Node=14438
       1     335   408.2
Encroach Node=14006
       1     270     326
Encroach Node=13392
       1     275   395.6
Encroach Node=12915
       1     215   341.7
Encroach Node=12080
       1     433     564
Encroach Node=11685
       1     372     560
Encroach Node=11084
       1     252     401
Encroach Node=10549
       1    69.7     165
Encroach Node=9960
       1   179.8     260
Encroach Node=9563
       1     240     405
Encroach Node=9512
       1     280     435
Encroach Node=9230
       1     230   331.5
Encroach Node=9048
       1     250     321
Encroach Node=8888
       1     320   384.5
Encroach Node=8787
       1     326   406.5
Encroach Node=8683
       1     238   338.3
Encroach Node=8604
       1     170     300
Encroach Node=8573
       1     170  304.15
Encroach Node=8412
       1   91.75     195
Encroach Node=8271
       1   124.9     205
Encroach Node=8122
       1   120.1     215
Encroach Node=8099
       1     115     215
Encroach Node=7957
       1  120.57     230
Encroach Node=7820
       1     173   280.6
Encroach Node=7620
       1     148     304
Encroach Node=7579
       1     106     303
Encroach Node=7432
       1     120  342.13
Encroach Node=7207
       1    85.7     290
Encroach Node=6950
       1    39.5     220
Encroach Node=6895
       1      38     166
Encroach Node=6746
       1    72.8     150
Encroach Node=6326
       1  173.12     249
Encroach Node=5722
       1     296     375
Encroach Node=5228
       1   289.4   341.5
Encroach Node=4461
       1     275     498
Encroach Node=3808
       1     340     496
Encroach Node=3417
       1     400     520
Encroach Node=3226
       1     340     457
Encroach Node=2715
       1     360     565
Encroach Node=2005
       1   120.9     320
Encroach Node=1460
       1      83     227
Encroach Node=810
       1     108     227
Encroach Node=305
       1   287.5     370
Encroach Node=241
       1   282.2     380
Encroach Node=240
       1   246.6     353
Encroach Node=209
       1     230     336
Encroach Node=165
       1   249.3     365
Computation Interval=0.1SEC
Output Interval=1SEC
Instantaneous Interval=Max Profile
Mapping Interval=1HOUR
Computation Time Step Use Courant=        0
Computation Time Step Use Time Series=    0
Computation Time Step Count To Double=0
Computation Time Step Max Doubling=0
Computation Time Step Max Halving=0
Computation Time Step Residence Courant=0
Run HTab= 0
Run UNet= 0
Run Sediment= 0
Run PostProcess= 0
Run WQNet= 0
Run RASMapper=-1
UNET Theta= 0
UNET Theta Warmup= 0
UNET ZTol= 0
UNET ZSATol= 0
UNET MxIter= 0
UNET Max Iter WO Improvement= 0
UNET MaxInSteps= 0
UNET DtIC= 0
UNET DtMin= 0
UNET MaxCRTS= 0
UNET WFStab= 0
UNET SFStab= 0
UNET WFX= 1
UNET SFX= 1
UNET Gravity=32.174
UNET 1D Methodology=Finite Difference
UNET DSS MLevel= 1
UNET Pardiso=0
UNET DZMax Abort= 0
UNET Use Existing IB Tables= 0
UNET Froude Reduction=False
UNET Froude Limit= 0
UNET Froude Power= 0
UNET D1 Cores= 0
UNET WindReference=Eulerian
UNET WindDragFormulation=Hsu (1988)
UNET D2 Coriolis=0
UNET D2 Cores= 0
UNET D2 Theta= 1
UNET D2 Theta Warmup= 1
UNET D2 Z Tol= 0.01
UNET D2 Volume Tol= 0.01
UNET D2 Max Iterations= 20
UNET D2 Equation= 0
UNET D2 RampUpFraction=0.1
UNET D2 TimeSlices= 1
UNET D2 Turbulence Formulation=Non-Conservative (original)
UNET D2 Eddy Viscosity=0.3
UNET D2 Transverse Eddy Viscosity=0.1
UNET D2 Smagorinsky Mixing=0
UNET D2 BCVolumeCheck=0
UNET D2 Cores=0
UNET D2 SolverType=PARDISO (Direct)
UNET D2 Minimum Iterations= 2147483647
UNET D2 Maximum Iterations= 2147483647
UNET D2 Restart Number= 10
UNET D2 Relaxation Coeff=1.3
UNET D2 SOR Precondition Iterations= 10
UNET D2 ILUT Maximum Fill= 8
UNET D2 ILUT Tolerance=1E-08
UNET D1D2 MaxIter= 0
UNET D1D2 ZTol=0.01
UNET D1D2 QTol=0.1
UNET D1D2 MinQTol=1
DSS File=dss
Write IC File= 0
Write IC File at Fixed DateTime=0
Write IC File at Sim End=0
Echo Input=False
Echo Parameters=False
Echo Output=False
Write Detailed= 0
HDF Write Warmup=0
HDF Write Time Slices=0
HDF Flush=0
HDF Compression= 1
HDF Chunk Size= 1
HDF Spatial Parts= 1
HDF Use Max Rows=0
HDF Fixed Rows= 1
Calibration Method= 0
Calibration Iterations= 20
Calibration Max Change=0.05
Calibration Tolerance=0.2
Calibration Maximum=1.5
Calibration Minimum=0.5
Calibration Optimization Method= 1
WQ AD Non Conservative
WQ ULTIMATE=-1
WQ Max Comp Step=1HOUR
WQ Output Interval=15MIN
WQ Output Selected Increments= 0
WQ Output face flow=0
WQ Output face velocity=0
WQ Output face area=0
WQ Output face dispersion=0
WQ Output cell volume=0
WQ Output cell surface area=0
WQ Output cell continuity=0
WQ Output cumulative cell continuity=0
WQ Output face conc=0
WQ Output face dconc_dx=0
WQ Output face courant=0
WQ Output face peclet=0
WQ Output face adv mass=0
WQ Output face disp mass=0
WQ Output cell mass=0
WQ Output cell source sink temp=0
WQ Output nsm pathways=0
WQ Output nsm derived pathways=0
WQ Create Restart=0
WQ Fixed Restart=0
WQ System Summary=0
WQ Write To DSS=0
Sorting and Armoring Iterations= 10
XS Update Threshold= 0.02
Bed Roughness Predictor= 0
Hydraulics Update Threshold= 0.02
Energy Slope Method= 1
Volume Change Method= 1
Sediment Retention Method= 0
Sediment TS Multiplier= 1
Warm Up Method= 0
XS Weighting Method= 0
Number of US Weighted Cross Sections= 1
Number of DS Weighted Cross Sections= 1
Upstream XS Weight=0
Main XS Weight=1
Downstream XS Weight=0
Number of DS XS's Weighted with US Boundary= 1
Upstream Boundary Weight= 1
Weight of XSs Associated with US Boundary= 0
Number of US XS's Weighted with DS Boundary= 1
Downstream Boundary Weight= 0.5
Weight of XSs Associated with DS Boundary= 0.5
Percentile Method= 0
Sediment Output Level= 3
Mass or Volume Output= 0
Output Increment Type= 1
Profile and TS Output Increment= 1
Transport Output Increment 1
XS Output Flag= 0
XS Output Increment= 10
Read HDF5 Sediment Hotstart= 0
Sediment Hotstart Type= 0
Write Gradation File= 0
Read Gradation Hotstart= 0
Write HDF5 File= 1
Write Binary Output= 1
Write DSS Sediment File= 0
DSS Sediment Output Type= 1
SV Curve= 0
Specific Gage Flag= 0
Subcell Erosion Methods= 0
Subcell Deposition Methods= 0
Advection Scheme= 1
Matrix Solver= 0
Implicit Weighting Factor= 1
Maximum Outer Loop Convergence Iterations= 5
Convergence Maximum Absolute= 0.001
Convergence RMSE= 0.0001
Grain Fractions Max Abs Error= 0.001
Max Subgrid Regions= 1
Max Subgrid Length Scale= 3.402823E+38
Initial Layer Thickness= 3.402823E+38
Min Layer Thickness= 3.402823E+38
Max Layer Thickness= 3.402823E+38
Number of Layers= 5

--- STMPNGCRK.f01 (steady flow) ---

Flow Title=Flow
Program Version=6.10
Number of Profiles= 7
Profile Names=01pct,FW,10pct,04pct,02pct,0_2pct,01plus
River Rch & RM=STMPNGCRK,Main            ,31767
     600     600     318     422     508     838     888
River Rch & RM=STMPNGCRK,Main            ,29497
     719     719     383     507     609     999    1060
River Rch & RM=STMPNGCRK,Main            ,26683
     821     821     440     581     697    1140    1210
River Rch & RM=STMPNGCRK,Main            ,24198
    1220    1220     661     867    1040    1670    1800
River Rch & RM=STMPNGCRK,Main            ,23608
    1360    1360     743     972    1160    1870    2010
River Rch & RM=STMPNGCRK,Main            ,19486
    1560    1560     856    1120    1330    2140    2300
River Rch & RM=STMPNGCRK,Main            ,17110
    1740    1740     960    1250    1490    2380    2570
River Rch & RM=STMPNGCRK,Main            ,16366
    1960    1960    1090    1410    1680    2680    2900
River Rch & RM=STMPNGCRK,Main            ,11084
    2780    2780    1560    2010    2380    3760    4110
Boundary for River Rch & Prof#=STMPNGCRK,Main            , 1
Up Type= 0
Dn Type= 3
Dn Slope=0.012409
Boundary for River Rch & Prof#=STMPNGCRK,Main            , 2
Up Type= 0
Dn Type= 3
Dn Slope=0.012409
Boundary for River Rch & Prof#=STMPNGCRK,Main            , 3
Up Type= 0
Dn Type= 3
Dn Slope=0.012409
Boundary for River Rch & Prof#=STMPNGCRK,Main            , 4
Up Type= 0
Dn Type= 3
Dn Slope=0.012409
Boundary for River Rch & Prof#=STMPNGCRK,Main            , 5
Up Type= 0
Dn Type= 3
Dn Slope=0.012409
Boundary for River Rch & Prof#=STMPNGCRK,Main            , 6
Up Type= 0
Dn Type= 3
Dn Slope=0.012409
DSS Import GetInterval= 0
DSS Import GetPeak= 0
DSS Import FillOption= 0

--- STMPNGCRK.g01 (geometry) ---

Geom Title=Geometry
Program Version=6.10

River Reach=STMPNGCRK       ,Main
Reach XY= 30
2187061.89650925429752.564038778      2187727.98      428999.939
      2188266.53      428863.393     2189273.029      428973.983
     2190958.091       430400.74     2192168.763      430751.126
     2194257.151      429783.054      2195393.38      429899.883
     2196250.227       429311.13     2197140.702       428342.33
     2199637.207      427393.912     2199987.976      426275.628
     2200367.693      426068.365     2200408.489      425664.325
     2201143.032      424769.904     2201598.491      424622.207
     2201714.503      424318.132     2202175.825      424293.269
     2202319.074      423803.999     2202731.721      423789.946
     2203284.876      423083.549     2203303.837      422389.981
     2204253.478      422255.875     2204335.043      421093.912
     2203444.882      420188.857     2203586.913      418642.554
     2204710.349      417270.762     2205124.606      417144.653
     2205624.592      415941.169      2206085.85      415357.711

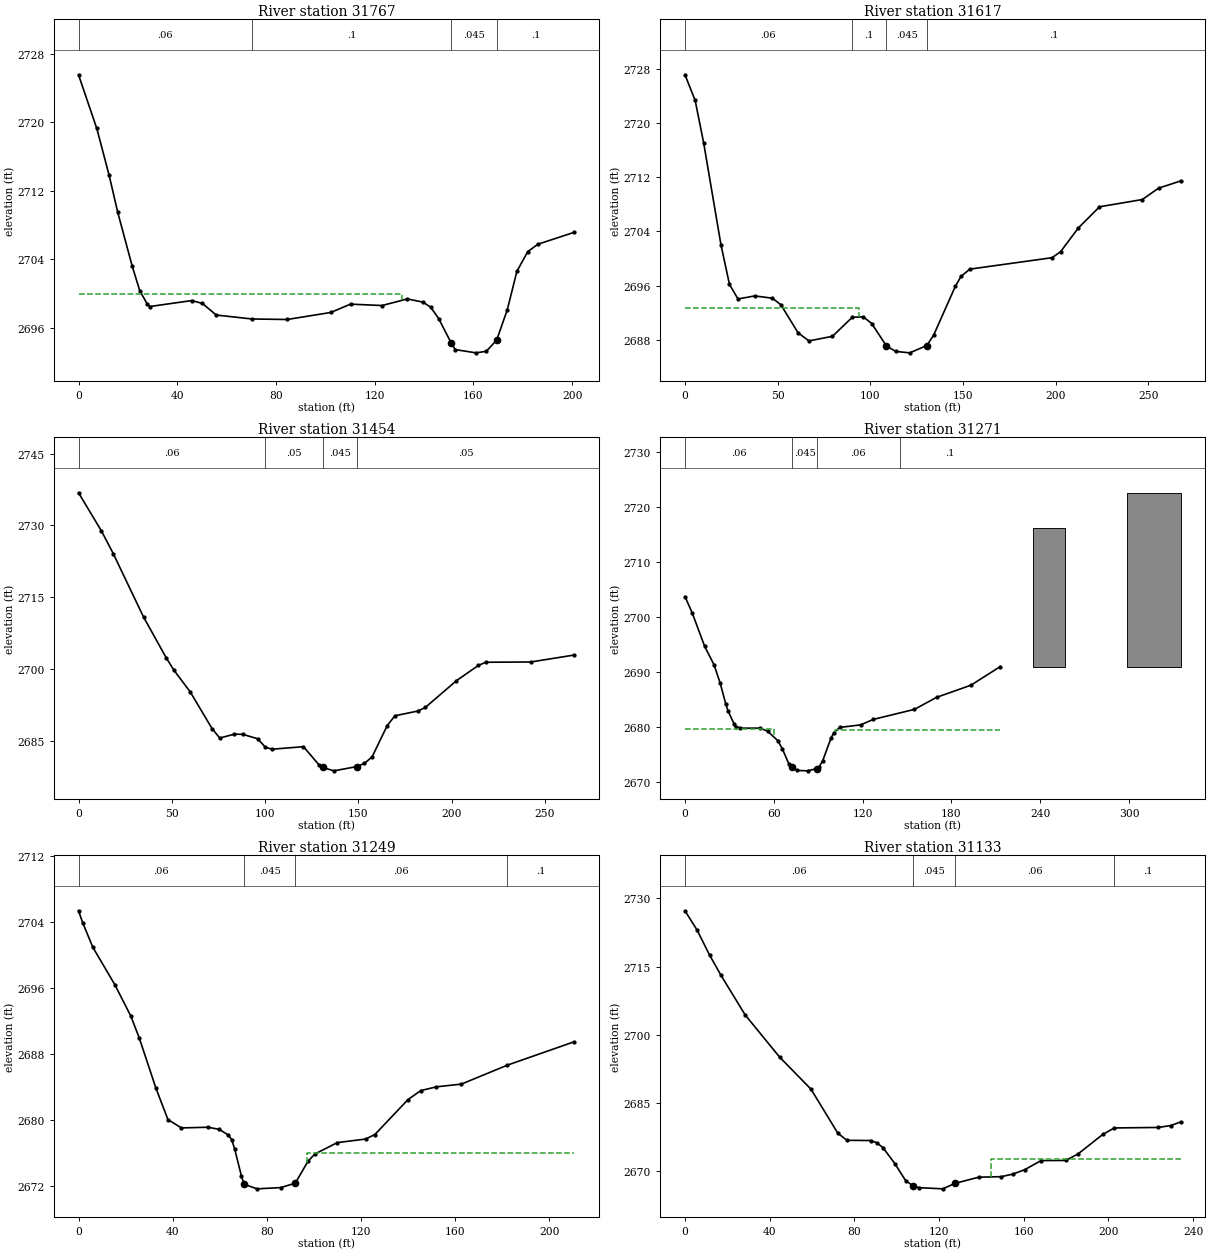
Type RM Length L Ch R = 1 ,31767   ,150.3,150.3,150.3
XS GIS Cut Line= 4
 2187215.0419357429798.3274823122187090.04577222429750.456611194
2187044.83439394429735.8294005742187025.55307085429733.169907734
#Sta/Elev= 30
       0 2725.54     7.4 2719.28    12.4 2713.82    15.9 2709.48    21.7 2703.27
    24.8 2700.36    27.9 2698.76    28.8  2698.5    45.9  2699.2    50.2 2698.86
    55.8 2697.51    70.3 2697.05    84.5 2696.99   102.2 2697.81   110.2 2698.78
     123 2698.62   133.2 2699.39   139.5 2699.02   142.7 2698.42   145.9  2697.1
     151 2694.24   152.6 2693.48     161  2693.1   165.2 2693.28   169.4 2694.58
   173.7 2698.12   177.6 2702.61     182 2704.91   186.1 2705.77   200.8 2707.16
#Mann= 4 ,-1,0
       0     .06       0    70.3      .1       0     151    .045       0
   169.4      .1       0
#XS Ineff= 2 , 0
          130.91 2699.97
Permanent Ineff=
       F       F
Bank Sta=151,169.4
XS Rating Curve= 0 ,0
Exp/Cntr(USF)=0,0
Exp/Cntr=0.3,0.1

Type RM Length L Ch R = 1 ,31617   ,167.6,163,157.9
XS GIS Cut Line= 3
2187260.91818719429683.9692901952187125.28405235429604.849378207
2187025.41594914429557.506258589
#Sta/Elev= 30
       0 2727.12     5.5 2723.33    10.1 2717.04    19.4 2702.06      24  2696.2
    28.6 2694.04    37.7 2694.49    47.2 2694.15    51.8 2693.17      61 2689.06
    66.9 2687.85    79.6 2688.53    90.3 2691.34    96.2 2691.41   100.8 2690.41
   108.7 2687.11   113.7  2686.3   121.3 2686.09   130.5 2687.17   134.2  2688.7
   145.9  2695.9     149 2697.37   153.7 2698.44   198.1 2700.13   202.7 2701.01
   212.3 2704.52   223.7 2707.64   246.8 2708.71   255.6 2710.39   267.5 2711.45
#Mann= 4 ,-1,0
       0     .06       0      90      .1       0   108.7    .045       0
   130.5      .1       0
#XS Ineff= 2 , 0
           93.73 2692.76
Permanent Ineff=
       F       F
Bank Sta=108.7,130.5
XS Rating Curve= 0 ,0
Exp/Cntr(USF)=0,0
Exp/Cntr=0.3,0.1

Type RM Length L Ch R = 1 ,31454   ,167.8,172.6,179.4
XS GIS Cut Line= 3
2187350.37759636429501.4374562462187160.39935196429462.823991937
2187089.16523301429453.340525102
#Sta/Elev= 30
       0 2736.82    12.3 2728.84    18.6 2724.13    34.9 2710.84    47.1 2702.29
    51.2 2699.73    59.8 2695.28    71.6 2687.56    75.7 2685.59    83.5  2686.4
      88 2686.37    96.1 2685.43   100.2 2683.65   103.9 2683.26   120.6 2683.79
   128.8 2680.04     131 2679.44   136.9 2678.74   149.2 2679.63   153.3 2680.29
   157.4 2681.68   165.5  2688.2   169.6 2690.24   181.9 2691.23   185.9 2691.98
   202.6 2697.57   214.3 2700.75   218.3 2701.42   242.5 2701.48   265.7 2702.93
#Mann= 4 ,-1,0
       0     .06       0     100     .05       0     131    .045       0
   149.2     .05       0
Bank Sta=131,149.2
XS Rating Curve= 0 ,0
Exp/Cntr(USF)=0,0
Exp/Cntr=0.5,0.3

Type RM Length L Ch R = 1 ,31271   ,29.4,31.7,34.4
XS GIS Cut Line= 5
2187365.83519103429390.2870746942187327.60907627 429355.91079885
2187292.60909759429329.8523318662187214.84675743 429273.02107522
2187197.30471883429260.302599725
#Sta/Elev= 30
       0 2703.72     4.8  2700.8    13.3 2694.68    19.6 2691.36    23.8    2688
    27.5 2684.27    29.1 2682.96    33.1 2680.65    34.5 2680.13    37.5 2679.84
    50.6 2679.85    55.8  2679.3    62.7 2677.57    65.7 2676.13    70.1  2673.4
    72.6 2672.72    75.8 2672.17    82.8  2672.1      892672.516    90.6 2672.81
      93 2673.92    98.7 2678.08   100.5 2678.97   104.4 2679.97   118.7 2680.44
   127.3 2681.44     155 2683.25   169.9 2685.43   193.2 2687.64     213 2691.02
#Mann= 4 ,-1,0
       0     .06       0    72.6    .045       0      89     .06       0
  145.05      .1       0
#XS Ineff= 2 , 0
              60 2679.67     101         2679.49
Permanent Ineff=
       F       F
#Block Obstruct= 2 ,-1
  235.39  256.84 2716.16   298.5  334.79 2722.54
Bank Sta=72.6,89
XS Rating Curve= 0 ,0
Exp/Cntr(USF)=0,0
Exp/Cntr=0.5,0.3

Type RM Length L Ch R = 1 ,31249   ,117,116.3,116.5
XS GIS Cut Line= 3
2187381.34889926429377.7283585052187320.03281434429309.024793474
2187231.42030525429230.304411666
#Sta/Elev= 30
       0  2705.4     1.8 2703.93     6.1 2700.96    15.4 2696.44    22.2 2692.63
    25.8 2689.96    32.9 2683.85      38 2680.04    43.7 2679.03      55 2679.11
    59.7 2678.86    63.5  2678.2    65.1  2677.6    66.4 2676.42    69.2  2673.2
    70.4 2672.19    75.8 2671.63    85.9 2671.78    92.1 2672.32    97.5 2674.97
   100.4 2675.85   109.9 2677.24     122 2677.68   125.9 2678.22     140 2682.47
   145.4 2683.56   152.1 2684.02   162.7 2684.35   182.2 2686.65   210.6 2689.49
#Mann= 4 ,-1,0
       0     .06       0    70.4    .045       0    92.1     .06       0
   182.2      .1       0
#XS Ineff= 2 , 0
              65    2676      97            2676
Permanent Ineff=
       F       F
#Block Obstruct= 2 , 0
                          305.42         2722.17
Bank Sta=70.4,92.1
XS Rating Curve= 0 ,0
Exp/Cntr(USF)=0,0
Exp/Cntr=0.5,0.3

Type RM Length L Ch R = 1 ,31133   ,213.2,215.1,216.8
XS GIS Cut Line= 3
 2187487.8415293429317.6373661352187350.37759636429172.450740333
2187324.35586826429150.309243507
#Sta/Elev= 30
       0 2727.29     5.7 2723.06    11.6 2717.56      17 2713.09    28.4 2704.39
    44.7 2695.09    59.5 2688.04    72.2 2678.34    76.5 2676.78    87.8 2676.73
    90.6 2676.24    93.5 2675.17    99.1 2671.67   104.2 2667.92   107.6 2666.81
   110.4 2666.36   121.8  2666.1   127.5  2667.3   138.7 2668.66   149.4 2668.78
   154.9 2669.35   160.4  2670.3   168.2 2672.32   179.9 2672.35   185.7  2673.8
   197.3 2678.06   202.8  2679.5   223.5 2679.61   229.4 2680.02   234.1 2680.82
#Mann= 4 ,-1,0
       0     .06       0   107.6    .045       0   127.5     .06       0
   202.8      .1       0
#XS Ineff= 2 , 0
                          144.66         2672.58
Permanent Ineff=
       F       F
Bank Sta=107.6,127.5
XS Rating Curve= 0 ,0
Exp/Cntr(USF)=0,0
Exp/Cntr=0.3,0.1

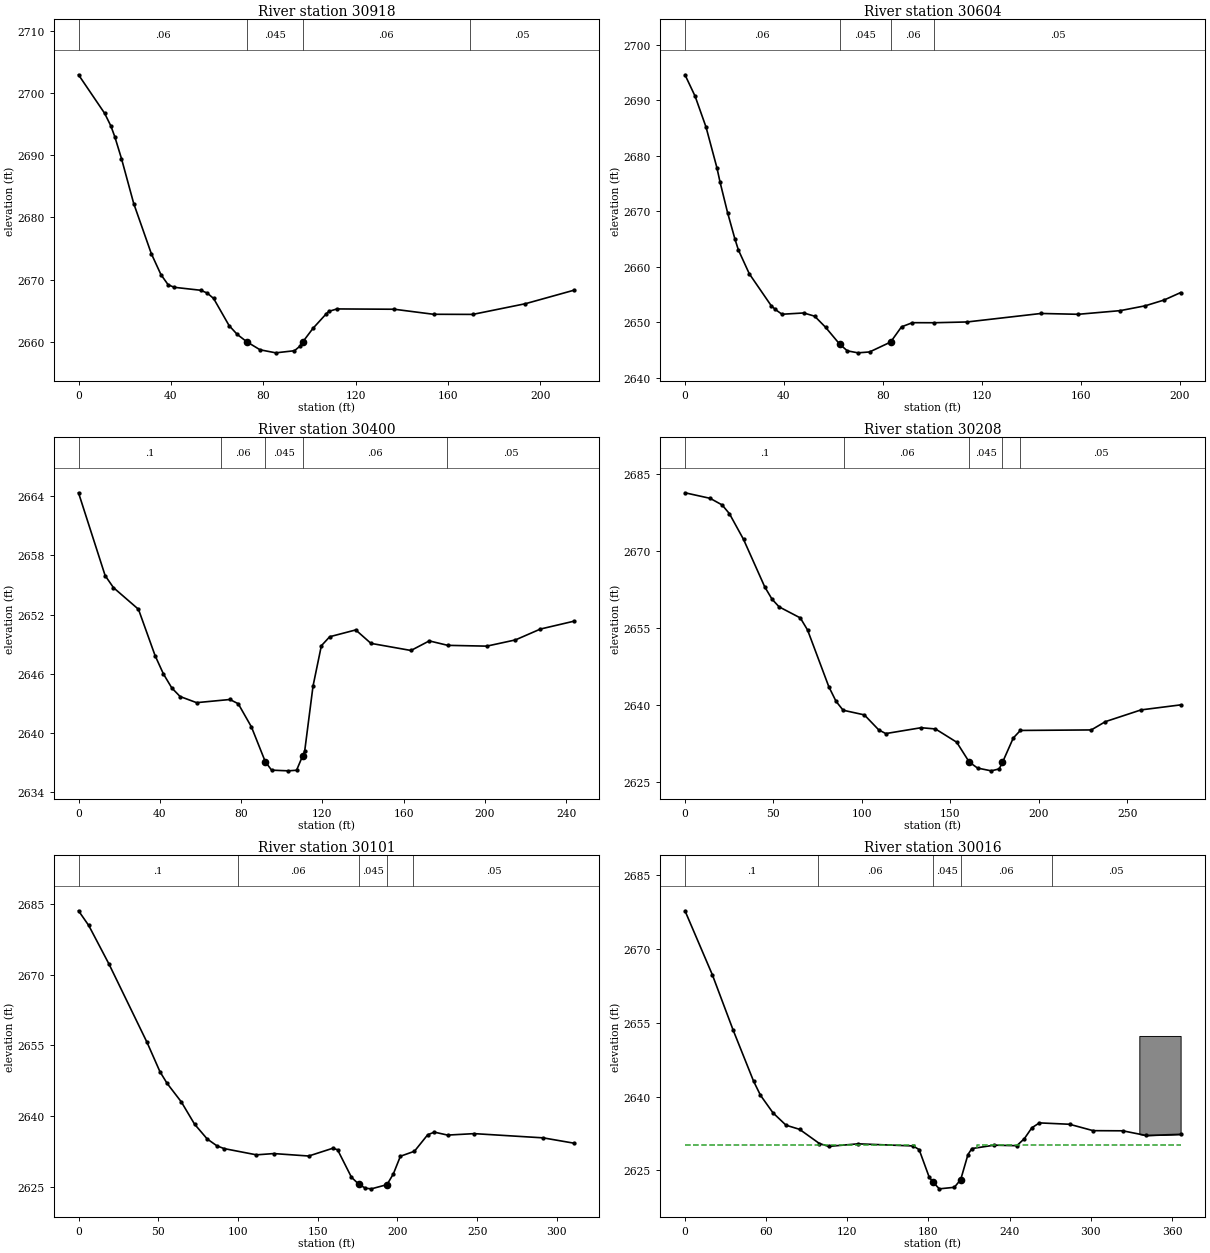
Type RM Length L Ch R = 1 ,30918   ,308.8,313.8,316
XS GIS Cut Line= 3
2187626.85000082429172.4507403332187561.97938078429084.412041708
 2187487.2872034429010.317699228
#Sta/Elev= 30
       0 2702.94    11.3 2696.75      14 2694.72    15.7 2692.99    18.6 2689.47
    23.9 2682.24    31.5  2674.2    35.7  2670.8    38.8 2669.18    41.4 2668.77
    52.9 2668.29    55.7 2667.85    58.5 2666.97    65.2 2662.61    68.7  2661.2
    72.9    2660    78.6 2658.72    85.4 2658.23    93.5 2658.57    95.8 2659.28
    97.2 2660.04   101.5 2662.16   107.2 2664.48   108.4  2664.9   111.9 2665.29
   136.7 2665.24   153.7 2664.43   170.7 2664.41   193.5 2666.13   214.6 2668.31
#Mann= 4 ,-1,0
       0     .06       0    72.9    .045       0    97.2     .06       0
  169.36     .05       0
Bank Sta=72.9,97.2
XS Rating Curve= 0 ,0
Exp/Cntr(USF)=0,0
Exp/Cntr=0.3,0.1

Type RM Length L Ch R = 1 ,30604   ,201.7,204.6,207.9
XS GIS Cut Line= 3
2187883.24340383429048.8876545442187846.17447809428967.027110208
2187799.17474541428867.058257586
#Sta/Elev= 30
       0 2694.58     4.1 2690.71     8.5 2685.17    12.9 2677.85    14.2  2675.2
    17.2 2669.78    20.2 2664.98    21.6 2663.02      26 2658.74    34.8 2653.03
    36.5 2652.32    39.2 2651.46      48 2651.69    52.4 2651.11    56.8 2649.12
    62.5 2646.08    65.6 2644.87    69.9 2644.51    74.6 2644.67    83.1 2646.45
    87.5 2649.19    91.9 2649.94   100.7 2649.93     114 2650.07   143.9  2651.6
   158.9 2651.45   175.9 2652.11     186 2652.98   193.6 2654.02   200.3 2655.36
#Mann= 4 ,-1,0
       0     .06       0    62.5    .045       0    83.1     .06       0
   100.7     .05       0
Bank Sta=62.5,83.1
XS Rating Curve= 0 ,0
Exp/Cntr(USF)=0,0
Exp/Cntr=0.3,0.1

Type RM Length L Ch R = 1 ,30400   ,189.5,192,194.5
XS GIS Cut Line= 3
2188068.58803251429017.9968830962188040.78633821 428889.80018159
2187988.06961989428790.156391691
#Sta/Elev= 30
       0 2664.33    13.1 2655.95    17.2 2654.73    29.5 2652.54    37.7 2647.84
    41.8 2645.99    45.9 2644.58      50 2643.71    58.1 2643.09    74.5 2643.41
    78.6 2642.98    85.1 2640.63    91.9 2637.12      95 2636.26   103.2 2636.19
   107.3 2636.25   110.3 2637.71   111.3 2638.19   115.4 2644.77   119.5 2648.85
   123.6 2649.76   136.4 2650.45   143.9 2649.09   163.6 2648.37   172.6 2649.34
   181.7 2648.89   200.9 2648.81     215 2649.44   227.3 2650.54   243.9 2651.34
#Mann= 5 ,-1,0
       0      .1       0      70     .06       0    91.9    .045       0
   110.3     .06       0  181.18     .05       0
Bank Sta=91.9,110.3
XS Rating Curve= 0 ,0
Exp/Cntr(USF)=0,0
Exp/Cntr=0.3,0.1

Type RM Length L Ch R = 1 ,30208   ,100.9,106.4,113.4
XS GIS Cut Line= 4
2188221.49735118429038.0758845372188233.85365976428919.146414465
2188230.76458261428843.4640244192188224.74817804428758.798349287
#Sta/Elev= 30
       0 2681.26    14.2 2680.18      21 2678.89    25.1  2677.2    33.1 2672.18
    45.1 2662.92    49.2 2660.54    53.2 2659.04    65.2 2656.88    69.3 2654.53
    81.3 2643.49    85.4 2640.63    89.4  2638.9   101.4 2637.99   109.5 2635.08
   113.5 2634.35   133.5 2635.49   141.6 2635.25   153.6 2632.67   160.7  2628.8
   165.4 2627.63   173.1 2627.09   177.6 2627.46  179.48 2628.73   185.6 2633.49
   189.6 2634.96   229.7 2635.06   237.7 2636.68   257.8 2638.96   280.2 2639.94
#Mann= 5 ,-1,0
       0      .1       0      90     .06       0   160.7    .045       0
  179.48     .06       0  189.57     .05       0
Bank Sta=160.7,179.48
XS Rating Curve= 0 ,0
Exp/Cntr(USF)=0,0
Exp/Cntr=0.3,0.1

Type RM Length L Ch R = 1 ,30101   ,78.5,85.2,96.2
XS GIS Cut Line= 4
2188256.27748372429038.9059242832188323.03634393428904.532321035
2188347.85694581428848.8999375252188376.10107897428753.041061323
#Sta/Elev= 30
       0 2683.64     6.4 2680.52    19.1 2672.32      43 2655.64    51.1 2649.41
    55.5 2646.97    64.5 2642.99    72.8 2638.26    80.7 2635.12    86.8 2633.66
    91.3 2633.07   111.6 2631.74   122.5 2632.01   144.4 2631.49   159.5 2633.14
   162.5 2632.82   171.2 2626.98   175.8 2625.49     180 2624.64   183.7 2624.51
   193.52625.404   197.5  2627.7   201.9 2631.44   210.7  2632.5     219    2636
   223.2 2636.57   231.5 2635.94   248.2 2636.25   291.5 2635.35   310.9 2634.21
#Mann= 5 ,-1,0
       0      .1       0     100     .06       0   175.8    .045       0
   193.5     .06       0  210.04     .05       0
Bank Sta=175.8,193.5
XS Rating Curve= 0 ,0
Exp/Cntr(USF)=0,0
Exp/Cntr=0.5,0.3

Type RM Length L Ch R = 1 ,30016   ,41.1,41,39
XS GIS Cut Line= 5
 2188285.0623597429035.4550133942188339.27566359428953.440015201
2188439.36176308428889.4961183062188476.89405039428850.573746282
2188529.71726956 428771.33891752
#Sta/Elev= 30
       0 2677.79    20.2  2664.8    35.6 2653.53    50.7 2643.15    55.8 2640.28
    65.1 2636.69    74.7 2634.19    84.7 2633.35    99.4 2630.46   106.2 2629.88
   127.9  2630.4   168.7 2629.97   173.1 2629.22   180.5 2623.65   183.1  2622.7
     188 2621.25   199.1 2621.56   203.8 2623.11   209.2 2628.23   212.1 2629.44
   228.6 2630.13   245.3 2630.02   250.9 2631.46   256.4 2633.66     262 2634.66
   284.3 2634.38   301.7 2633.08   323.6 2633.05   340.9  2632.1   366.4 2632.33
#Mann= 5 ,-1,0
       0      .1       0   98.31     .06       0   183.1    .045       0
   203.8     .06       0  271.15     .05       0
#XS Ineff= 2 , 0
             170 2630.25     216         2630.16
Permanent Ineff=
       F       F
#Block Obstruct= 1 ,-1
  335.87  366.38 2652.34
Bank Sta=183.1,203.8
XS Rating Curve= 0 ,0
Exp/Cntr(USF)=0,0
Exp/Cntr=0.5,0.3

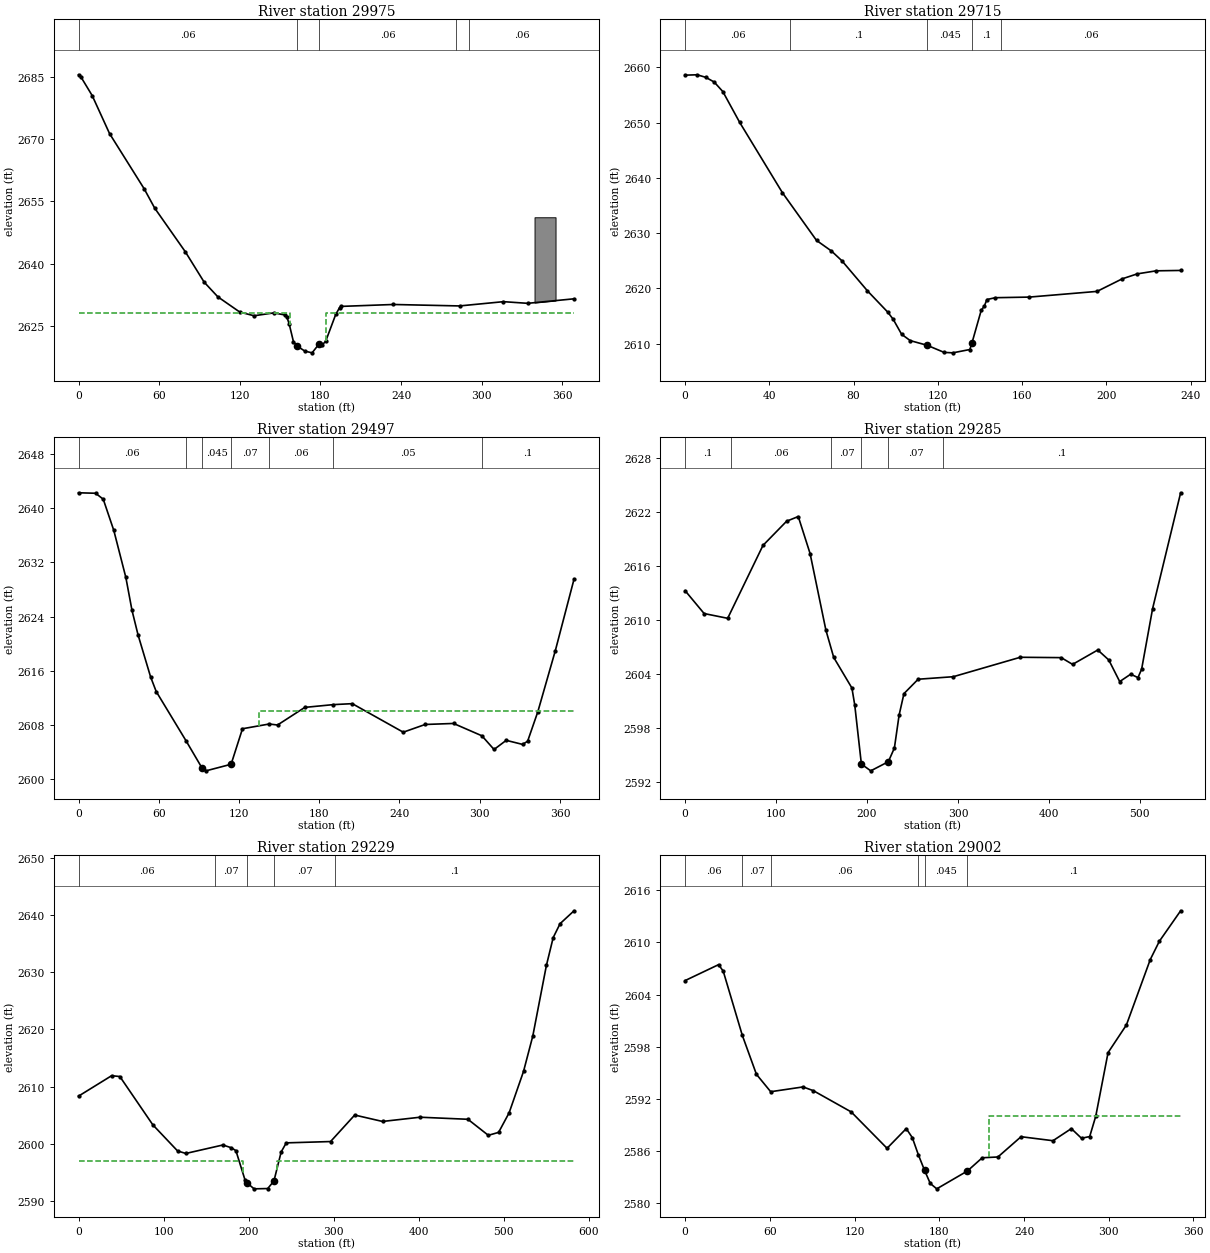
Type RM Length L Ch R = 1 ,29975   ,267.8,259.9,249
XS GIS Cut Line= 5
2188337.88557888429046.5756911152188415.73032292428947.879676341
2188474.11388096428908.9573043182188522.76684599428883.935779445
2188575.59006516428778.289341096
#Sta/Elev= 30
       0 2685.57     1.8 2685.05    10.2 2680.54    23.1 2671.38    48.9 2658.03
    56.7 2653.38    79.5 2642.84    93.5 2635.52   103.7 2631.97     120  2628.3
   130.6 2627.41   145.3  2628.1   153.9 2627.58   155.1 2627.06   156.8 2625.37
   159.9 2621.19   162.6 2620.12   168.4 2618.88   173.8 2618.46   179.1 2620.64
     181 2620.29   183.9 2621.24   191.4 2627.74   194.3  2629.4   195.5 2629.67
   234.2 2630.13   283.5 2629.78   316.2 2630.81   334.2 2630.41   368.7  2631.5
#Mann= 5 ,-1,0
       0     .06       0   162.6    .045       0   179.1     .06       0
  280.58      .1       0  290.58     .06       0
#XS Ineff= 2 , 0
             157    2628     184            2628
Permanent Ineff=
       F       F
#Block Obstruct= 1 ,-1
   339.3  354.94 2651.18
Bank Sta=162.6,179.1
XS Rating Curve= 0 ,0
Exp/Cntr(USF)=0,0
Exp/Cntr=0.5,0.3

Type RM Length L Ch R = 1 ,29715   ,213,218.6,223.7
XS GIS Cut Line= 3
2188681.76984574428994.8288045112188704.93792433428841.919485847
2188697.21523146428761.603480084
#Sta/Elev= 30
       0 2658.57     5.7 2658.64     9.8 2658.18    13.8 2657.33    17.9 2655.61
    25.9 2650.04    46.2 2637.32    62.4 2628.69    69.5 2626.77    74.5 2624.99
    86.6 2619.56    96.2 2615.73    98.8 2614.43   102.8 2611.72   106.9 2610.57
   114.9 2609.73     123 2608.44   127.1 2608.36   135.2 2608.96  136.262610.215
   140.6 2616.04   142.1 2616.83   143.3    2618   147.3 2618.33   163.4 2618.44
   195.6 2619.47   207.6 2621.75   214.7 2622.64   223.7 2623.19   235.3 2623.26
#Mann= 5 ,-1,0
       0     .06       0      50      .1       0   114.9    .045       0
  136.26      .1       0     150     .06       0
Bank Sta=114.9,136.26
XS Rating Curve= 0 ,0
Exp/Cntr(USF)=0,0
Exp/Cntr=0.3,0.1

Type RM Length L Ch R = 1 ,29497   ,227.1,211.2,182.1
XS GIS Cut Line= 3
2188862.48085871429016.4523445242188961.33132734 428831.10771584
2189026.20194738428684.376551466
#Sta/Elev= 30
       0 2642.26    12.8 2642.19    18.5 2641.31    26.4  2636.7    35.4 2629.77
      40 2624.91    44.5 2621.31    53.9  2615.1    58.1 2612.94    80.5 2605.64
    92.4 2601.64    95.3 2601.24   114.1 2602.21   122.6 2607.45   142.6 2608.15
   148.8    2608   169.2  2610.6   190.6 2611.01   204.7 2611.15   242.8 2606.94
   259.2 2608.08   280.4 2608.23   301.6 2606.41   310.7 2604.39   319.8 2605.74
     332 2605.14   335.8 2605.61   343.4 2609.94   356.5 2618.96   370.5 2629.52
#Mann= 7 ,-1,0
       0     .06       0    80.5     .07       0    92.4    .045       0
   114.1     .07       0   142.6     .06       0   190.6     .05       0
   301.6      .1       0
#XS Ineff= 2 , 0
                             135            2610
Permanent Ineff=
       F       F
Bank Sta=92.4,114.1
XS Rating Curve= 0 ,0
Exp/Cntr(USF)=0,0
Exp/Cntr=0.5,0.3

Type RM Length L Ch R = 1 ,29285   ,64.1,56.3,66.6
XS GIS Cut Line= 6
2189190.00750925429192.5345862032189137.18429007429061.866622981
2189126.06361235429036.8450981092189064.89988488428963.170608207
2189032.92793644428817.211713119  2189020.417174428686.543749898
#Sta/Elev= 30
       0 2613.29    20.9 2610.75    46.8 2610.22    85.6 2618.32   111.6 2621.01
   124.4 2621.53   137.4 2617.42   154.8  2608.9   163.4 2605.87   183.4 2602.47
   186.5 2600.59   193.8 2594.02   204.1 2593.27   223.4 2594.28   230.1 2595.81
   235.3 2599.48   240.6 2601.85   256.2 2603.45   294.8 2603.73   368.5 2605.89
   413.5 2605.85     426  2605.1   453.7  2606.7   465.8 2605.59   477.8 2603.19
   489.9 2604.01   497.9 2603.63   501.9 2604.56     514 2611.31   544.8 2624.17
#Mann= 6 ,-1,0
       0      .1       0      50     .06       0  160.94     .07       0
   193.8    .045       0   223.4     .07       0  284.08      .1       0
#XS Ineff= 2 , 0
             166 2602.84     250         2601.83
Permanent Ineff=
       F       F
Bank Sta=193.8,223.4
XS Rating Curve= 0 ,0
Exp/Cntr(USF)=0,0
Exp/Cntr=0.5,0.3

Type RM Length L Ch R = 1 ,29229   ,197.9,227.5,243
XS GIS Cut Line= 5
2189288.70352402429177.2436543362189188.61742453429031.284759248
2189145.52479836428982.6317942192189076.02056261428928.418490329
2189053.77920716428676.813156892
#Sta/Elev= 30
       0 2608.33    38.9  2611.9    48.6 2611.76    87.4 2603.32   116.5 2598.76
   126.2 2598.32   169.8  2599.8   179.8 2599.31   185.1 2598.81   195.8 2593.69
   198.6 2593.12   206.5 2592.14   222.5 2592.19   229.8 2593.51   238.3 2598.58
   244.3 2600.17   296.4  2600.4   324.8 2605.03   357.5 2603.91   401.6 2604.65
   457.9 2604.29   481.9 2601.49     494    2602   506.4 2605.43   523.3 2612.65
   534.2 2618.83   550.2 2631.16   558.2 2636.03   566.3 2638.46   582.7 2640.71
#Mann= 5 ,-1,0
       0     .06       0     160     .07       0   198.6    .045       0
   229.8     .07       0  301.97      .1       0
#XS Ineff= 2 , 0
             194    2597     233            2597
Permanent Ineff=
       F       F
Bank Sta=198.6,229.8
XS Rating Curve= 0 ,0
Exp/Cntr(USF)=0,0
Exp/Cntr=0.5,0.3

Type RM Length L Ch R = 1 ,29002   ,224,229.6,235.8
XS GIS Cut Line= 3
2189313.48612184429198.7078960632189333.56512328429107.580120293
2189432.41559191428869.721180149
#Sta/Elev= 30
       0  2605.6    23.7 2607.43      27 2606.68    40.5 2599.31    50.5 2594.83
    60.6 2592.83    83.5 2593.38    90.8 2592.95   117.6 2590.51     143 2586.33
   156.6 2588.59   160.9 2587.55   165.2 2585.57   169.6 2583.78   173.6 2582.29
   178.2 2581.67   199.9 2583.72   210.4 2585.24   221.5 2585.33   237.9 2587.66
   260.5  2587.2   273.5 2588.59   280.7 2587.48   286.5 2587.68   290.8 2590.02
   299.5 2597.32   312.5  2600.5   329.4 2608.02   335.8 2610.11   350.9 2613.62
#Mann= 6 ,-1,0
       0     .06       0    40.5     .07       0    60.6     .06       0
   165.2      .1       0   169.6    .045       0   199.9      .1       0
#XS Ineff= 2 , 0
                             215            2590
Permanent Ineff=
       F       F
Bank Sta=169.6,199.9
XS Rating Curve= 0 ,0
Exp/Cntr(USF)=0,0
Exp/Cntr=0.3,0.1

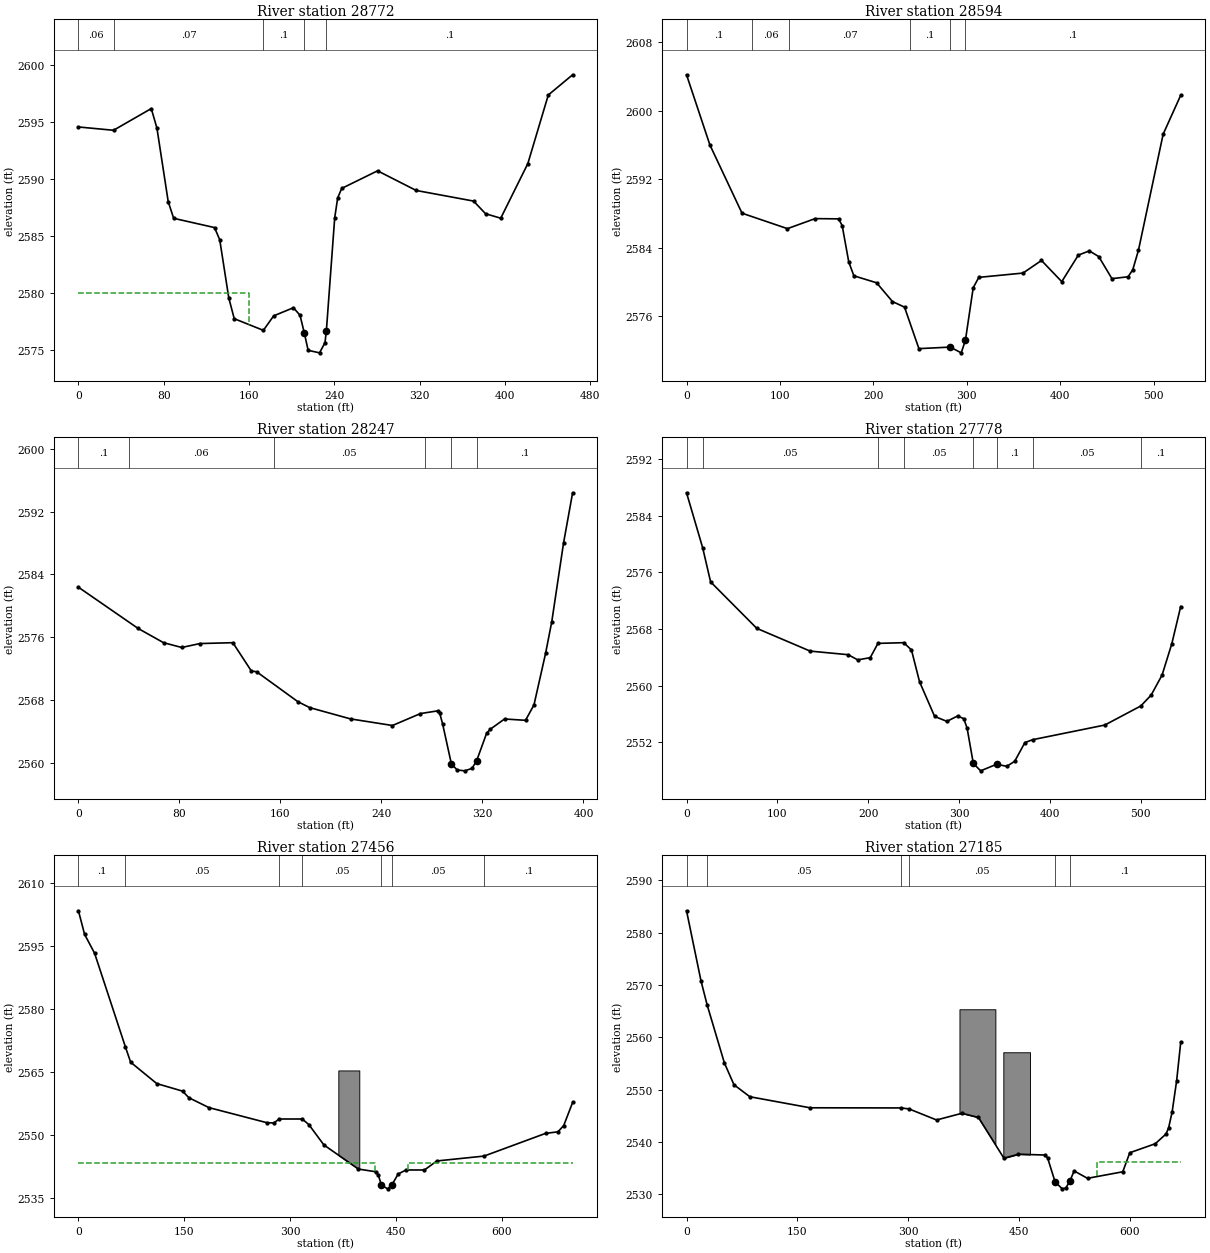
Type RM Length L Ch R = 1 ,28772   ,176,178.4,180.2
XS GIS Cut Line= 4
2189395.34666617429322.2709818522189446.31643906429285.202056115
2189579.14675628429129.2036603062189719.69976637428993.284265939
#Sta/Elev= 30
       0 2594.56    32.9 2594.27    68.3 2596.17    73.6 2594.46    84.2 2588.01
    89.3 2586.56   127.6 2585.75   132.5 2584.68     141 2579.58   146.1 2577.77
   173.4 2576.75   183.1 2578.02   201.6 2578.73   207.8 2578.07   211.9 2576.48
   215.4    2575   226.1 2574.78   231.2 2575.67   232.5 2576.72   240.3  2586.6
   243.1 2588.35   246.9 2589.18   280.5 2590.72   316.7    2589   370.5 2588.07
   381.8 2586.96     396 2586.57   421.4 2591.35   440.6 2597.36   463.4 2599.13
#Mann= 5 ,-1,0
       0     .06       0    32.9     .07       0   173.4      .1       0
   211.9    .045       0   232.5      .1       0
#XS Ineff= 2 , 0
             160    2580
Permanent Ineff=
       F       F
Bank Sta=211.9,232.5
XS Rating Curve= 0 ,0
Exp/Cntr(USF)=0,0
Exp/Cntr=0.3,0.1

Type RM Length L Ch R = 1 ,28594   ,348.5,346.2,340
XS GIS Cut Line= 4
2189430.87105334429482.9029933772189525.08790625429413.398757621
2189554.43413913 429399.497910472189833.99562072429143.104507458
#Sta/Elev= 30
       0 2604.18      25    2596    59.4 2588.04     108 2586.24   137.6 2587.41
   162.8 2587.38   166.6 2586.59   173.6 2582.37   179.1 2580.74   203.4 2579.93
   220.4 2577.74   233.3 2577.09   248.7 2572.25   282.2 2572.43     294 2571.76
   298.5 2573.23   306.8 2579.34   312.8 2580.56   360.1 2581.06   379.9 2582.53
   401.6 2580.06   419.3 2583.15   431.1 2583.65   441.2 2582.98   455.3 2580.41
   472.6 2580.63   477.6 2581.45   483.7 2583.73   510.1 2597.25   528.9 2601.79
#Mann= 6 ,-1,0
       0      .1       0      70     .06       0     110     .07       0
  239.55      .1       0   282.2    .045       0   298.5      .1       0
Bank Sta=282.2,298.5
XS Rating Curve= 0 ,0
Exp/Cntr(USF)=0,0
Exp/Cntr=0.3,0.1

Type RM Length L Ch R = 1 ,28247   ,465,469.1,473.5
XS GIS Cut Line= 3
2189764.49138497429767.0980906922189823.18385072 429680.60393064
2189971.45955366429435.022297634
#Sta/Elev= 30
       0 2582.38    47.2 2577.14    67.4 2575.32    81.8 2574.71    96.2 2575.21
   122.3 2575.32   136.9 2571.73   141.2 2571.61   173.9  2567.8   183.3 2567.05
   215.5 2565.62   248.7 2564.78   270.9  2566.3   284.4 2566.64   286.1 2566.37
   288.4 2565.01   295.4 2559.88     300 2559.12   305.9 2559.01   311.7 2559.32
   315.4  2560.3   323.3  2563.8   326.3 2564.32   337.5 2565.61   354.1 2565.44
   360.8  2567.4     370 2573.97   374.9    2578   384.2 2587.99   391.4  2594.4
#Mann= 6 ,-1,0
       0      .1       0      40     .06       0  154.53     .05       0
  274.53      .1       0   295.4    .045       0   315.4      .1       0
Bank Sta=295.4,315.4
XS Rating Curve= 0 ,0
Exp/Cntr(USF)=0,0
Exp/Cntr=0.3,0.1

Type RM Length L Ch R = 1 ,27778   ,326.4,322.4,316.3
XS GIS Cut Line= 2
2189916.22157138430094.2836646332190331.83868094429742.920365954
#Sta/Elev= 30
       0 2587.24    17.8 2579.46    26.5 2574.65    77.4 2568.08   136.1 2564.87
     178 2564.36   188.5 2563.63   202.3 2563.94   210.8 2565.96   239.2 2566.06
   247.7 2565.03   256.6 2560.54   273.2 2555.64   286.7 2554.94   298.5  2555.7
   305.3 2555.32     309 2553.97   315.8    2549   323.9 2547.95   341.4 2548.88
   352.7 2548.59   361.4  2549.3   372.6 2551.94   381.1 2552.35   460.6 2554.42
   500.3 2557.12   511.7 2558.66   523.7 2561.49   534.4 2565.91   544.2 2571.17
#Mann= 8 ,-1,0
       0      .1       0    17.8     .05       0   210.8    .016       0
   239.2     .05       0   315.8    .045       0   341.4      .1       0
   381.1     .05       0   500.3      .1       0
Bank Sta=315.8,341.4
XS Rating Curve= 0 ,0
Exp/Cntr(USF)=0,0
Exp/Cntr=0.3,0.1

Type RM Length L Ch R = 1 ,27456   ,266.5,270.8,274.9
XS GIS Cut Line= 3
   2190169.97968430411.197697817 2190363.3656008 430175.69296533
2190570.03128091429838.449533827
#Sta/Elev= 30
       0 2603.41     8.7 2597.81    22.9 2593.31    66.5 2571.06      74 2567.39
     111 2562.31   147.5 2560.52   156.5 2558.95   184.9  2556.6   266.6 2553.03
   276.9 2552.93   284.4 2553.89   317.1 2553.89   326.4 2552.58   347.9 2547.71
   396.8 2541.98   421.1 2541.35     425 2540.56   429.3 2538.19     438 2537.28
   443.9 2538.14   453.1 2540.81   464.2 2541.76   490.4 2541.77   507.9 2543.91
   574.8 2545.07     662 2550.47   679.5 2550.84   687.7 2552.33   700.3 2557.82
#Mann= 7 ,-1,0
       0      .1       0    66.5     .05       0   284.4    .016       0
   317.1     .05       0   429.3    .045       0   443.9     .05       0
   574.8      .1       0
#XS Ineff= 2 , 0
             420 2543.47     467         2543.47
Permanent Ineff=
       F       F
#Block Obstruct= 1 ,-1
  368.29     398 2565.44
Bank Sta=429.3,443.9
XS Rating Curve= 0 ,0
Exp/Cntr(USF)=0,0
Exp/Cntr=0.3,0.1

Type RM Length L Ch R = 1 ,27185   ,262.4,264.3,270.6
XS GIS Cut Line= 4
2190376.51788334430520.5425407532190599.45966995430236.798448702
2190700.79684568430096.0523712952190773.98480593 429983.45550937
#Sta/Elev= 30
       0  2584.2    19.5 2570.85    27.8 2566.25    51.2 2555.13    64.2 2550.95
    85.7 2548.66   167.1 2546.55   290.8 2546.52   301.3 2546.32   338.3 2544.22
   372.6  2545.5   394.9  2544.7   429.4 2536.92   449.1 2537.68   485.3 2537.52
   488.5 2536.98   498.6 2532.41   508.3 2531.06   513.2 2531.22   518.7 2532.57
   524.4 2534.48   542.5 2533.07   590.2 2534.32   599.7 2537.96   634.2 2539.68
   648.7 2541.54   652.2 2542.69     657 2545.76   663.1 2551.72   668.6 2559.04
#Mann= 6 ,-1,0
       0      .1       0    27.8     .05       0   290.8    .016       0
   301.3     .05       0   498.6    .045       0   518.7      .1       0
#XS Ineff= 2 , 0
                             556         2536.18
Permanent Ineff=
       F       F
#Block Obstruct= 2 ,-1
  369.26  417.86 2565.38   428.6  464.75 2557.16
Bank Sta=498.6,518.7
XS Rating Curve= 0 ,0
Exp/Cntr(USF)=0,0
Exp/Cntr=0.3,0.1