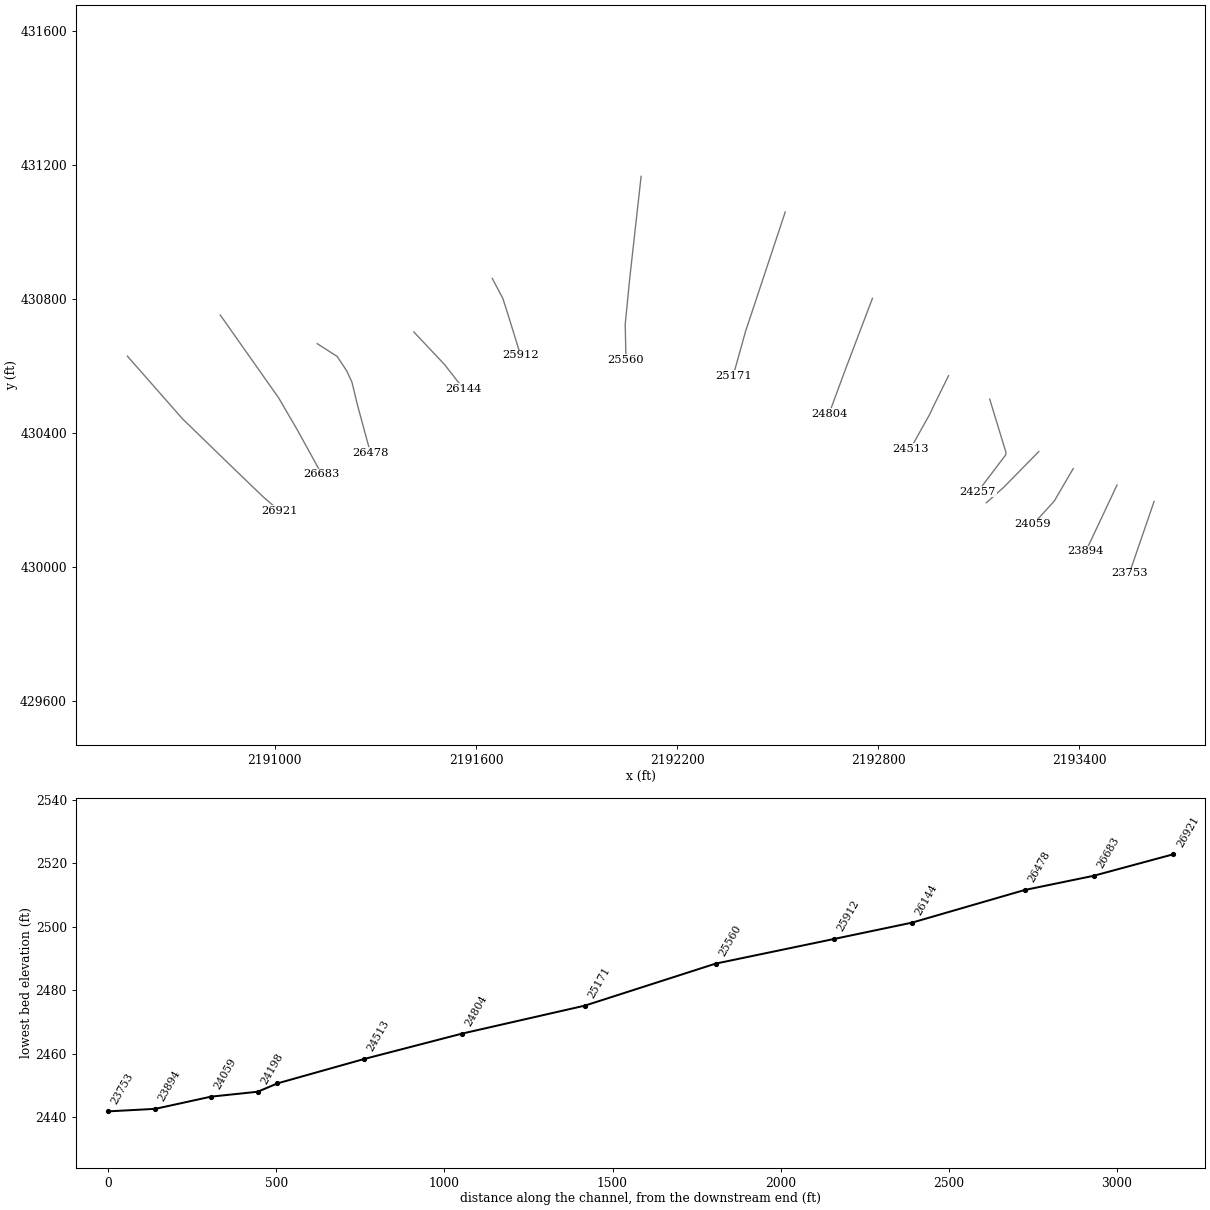
HEC-RAS study STMPNGCRK.prj: STMPNGCRK

--- STMPNGCRK.g01 (geometry) --- (continued)

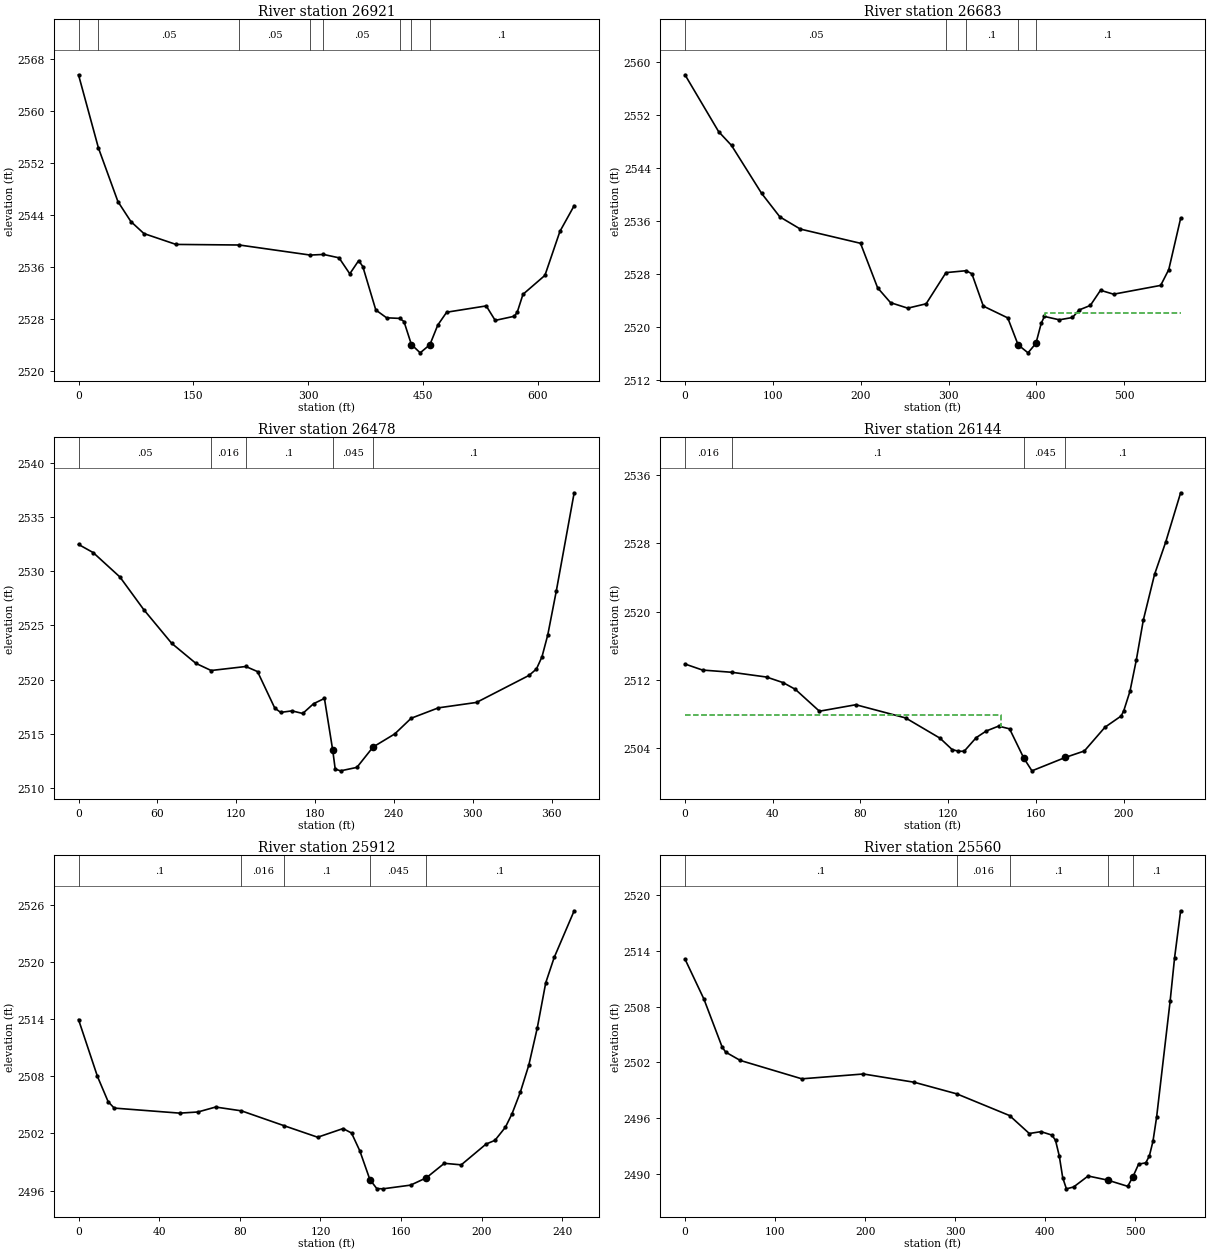
Type RM Length L Ch R = 1 ,26921   ,239.4,237.5,231.8
XS GIS Cut Line= 5
2190560.09145467430629.7393216232190724.05068992430443.177442055
2190858.66749115430312.4340987772190967.81731462430207.288154907
2191013.72970198 430168.54676976
#Sta/Elev= 30
       0 2565.62      26 2554.37    51.5 2546.11    68.5 2543.03    85.5 2541.19
   127.4 2539.52   210.2 2539.43   302.9 2537.88   320.1 2537.98   340.4 2537.46
   354.5    2535   366.1 2537.03   371.5 2536.12   388.5 2529.43   402.6 2528.23
   419.6 2528.14   425.3 2527.66     435 2524.12   446.5 2522.84   459.2  2524.1
   469.5 2527.12   481.1 2529.09   532.8 2530.06   544.5 2527.83   569.5 2528.47
   573.3 2529.09   580.8 2531.84   609.5 2534.76   629.1 2541.53   647.7 2545.48
#Mann= 8 ,-1,0
       0      .1       0      26     .05       0   210.2     .05       0
   302.9    .016       0   320.1     .05       0   419.6      .1       0
     435    .045       0   459.2      .1       0
Bank Sta=435,459.2
XS Rating Curve= 0 ,0
Exp/Cntr(USF)=0,0
Exp/Cntr=0.3,0.1

Type RM Length L Ch R = 1 ,26683   ,208.1,205.3,199.9
XS GIS Cut Line= 4
2190837.03904861430752.492076319 2191011.5641846430504.778980084
2191066.73664694430410.1976160662191139.92460719430277.333318995
#Sta/Elev= 30
       0 2558.06    38.3 2549.47      53 2547.38    87.2 2540.15     108 2536.59
   131.3 2534.75   199.8  2532.6   219.3 2525.87     234 2523.63   253.6  2522.8
   274.5 2523.46   297.1 2528.17   320.1 2528.46   326.6 2527.99   339.6 2523.11
   367.4 2521.33   379.2 2517.26   390.5 2516.05   399.5 2517.49   405.5 2520.51
   409.1 2521.55   426.1 2521.04   441.1 2521.39   448.7 2522.53   461.4 2523.21
     473  2525.5   487.9 2524.91   541.5 2526.24   550.7 2528.63   564.2 2536.37
#Mann= 5 ,-1,0
       0     .05       0   297.1    .016       0   320.1      .1       0
   379.2    .045       0   399.5      .1       0
#XS Ineff= 2 , 0
                          409.35         2522.12
Permanent Ineff=
       F       F
Bank Sta=379.2,399.5
XS Rating Curve= 0 ,0
Exp/Cntr(USF)=0,0
Exp/Cntr=0.3,0.1

Type RM Length L Ch R = 1 ,26478   ,328,334.6,337.9
XS GIS Cut Line= 6
2191126.41298376430666.9184612562191186.08932058430628.635528201
2191214.23853606 430585.848720672191230.00209673430552.069662092
2191246.89162602430482.2596076992191285.17455907430341.513530292
#Sta/Elev= 30
       0 2532.49    11.2 2531.73    31.5 2529.48    49.6 2526.47    70.9 2523.35
    89.3  2521.5   100.9 2520.84   127.3 2521.21   136.2 2520.74   149.3 2517.37
   153.8 2516.97   162.4 2517.11   170.6 2516.87   178.8 2517.77   187.1 2518.26
   193.4 2513.48   195.3 2511.73   199.4 2511.57   211.8 2511.89   224.1 2513.77
   240.6 2514.98   253.1 2516.43   273.8 2517.39   302.8 2517.89   342.8 2520.39
   348.4 2520.98   352.6  2522.1     357 2524.12   363.5 2528.18   377.1 2537.26
#Mann= 5 ,-1,0
       0     .05       0   100.9    .016       0   127.3      .1       0
   193.4    .045       0   224.1      .1       0
Bank Sta=193.4,224.1
XS Rating Curve= 0 ,0
Exp/Cntr(USF)=0,0
Exp/Cntr=0.3,0.1

Type RM Length L Ch R = 1 ,26144   ,235,231.2,221.4
XS GIS Cut Line= 3
2191414.66095029430701.8234884532191505.86440845430604.990187197
2191563.28880803430531.802226946
#Sta/Elev= 30
       0 2513.85       8 2513.14    21.3 2512.88    37.2 2512.32    44.8 2511.66
    50.3 2510.88    61.3 2508.31    77.9 2509.07   100.6 2507.52   116.3 2505.14
   121.8 2503.81   124.7 2503.61   127.3 2503.61   132.8 2505.21   137.4 2505.99
     143 2506.56     148 2506.24   154.5  2502.8   158.2 2501.31   173.5 2502.89
   182.1 2503.64   191.5 2506.43   198.9 2507.75   200.1 2508.39   202.9 2510.65
   205.8 2514.33     209 2519.02   214.1 2524.36   219.2 2528.17     226 2533.95
#Mann= 4 ,-1,0
       0    .016       0    21.3      .1       0   154.5    .045       0
   173.5      .1       0
#XS Ineff= 2 , 0
          143.94 2507.83
Permanent Ineff=
       F       F
Bank Sta=154.5,173.5
XS Rating Curve= 0 ,0
Exp/Cntr(USF)=0,0
Exp/Cntr=0.3,0.1

Type RM Length L Ch R = 1 ,25912   ,352.3,352.9,341.8
XS GIS Cut Line= 5
2191648.62920855430861.5341915942191680.31013898 430801.54178176
2191699.80402441430740.107506161 2191728.6170274430646.939780404
2191733.89281472430631.849155589
#Sta/Elev= 30
       0 2513.96     9.4 2507.98    14.7 2505.33    17.7 2504.66    50.2 2504.13
    59.2 2504.25      68 2504.77    80.8 2504.37   101.8 2502.82   118.6  2501.6
   131.2 2502.51   135.4 2502.04   139.5 2500.17   144.5 2497.15   147.9 2496.21
   150.9 2496.18   164.7 2496.57   172.5 2497.34   181.4 2498.86   189.8  2498.7
   202.1 2500.88   206.5 2501.27   211.7 2502.65     215 2504.07   219.1 2506.33
   223.3 2509.17   227.5 2513.07   231.7 2517.82   235.9 2520.48   245.8 2525.38
#Mann= 5 ,-1,0
       0      .1       0    80.8    .016       0   101.8      .1       0
   144.5    .045       0   172.5      .1       0
Bank Sta=144.5,172.5
XS Rating Curve= 0 ,0
Exp/Cntr(USF)=0,0
Exp/Cntr=0.3,0.1

Type RM Length L Ch R = 1 ,25560   ,389.9,388.4,379.3
XS GIS Cut Line= 4
2192092.65209317431166.085160637 2192058.7150005430861.711032386
2192045.23696379430724.9136486892192047.49709799430618.445011423
#Sta/Elev= 30
       0 2513.11      21 2508.81    41.2 2503.66    45.2  2503.1    61.3 2502.21
   129.7 2500.23   198.1 2500.75   254.5 2499.86   301.8 2498.61   360.3 2496.28
   382.2 2494.35   395.2 2494.55   407.3 2494.18   411.3 2493.62   415.5 2491.93
   419.3  2489.6   423.4  2488.4   431.4  2488.6   447.5 2489.78   469.1 2489.34
   491.5 2488.67   497.3 2489.71   503.5 2491.05   511.5  2491.2   515.5 2491.94
   519.5 2493.52   523.5 2496.08   538.6 2508.64   543.5 2513.26   550.2  2518.3
#Mann= 5 ,-1,0
       0      .1       0   301.8    .016       0   360.3      .1       0
   469.1    .045       0   497.3      .1       0
Bank Sta=469.1,497.3
XS Rating Curve= 0 ,0
Exp/Cntr(USF)=0,0
Exp/Cntr=0.3,0.1

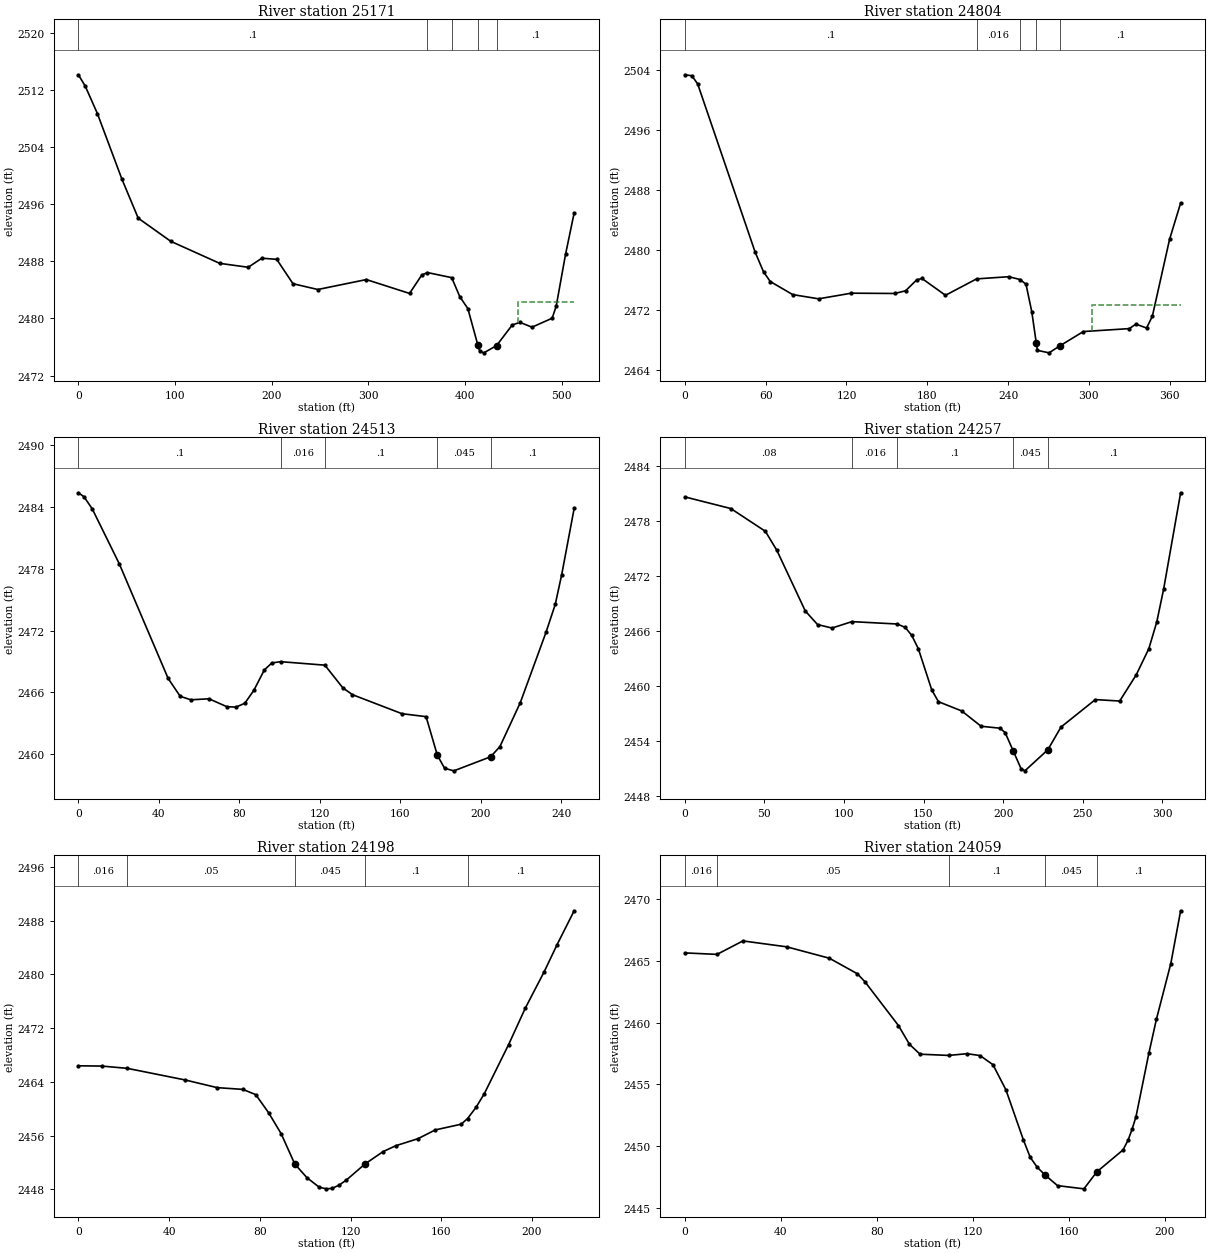
Type RM Length L Ch R = 1 ,25171   ,354.3,366.8,352.9
XS GIS Cut Line= 3
2192522.61407163431059.8815093752192404.38736661430704.075425691
2192367.23040218430571.211128619
#Sta/Elev= 30
       0 2514.09     7.1  2512.5    19.7 2508.65      45  2499.5    61.9 2494.03
    95.6 2490.79   146.2 2487.71   175.7 2487.16   189.8 2488.43   205.2 2488.27
     222 2484.86   247.7 2484.05   297.9 2485.44   342.6  2483.5   355.2 2486.07
   361.1 2486.42   386.2 2485.71   394.6 2483.04   402.9 2481.39   413.2 2476.31
   415.3  2475.4   419.5 2475.19   432.6  2476.2   448.9  2479.1   456.9 2479.45
   469.3 2478.78   490.1 2480.03   494.3  2481.7     504 2488.98   512.9 2494.77
#Mann= 5 ,-1,0
       0      .1       0   361.1    .016       0   386.2      .1       0
   413.2    .045       0   432.6      .1       0
#XS Ineff= 2 , 0
                          454.99         2482.37
Permanent Ineff=
       F       F
Bank Sta=413.2,432.6
XS Rating Curve= 0 ,0
Exp/Cntr(USF)=0,0
Exp/Cntr=0.3,0.1

Type RM Length L Ch R = 1 ,24804   ,288.6,290.8,283.7
XS GIS Cut Line= 3
2192782.71282268430802.0346955662192700.51711348 430585.84872067
2192653.22643147430457.488298075
#Sta/Elev= 30
       0  2503.3     5.2 2503.17     9.5 2502.09    52.2 2479.72    58.4 2477.11
    63.4 2475.82    80.1 2474.08    99.3 2473.52   123.6 2474.27   155.9 2474.23
   163.9 2474.59   172.1 2476.03     176 2476.23   193.5 2473.99   216.6 2476.17
   240.5 2476.46     249 2476.08   253.3 2475.45   257.6 2471.79  260.962467.604
   261.8 2466.67   270.4 2466.34   278.6 2467.29   295.9 2469.17     330 2469.56
   334.9 2470.16   342.8 2469.64   347.1  2471.2   359.9 2481.43   368.1 2486.25
#Mann= 5 ,-1,0
       0      .1       0   216.6    .016       0     249      .1       0
  260.96    .045       0   278.6      .1       0
#XS Ineff= 2 , 0
                             302         2472.64
Permanent Ineff=
       F       F
Bank Sta=260.96,278.6
XS Rating Curve= 0 ,0
Exp/Cntr(USF)=0,0
Exp/Cntr=0.3,0.1

Type RM Length L Ch R = 1 ,24513   ,258.5,256.3,253
XS GIS Cut Line= 4
2193009.79367828430571.3433491182192965.93782943 430482.52927881
2192954.33765235430457.5203234352192895.96144486430352.964550799
#Sta/Elev= 30
       0  2485.4     2.8 2485.01     6.9 2483.83    20.3  2478.5    44.6 2467.34
    50.6  2465.6    55.9 2465.26    64.9 2465.36    73.8 2464.59    78.3 2464.55
    82.7 2464.92    87.2 2466.18    92.4 2468.16    96.1 2468.84   100.5 2468.97
   122.5 2468.63   131.4 2466.43   136.2 2465.76   160.8 2463.91   172.8 2463.62
   178.4 2459.87     182  2458.6   186.6 2458.35   204.9 2459.72   209.5 2460.71
   219.6 2464.97   232.4 2471.82     237 2474.54   240.2 2477.43   246.4 2483.88
#Mann= 5 ,-1,0
       0      .1       0   100.5    .016       0   122.5      .1       0
   178.4    .045       0   204.9      .1       0
Bank Sta=178.4,204.9
XS Rating Curve= 0 ,0
Exp/Cntr(USF)=0,0
Exp/Cntr=0.3,0.1

Type RM Length L Ch R = 1 ,24257   ,61.1,58.9,56.4
XS GIS Cut Line= 4
2193132.52103112430501.6213139312193180.60664158430343.764511915
2193180.60664158430335.5073868872193097.06396482430225.250482094
#Sta/Elev= 30
       0 2480.59    28.9 2479.32    50.6 2476.84    57.8 2474.77    75.7 2468.15
    83.4 2466.67    92.5 2466.29     105 2466.99   133.5 2466.73   138.5 2466.36
   142.6 2465.49   146.8 2464.01   155.2 2459.53   159.4 2458.26     174 2457.25
   186.2 2455.58   198.1 2455.37   201.3 2454.89   206.3 2452.93   211.3 2450.95
   213.7 2450.72   228.12453.011   236.4 2455.49     258 2458.49   273.3 2458.33
   283.7 2461.19   291.6 2464.03   296.6 2466.95   300.9 2470.52   311.6 2481.04
#Mann= 5 ,-1,0
       0     .08       0     105    .016       0   133.5      .1       0
   206.3    .045       0   228.1      .1       0
Bank Sta=206.3,228.1
XS Rating Curve= 0 ,0
Exp/Cntr(USF)=0,0
Exp/Cntr=0.3,0.1

Type RM Length L Ch R = 1 ,24198   ,138.4,138.7,139.1
XS GIS Cut Line= 3
2193278.99020845 430344.979341372193174.11413255430238.196427725
2193122.62951347430192.432321877
#Sta/Elev= 30
       0 2466.39    10.3 2466.35    21.6 2466.01    47.1 2464.28    61.2 2463.14
    72.5 2462.88    78.2  2462.1    83.9 2459.39    89.4 2456.29    95.4 2451.78
   100.8 2449.73   106.2 2448.32   109.3 2448.08   111.9 2448.15     115 2448.64
   118.2  2449.4   126.3 2451.76   134.3 2453.61   139.9 2454.49   149.7 2455.54
   157.4 2456.85   168.8  2457.7   171.6 2458.54   175.3 2460.19     179 2462.25
   189.7 2469.55   197.1    2475   205.4  2480.4   211.1 2484.44   218.6 2489.46
#Mann= 5 ,-1,0
       0    .016       0    21.6     .05       0    95.4    .045       0
   126.3      .1       0   171.6      .1       0
Bank Sta=95.4,126.3
XS Rating Curve= 0 ,0
Exp/Cntr(USF)=0,0
Exp/Cntr=0.3,0.1

Type RM Length L Ch R = 1 ,24059   ,160.9,165.7,170.1
XS GIS Cut Line= 3
2193381.61449549430294.0386103312193324.94145677430197.007498587
2193261.39895881430127.454223797
#Sta/Elev= 30
       0 2465.64    13.4 2465.52    24.2 2466.61    42.5 2466.13    60.2 2465.21
    71.9 2463.95    75.1 2463.29      89 2459.76    93.6 2458.24      98 2457.44
   109.9 2457.34   117.6 2457.48     123 2457.33   128.4 2456.59   133.8 2454.55
   141.1 2450.49   143.9  2449.1   146.8  2448.3   150.1 2447.66   155.3  2446.8
   166.3 2446.54   171.7 2447.92   182.6 2449.69   184.7 2450.48   186.4 2451.38
     188 2452.38   193.4 2457.55   196.5 2460.26   202.5 2464.77   206.6 2469.05
#Mann= 5 ,-1,0
       0    .016       0    13.4     .05       0   109.9      .1       0
   150.1    .045       0   171.7      .1       0
#Block Obstruct= 1 ,-1
      87     113    2455
Bank Sta=150.1,171.7
XS Rating Curve= 0 ,0
Exp/Cntr(USF)=0,0
Exp/Cntr=0.3,0.1

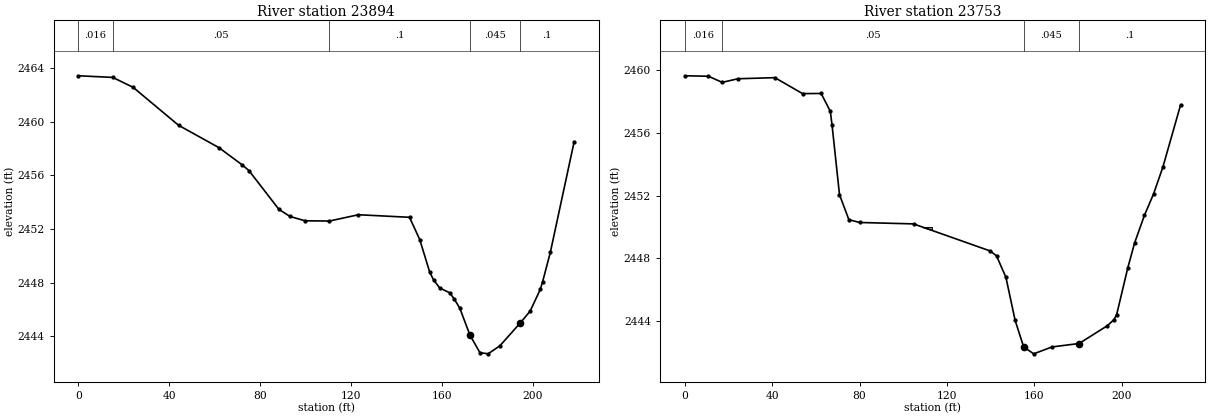
Type RM Length L Ch R = 1 ,23894   ,138.9,140.6,142.3
XS GIS Cut Line= 3
2193512.38792866430245.080113232 2193435.9621742430083.010670103
2193419.11116971430047.749955452
#Sta/Elev= 30
       0 2463.43    15.1 2463.31    24.1 2462.57    44.1 2459.74    61.8 2458.08
    72.2 2456.78    75.1 2456.36    88.3 2453.47    93.2 2452.94    99.8 2452.62
   110.5  2452.6   123.3 2453.07   145.8 2452.88   150.3 2451.22   154.7 2448.79
   156.4 2448.21   159.1 2447.61   163.5 2447.25   165.4 2446.81   167.9 2446.12
   172.4  2444.1   176.8 2442.79   180.4  2442.7   185.6  2443.3   194.5 2444.99
   198.9 2445.88   203.4 2447.51   204.4 2448.07   207.8 2450.26   218.3 2458.52
#Mann= 5 ,-1,0
       0    .016       0    15.1     .05       0   110.5      .1       0
   172.4    .045       0   194.5      .1       0
Bank Sta=172.4,194.5
XS Rating Curve= 0 ,0
Exp/Cntr(USF)=0,0
Exp/Cntr=0.5,0.3

Type RM Length L Ch R = 1 ,23753   ,146.4,145.1,144.3
XS GIS Cut Line= 2
2193622.90425124430196.1488161822193549.05756443429981.478214979
#Sta/Elev= 30
       0 2459.66    10.8 2459.63    17.1 2459.24    24.3 2459.47    41.2 2459.54
    53.9 2458.52    62.4 2458.53    66.6 2457.39    67.4 2456.51    70.8 2452.07
    75.1 2450.47      80 2450.29   104.7  2450.2   139.8 2448.47   142.7 2448.16
     147 2446.79   151.2 2444.05   155.1 2442.35   159.7  2441.9   168.1 2442.34
   180.5 2442.56   193.5  2443.7   196.5 2444.09   197.7  2444.4   202.8 2447.39
   205.9 2448.97   210.4 2450.74   214.6 2452.11   218.9 2453.84     227 2457.81
#Mann= 4 ,-1,0
       0    .016       0    17.1     .05       0   155.1    .045       0
   180.5      .1       0
#Block Obstruct= 1 ,-1
      57     113    2450
Bank Sta=155.1,180.5
XS Rating Curve= 0 ,0
Exp/Cntr(USF)=0,0
Exp/Cntr=0.3,0.1