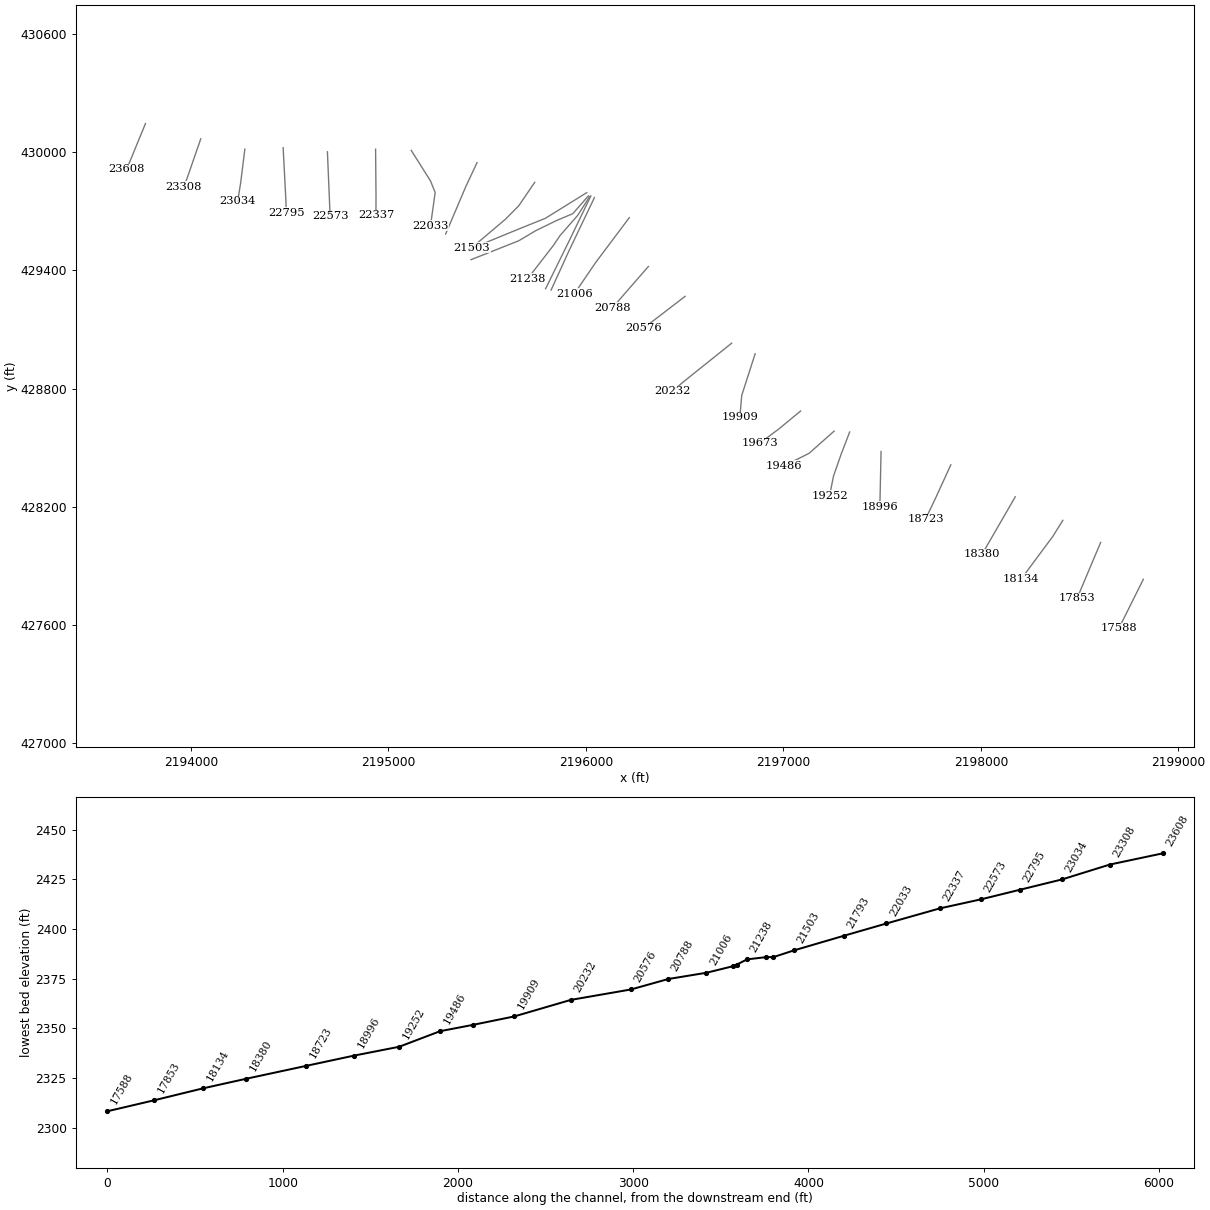
HEC-RAS study STMPNGCRK.prj: STMPNGCRK

--- STMPNGCRK.g01 (geometry) --- (continued)

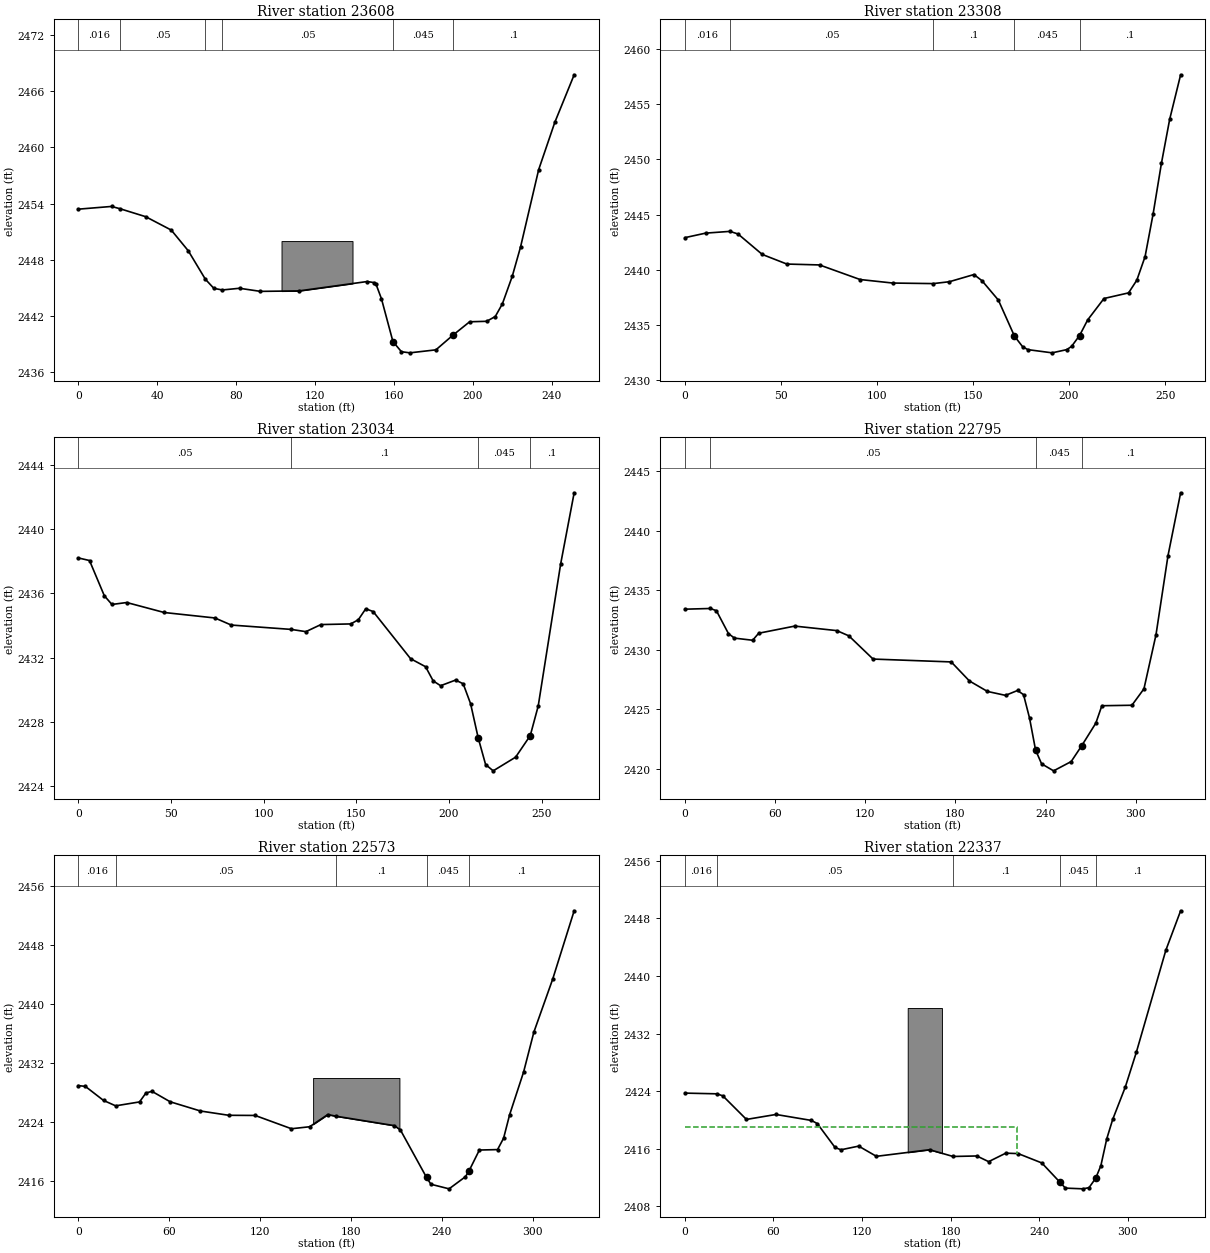
Type RM Length L Ch R = 1 ,23608   ,299.6,300.3,301.2
XS GIS Cut Line= 2
2193769.04750857430144.7613782862193673.70562139 429912.12717356
#Sta/Elev= 30
       0  2453.4    16.8 2453.69    21.2 2453.44    34.1  2452.6    47.1 2451.17
    55.7 2448.97    64.4 2445.93    68.7 2444.96      73 2444.79    81.7 2444.97
    92.3 2444.64   111.9 2444.69   146.5 2445.69     150 2445.57   150.9 2445.42
   153.7 2443.84   159.5 2439.29   163.8 2438.21   168.1 2438.09   181.3 2438.41
   189.8 2439.95   198.4  2441.4     207 2441.45   211.4 2441.96     215 2443.31
     220 2446.24   224.2 2449.36   233.4 2457.61   241.6 2462.66   251.4 2467.72
#Mann= 6 ,-1,0
       0    .016       0    21.2     .05       0    64.4    .016       0
      73     .05       0   159.5    .045       0   189.8      .1       0
#Block Obstruct= 1 ,-1
     103     139    2450
Bank Sta=159.5,189.8
XS Rating Curve= 0 ,0
Exp/Cntr(USF)=0,0
Exp/Cntr=0.3,0.1

Type RM Length L Ch R = 1 ,23308   ,271.7,274.3,277.4
XS GIS Cut Line= 3
2194049.19767773430067.3817799042193979.31502409429865.466782963
2193963.88292022429823.838517224
#Sta/Elev= 30
       0 2442.92    10.8 2443.33    23.5 2443.49    27.7 2443.25    40.3  2441.4
    53.1 2440.53    70.1 2440.45    91.2 2439.13   108.2 2438.81   129.3 2438.76
   137.7 2438.93   150.5 2439.58   154.7 2439.02   163.2 2437.27   171.6    2434
   175.9 2433.03   178.6 2432.78   191.2 2432.49   198.8 2432.78   201.3 2433.07
   205.5 2434.06   209.7 2435.47   218.2 2437.41     231 2437.92   235.3 2439.07
   239.6 2441.21   243.8 2445.09   248.1 2449.65   252.4 2453.64   258.1 2457.67
#Mann= 5 ,-1,0
       0    .016       0    23.5     .05       0   129.3      .1       0
   171.6    .045       0   205.5      .1       0
Bank Sta=171.6,205.5
XS Rating Curve= 0 ,0
Exp/Cntr(USF)=0,0
Exp/Cntr=0.3,0.1

Type RM Length L Ch R = 1 ,23034   ,234.2,238.2,242.1
XS GIS Cut Line= 3
 2194272.4526729430015.0964117172194251.47745772429845.387852532
2194236.22275577429750.045965349
#Sta/Elev= 30
       0  2438.2       6 2438.04      14 2435.85    18.1 2435.31    26.1 2435.43
    46.3 2434.81    73.7 2434.47    82.5 2434.03   114.8 2433.76   122.8 2433.62
   130.9 2434.06     147  2434.1   151.1 2434.36   155.1 2435.04   159.1 2434.87
   179.3 2431.94   187.4 2431.44   191.5 2430.56   195.5 2430.26   203.6 2430.61
   207.7 2430.38   211.7 2429.14   215.8 2427.02   219.8 2425.36   223.9 2424.97
     236 2425.82   243.9 2427.16   248.2    2429   260.3 2437.82   267.6 2442.25
#Mann= 4 ,-1,0
       0     .05       0   114.8      .1       0   215.8    .045       0
   243.9      .1       0
Bank Sta=215.8,243.9
XS Rating Curve= 0 ,0
Exp/Cntr(USF)=0,0
Exp/Cntr=0.3,0.1

Type RM Length L Ch R = 1 ,22795   ,222.3,222.1,221.7
XS GIS Cut Line= 3
2194466.43548442430022.1797660722194480.46538759429752.970292494
 2194481.7459507429692.733553298
#Sta/Elev= 30
       0  2433.4      17 2433.46      21 2433.27      29 2431.35      33 2430.97
    45.1 2430.79    49.1 2431.38    73.1 2431.98   101.1  2431.6   109.1 2431.16
   125.2 2429.21   177.2 2428.97   189.3 2427.37   201.3 2426.49   213.3 2426.16
   221.3 2426.57   225.3 2426.22   229.3 2424.25   233.3 2421.57   237.3 2420.41
   245.3 2419.82     257  2420.6     264 2421.93   273.4 2423.83   277.4 2425.29
   297.4 2425.33   305.4 2426.71   313.4 2431.24   321.4  2437.9   329.8 2443.18
#Mann= 4 ,-1,0
       0    .016       0      17     .05       0   233.3    .045       0
     264      .1       0
Bank Sta=233.3,264
XS Rating Curve= 0 ,0
Exp/Cntr(USF)=0,0
Exp/Cntr=0.3,0.1

Type RM Length L Ch R = 1 ,22573   ,237.3,236.6,235.3
XS GIS Cut Line= 2
2194690.66285179430001.7299020462194704.40227083429674.626041058
#Sta/Elev= 30
       0 2428.97     4.6 2428.86    16.6 2426.96    24.6 2426.23    40.4 2426.76
    44.6 2427.97    48.6 2428.19    60.6 2426.78    80.6 2425.53    99.3 2424.95
   116.7 2424.93   140.7 2423.13   152.7  2423.4   164.7 2425.05   170.3 2424.82
   208.7 2423.55   212.7 2422.95   229.9 2416.55   232.8 2415.62   244.8    2415
   255.6 2416.64   257.92417.396   264.8 2420.25   276.8 2420.31   280.8 2421.85
   284.8 2425.04     294  2430.8   300.8 2436.21   313.2 2443.36   327.4 2452.62
#Mann= 5 ,-1,0
       0    .016       0    24.6     .05       0   170.3      .1       0
   229.9    .045       0   257.9      .1       0
#Block Obstruct= 1 ,-1
     155     212    2430
Bank Sta=229.9,257.9
XS Rating Curve= 0 ,0
Exp/Cntr(USF)=0,0
Exp/Cntr=0.3,0.1

Type RM Length L Ch R = 1 ,22337   ,285.8,303.7,312.5
XS GIS Cut Line= 3
 2194934.7235061430014.8990528712194936.81976495429768.230059441
2194936.45905158429679.164509151
#Sta/Elev= 30
       0 2423.72    21.7 2423.62    25.7 2423.34    41.7 2420.06    61.7 2420.75
    85.7 2419.92    89.7 2419.48   101.7 2416.16   105.7 2415.84   117.7 2416.35
   129.7 2414.93   165.7 2415.85   181.6 2414.91   197.7 2414.98   205.7 2414.19
   217.3 2415.37   225.7 2415.31   241.7 2414.01   253.7 2411.39   257.7 2410.51
   269.7 2410.41   273.7 2410.58   278.2 2411.89   281.7 2413.64   285.7 2417.38
   289.7 2420.06   298.2 2424.54   305.7 2429.39   325.7 2443.59   335.7 2449.07
#Mann= 5 ,-1,0
       0    .016       0    21.7     .05       0   181.6      .1       0
   253.7    .045       0   278.2      .1       0
#XS Ineff= 2 , 0
             225 2419.05
Permanent Ineff=
       F       F
#Block Obstruct= 1 ,-1
   150.9  174.07 2435.55
Bank Sta=253.7,278.2
XS Rating Curve= 0 ,0
Exp/Cntr(USF)=0,0
Exp/Cntr=0.3,0.1

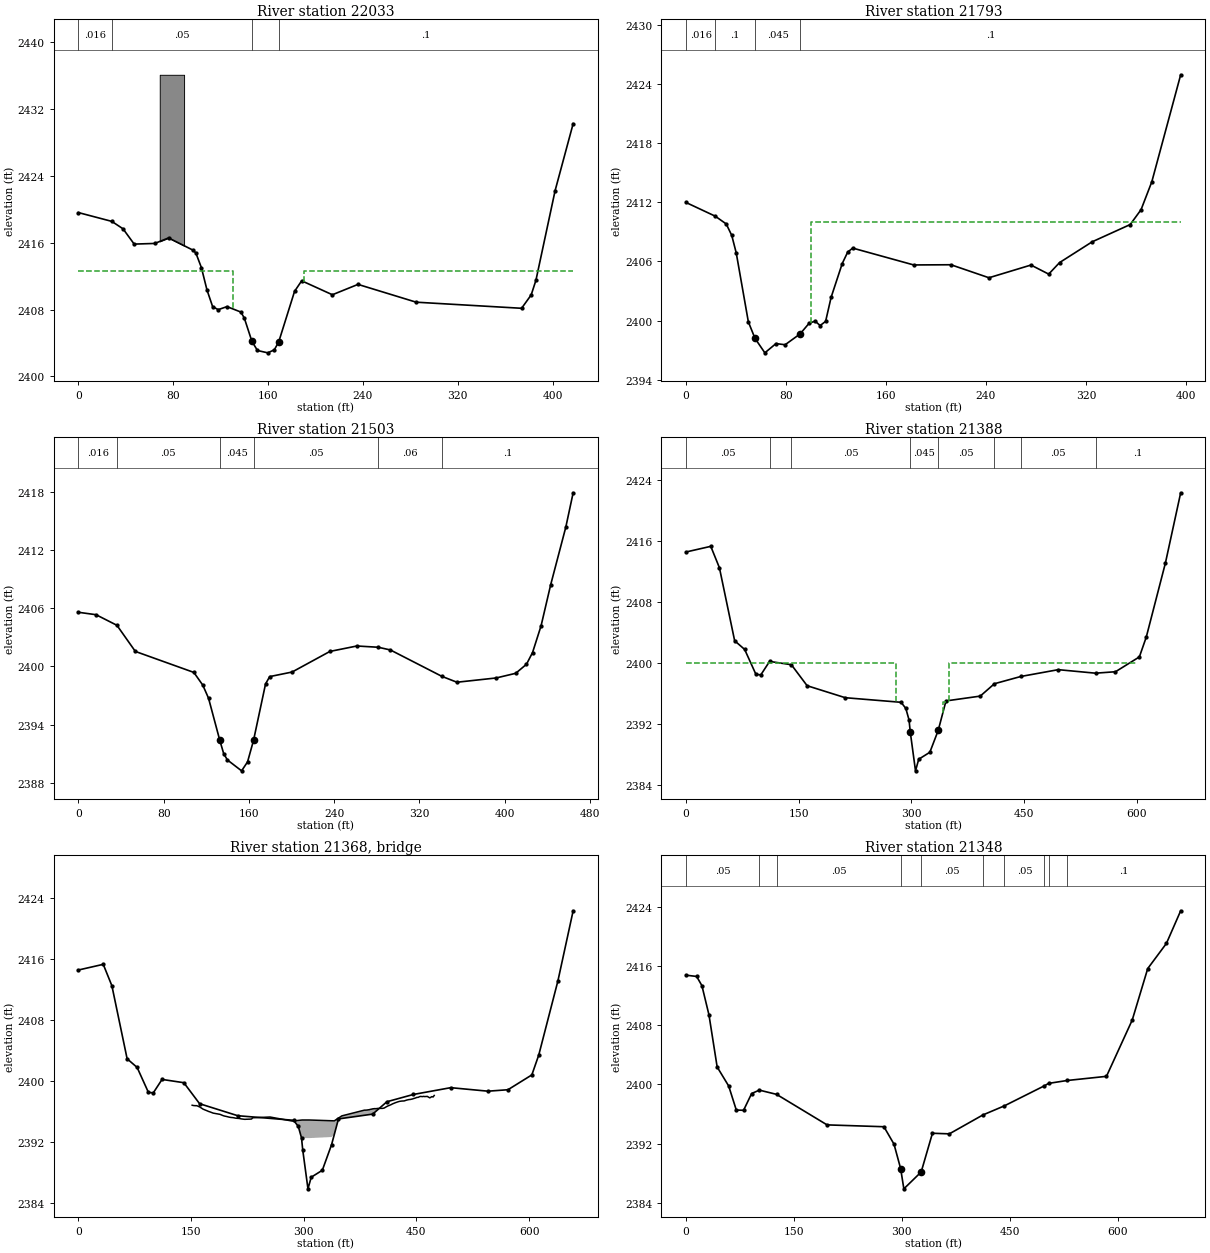
Type RM Length L Ch R = 1 ,22033   ,253.4,240.2,221
XS GIS Cut Line= 5
2195115.12851045430008.9766066632195163.92048395429931.409879559
2195212.71245746429853.8431524552195236.48290608429795.042569005
2195212.71245746429626.147276117
#Sta/Elev= 30
       0 2419.61    28.1 2418.56    37.6 2417.67      47 2415.84    64.4 2415.92
      76 2416.58    96.3 2415.14      99 2414.79   103.7 2413.03   108.4 2410.36
   113.2 2408.35   117.9    2408   125.3 2408.36     137 2407.71   139.9 2406.99
   146.3 2404.21     151 2403.11   159.7 2402.83   165.2 2403.19   168.9 2404.13
   182.3 2410.19   188.3 2411.45   214.2 2409.78   235.8 2411.02   284.9 2408.89
   373.8 2408.16   381.9 2409.76   385.9 2411.51   402.1 2422.25   417.3 2430.25
#Mann= 4 ,-1,0
       0    .016       0    28.1     .05       0   146.3    .045       0
   168.9      .1       0
#XS Ineff= 2 , 0
             130 2412.62  190.14         2412.62
Permanent Ineff=
       F       F
#Block Obstruct= 1 ,-1
   68.56    89.1  2436.1
Bank Sta=146.3,168.9
XS Rating Curve= 0 ,0
Exp/Cntr(USF)=0,0
Exp/Cntr=0.3,0.1

Type RM Length L Ch R = 1 ,21793   ,290.1,289.3,281.2
XS GIS Cut Line= 3
2195448.38827331429946.3553924432195391.95981585429825.858071588
2195289.42875151429583.990918734
#Sta/Elev= 30
       0 2411.98    23.4 2410.59    32.2  2409.8    36.6 2408.64    40.2 2406.86
    49.9 2399.86    55.2 2398.19    63.1 2396.72      72 2397.66    79.3 2397.54
    91.3 2398.64    98.5 2399.72   103.3 2399.94   107.3 2399.49   111.7 2399.91
   116.1 2402.35     125 2405.78   129.4 2406.95   133.4 2407.35   182.2 2405.64
     212 2405.66   242.4 2404.34     276 2405.63   290.2 2404.71   298.9 2405.88
     325 2407.99   355.4 2409.74   364.1 2411.25   372.7 2414.08   395.8 2424.94
#Mann= 4 ,-1,0
       0    .016       0    23.4      .1       0    55.2    .045       0
    91.3      .1       0
#XS Ineff= 2 , 0
                             100            2410
Permanent Ineff=
       F       F
Bank Sta=55.2,91.3
XS Rating Curve= 0 ,0
Exp/Cntr(USF)=0,0
Exp/Cntr=0.3,0.1

Type RM Length L Ch R = 1 ,21503   ,124.8,115.6,106.1
XS GIS Cut Line= 4
2195740.71215682429846.7978806672195659.91161719429727.702394192
2195591.98007498429658.9501799772195421.25181934429514.380561898
#Sta/Elev= 30
       0 2405.57    16.5 2405.32    36.1 2404.23    53.4 2401.54   108.3 2399.38
   116.7 2398.07   122.1 2396.72   132.5 2392.45   136.3 2391.02   139.8 2390.37
   153.1 2389.25   158.7 2390.17   164.3 2392.38   175.6  2398.2   179.5 2398.95
   200.5 2399.42     236 2401.54   261.3  2402.1   281.4 2401.97   292.8 2401.69
     341 2398.98   355.2 2398.37   392.1 2398.81   410.4 2399.29   420.5 2400.22
   426.2 2401.43   434.2 2404.18   443.2  2408.4   457.4 2414.33   464.3 2417.87
#Mann= 6 ,-1,0
       0    .016       0    36.1     .05       0   132.5    .045       0
   164.3     .05       0   281.4     .06       0     341      .1       0
Bank Sta=132.5,164.3
XS Rating Curve= 0 ,0
Exp/Cntr(USF)=0,0
Exp/Cntr=0.5,0.3

Type RM Length L Ch R = 1 ,21388   ,40.3,40.2,43.4
BEGIN DESCRIPTION:
Channel burned based on survey STA102BU
END DESCRIPTION:
XS GIS Cut Line= 4
2196004.20278278429794.4412678512195794.29999079429663.773304629
  2195666.412197 429612.340170172195413.41677885429508.083816536
#Sta/Elev= 30
       0 2414.55      33 2415.29    44.5 2412.49    64.8 2402.93    78.1  2401.8
    93.2 2398.52    99.7 2398.48   111.3 2400.23   140.3  2399.8   161.3 2397.05
   212.1 2395.48   286.4 2394.88   292.7 2394.08     297 2392.57  298.63    2391
   305.6 2385.91   309.9 2387.43   324.7 2388.34   335.8 2391.19   346.2 2395.06
   391.8 2395.69   410.7 2397.31   445.9 2398.26   495.7 2399.15   545.3 2398.69
   571.9 2398.88   603.7 2400.82   612.9 2403.42   638.4 2413.12   658.7  2422.3
#Mann= 8 ,-1,0
       0     .05       0   111.3    .016       0   140.3     .05       0
  298.63    .045       0   335.8     .05       0   410.7    .016       0
   445.9     .05       0   545.3      .1       0
#XS Ineff= 4 ,-1
       0     280    2400     280     286 2394.68     342     350  2394.9
     350     600    2400
Permanent Ineff=
       F       F       F       F
Bank Sta=298.63,335.8
XS Rating Curve= 0 ,0
Exp/Cntr(USF)=0,0
Exp/Cntr=0.5,0.3

Type RM Length L Ch R = 3 ,21368   ,,,
BEGIN DESCRIPTION:
Unnamed Road
Survey ID: 54075STA100
Deck information taken from LIDAR
Opening information taken from Survey
END DESCRIPTION:
Bridge Culvert--1,0,-1,-1, 0
Deck Dist Width WeirC Skew NumUp NumDn MinLoCord MaxHiCord MaxSubmerge Is_Ogee
14,13,2.6,0, 110, 110, , , 0.98, 0, 0,0,,
   151.4   152.4   152.7   153.3   155.7   156.9   158.7   160.6   161.4   161.6
   165.9   167.6   169.9   173.5   174.9   179.1   179.4   188.4   192.9   194.3
   197.1   197.4   197.6   200.4   201.9   203.2   205.6   206.1   206.4   209.1
   213.9   217.6   217.9   220.1   220.9   222.2   223.8   224.7   226.8   227.8
   229.3   230.5     232  255.16  284.58  297.83  307.47  340.66   350.7  380.78
   382.6   384.8   385.5     387   388.5   389.3   391.5   391.8   393.7   394.5
   395.9   397.5   398.2   400.4   404.8   406.4   407.2   409.4   409.6   411.7
   412.3   413.7   415.3   416.1   416.5   418.2   420.5   421.4   424.8   427.6
   430.6   432.7   433.4   433.7   434.5   436.8   439.9     442   442.9   445.1
     446   447.2   449.1   450.7   452.2   454.4     455   455.8   458.3   459.3
   461.4   461.7   463.6   464.4   466.5   467.5   467.9   470.6   472.2   473.7
 2396.85 2396.83 2396.82 2396.81 2396.79  2396.8 2396.75 2396.66 2396.64 2396.62
 2396.34 2396.27 2396.18 2396.03 2395.99 2395.83 2395.82 2395.66 2395.48 2395.44
 2395.38 2395.38 2395.37  2395.3 2395.27 2395.25 2395.23 2395.22 2395.22 2395.16
 2395.12 2395.05 2395.05 2395.02 2395.01 2395.01 2395.02 2395.02 2395.03 2395.03
 2395.04 2395.05 2395.21 2395.31 2394.78 2394.92 2394.92 2394.81 2395.46 2396.21
 2396.21 2396.23 2396.25 2396.26 2396.31 2396.32 2396.37 2396.38  2396.4 2396.41
  2396.4 2396.42 2396.43 2396.44 2396.44 2396.47 2396.49 2396.62 2396.63 2396.74
 2396.77 2396.82 2396.89 2396.92 2396.94 2397.03 2397.12 2397.16 2397.28 2397.36
  2397.4 2397.41 2397.41 2397.42 2397.44 2397.52 2397.59 2397.61 2397.63 2397.68
 2397.72 2397.75 2397.81 2397.88 2397.88 2397.98    2398    2398 2397.98 2398.01
 2397.98 2397.99    2398 2398.01 2397.89 2397.83 2397.82 2397.98 2397.93 2398.13
                                                                                
                                                                                
                                                                                
                                                                                
                                         2392.55 2392.55 2392.71
                                                                                
                                                                                
                                                                                
                                                                                
                                                                                
                                                                                
   151.4   152.4   152.7   153.3   155.7   156.9   158.7   160.6   161.4   161.6
   165.9   167.6   169.9   173.5   174.9   179.1   179.4   188.4   192.9   194.3
   197.1   197.4   197.6   200.4   201.9   203.2   205.6   206.1   206.4   209.1
   213.9   217.6   217.9   220.1   220.9   222.2   223.8   224.7   226.8   227.8
   229.3   230.5     232  255.16  284.58  292.83  300.47  333.66   350.7  380.78
   382.6   384.8   385.5     387   388.5   389.3   391.5   391.8   393.7   394.5
   395.9   397.5   398.2   400.4   404.8   406.4   407.2   409.4   409.6   411.7
   412.3   413.7   415.3   416.1   416.5   418.2   420.5   421.4   424.8   427.6
   430.6   432.7   433.4   433.7   434.5   436.8   439.9     442   442.9   445.1
     446   447.2   449.1   450.7   452.2   454.4     455   455.8   458.3   459.3
   461.4   461.7   463.6   464.4   466.5   467.5   467.9   470.6   472.2   473.7
 2396.85 2396.83 2396.82 2396.81 2396.79  2396.8 2396.75 2396.66 2396.64 2396.62
 2396.34 2396.27 2396.18 2396.03 2395.99 2395.83 2395.82 2395.66 2395.48 2395.44
 2395.38 2395.38 2395.37  2395.3 2395.27 2395.25 2395.23 2395.22 2395.22 2395.16
 2395.12 2395.05 2395.05 2395.02 2395.01 2395.01 2395.02 2395.02 2395.03 2395.03
 2395.04 2395.05 2395.21 2395.31 2394.78 2394.92 2394.92 2394.81 2395.46 2396.21
 2396.21 2396.23 2396.25 2396.26 2396.31 2396.32 2396.37 2396.38  2396.4 2396.41
  2396.4 2396.42 2396.43 2396.44 2396.44 2396.47 2396.49 2396.62 2396.63 2396.74
 2396.77 2396.82 2396.89 2396.92 2396.94 2397.03 2397.12 2397.16 2397.28 2397.36
  2397.4 2397.41 2397.41 2397.42 2397.44 2397.52 2397.59 2397.61 2397.63 2397.68
 2397.72 2397.75 2397.81 2397.88 2397.88 2397.98    2398    2398 2397.98 2398.01
 2397.98 2397.99    2398 2398.01 2397.89 2397.83 2397.82 2397.98 2397.93 2398.13
                                                                                
                                                                                
                                                                                
                                                                                
                                         2392.55 2392.55 2392.71
                                                                                
                                                                                
                                                                                
                                                                                
                                                                                
                                                                                
BR Coef=-1 ,-1 , 0 ,, 0 ,,,0.8,0,1.2,0,
WSPro=,,,, 1 ,,,, 0 ,,,, 0 ,,,,-1 ,-1 ,-1 , 0 , 0 , 0 , 0 , 0
BR U #Sta/Elev= 30
       0 2414.55      33 2415.29    44.5 2412.49    64.8 2402.93    78.1  2401.8
    93.2 2398.52    99.7 2398.48   111.3 2400.23   140.3  2399.8   161.3 2397.05
   212.1 2395.48   286.4 2394.88   292.7 2394.08     297 2392.57  298.63    2391
   305.6 2385.91   309.9 2387.43   324.7 2388.34     337 2391.68   346.2 2395.06
   391.8 2395.69   410.7 2397.31   445.9 2398.26   495.7 2399.15   545.3 2398.69
   571.9 2398.88   603.7 2400.82   612.9 2403.42   638.4 2413.12   658.7  2422.3
BR U #Mann= 8
       0     .05   111.3    .016   140.3     .05  298.63     .04     337     .05
   410.7    .016   445.9     .05   545.3      .1
BR U Banks=298.63,337
BR D #Sta/Elev= 30
       0 2414.74    14.8 2414.57    22.1 2413.33    31.9 2409.39    43.3 2402.35
    59.3 2399.79    69.9 2396.54      80 2396.51    91.2 2398.77   101.9 2399.23
   125.8 2398.66     196 2394.54     275 2394.29     289 2391.94  298.23 2388.64
  302.68 2385.91  320.67 2387.59   328.5 2388.43   342.4 2393.41   365.9 2393.33
   412.5 2395.88   442.4 2397.11   497.9 2399.81   503.8 2400.14   529.6 2400.53
   584.2 2401.09     620 2408.69   641.5 2415.63   667.5 2419.03   687.3 2423.43
BR D #Mann= 10
       0     .05   101.9    .016   125.8     .05  298.23     .04  320.67     .05
   412.5    .016   442.4     .05   497.9    .016   503.8     .05   529.6      .1
BR D Banks=,320.67
BC Design=,, 0 ,, 0 ,,,,,,
BC Use User HTab Curves=0
BC User HTab FreeFlow(D)= 0

Type RM Length L Ch R = 1 ,21348   ,99.8,109.9,119.3
BEGIN DESCRIPTION:
Channel burned based on survey STA098BD
END DESCRIPTION:
XS GIS Cut Line= 6
2196012.54329107429777.7602512692195933.30846231429687.404744786
2195854.07363354429654.0427116232195745.64702576429601.219492449
2195659.46177343429549.786357989  2195417.587033429453.870512646
#Sta/Elev= 30
       0 2414.74    14.8 2414.57    22.1 2413.33    31.9 2409.39    43.3 2402.35
    59.3 2399.79    69.9 2396.54      80 2396.51    91.2 2398.77   101.9 2399.23
   125.8 2398.66     196 2394.54     275 2394.29     289 2391.94  298.23 2388.64
  302.68 2385.91   326.8 2388.19   326.8  2388.2   342.4 2393.41   365.9 2393.33
   412.5 2395.88   442.4 2397.11   497.9 2399.81   503.8 2400.14   529.6 2400.53
   584.2 2401.09     620 2408.69   641.5 2415.63   667.5 2419.03   687.3 2423.43
#Mann= 10 ,-1,0
       0     .05       0   101.9    .016       0   125.8     .05       0
  298.23    .045       0   326.8     .05       0   412.5    .016       0
   442.4     .05       0   497.9    .016       0   503.8     .05       0
   529.6      .1       0
#XS Ineff= 2 , 0
             287    2391     338          2391.2
Permanent Ineff=
       F       F
Bank Sta=298.23,326.8
XS Rating Curve= 0 ,0
Exp/Cntr(USF)=0,0
Exp/Cntr=0.5,0.3

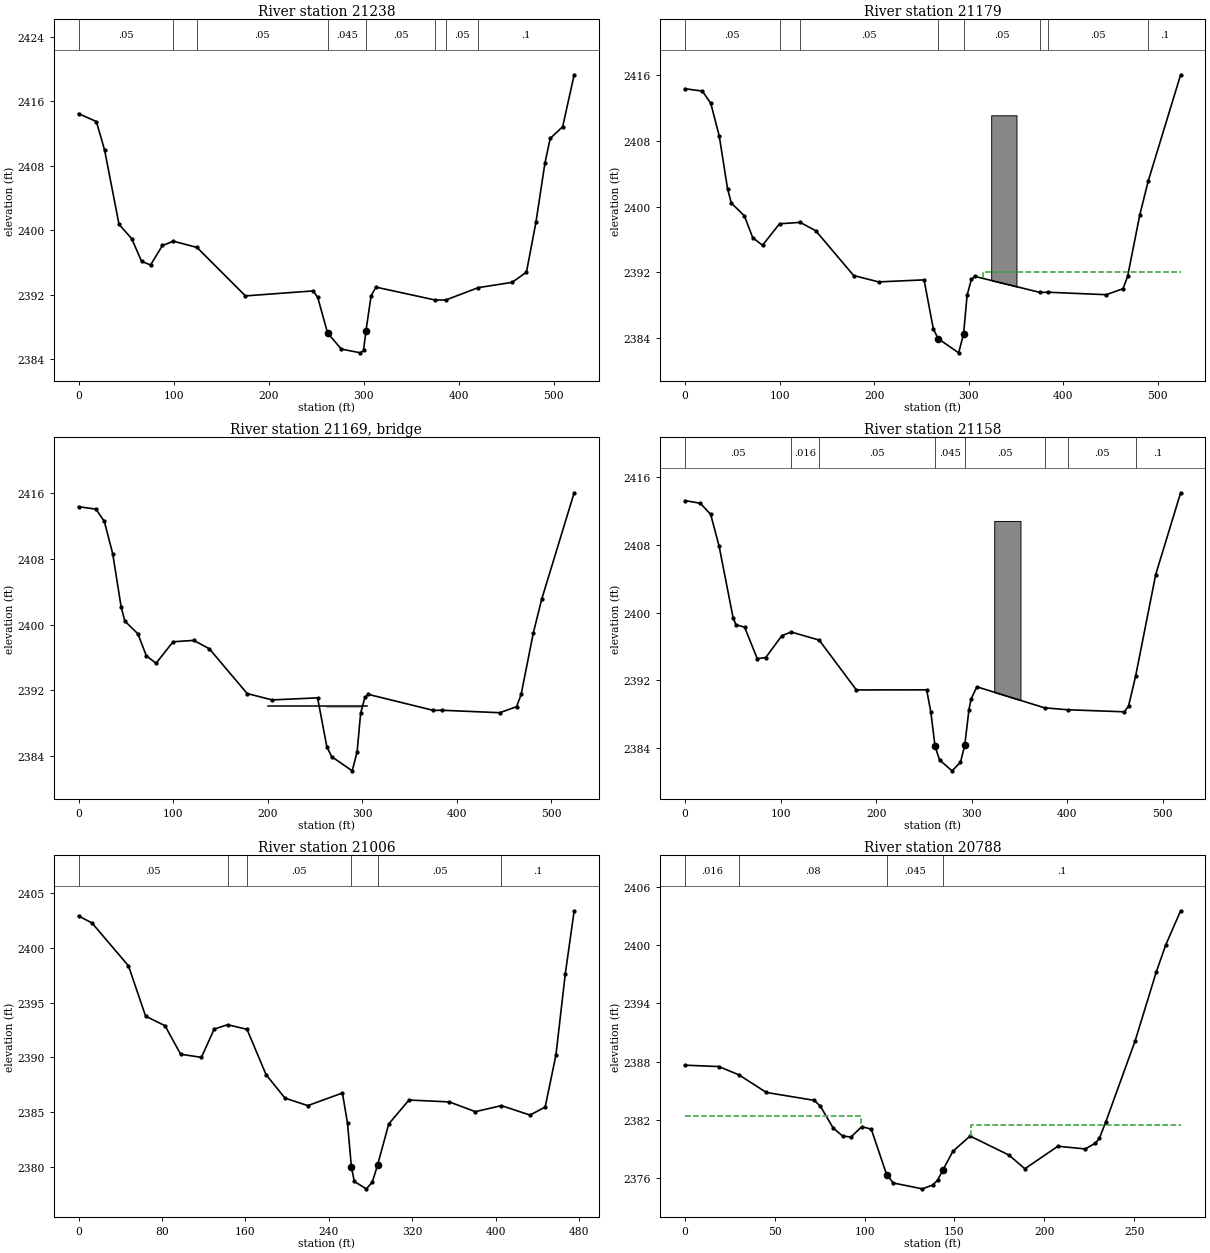
Type RM Length L Ch R = 1 ,21238   ,56.5,58.6,61.2
XS GIS Cut Line= 5
2196018.25715135429773.0752996552195958.45248346429679.193659492
  2195868.981891429576.5897690632195835.32781494429526.519070533
2195704.81566632429357.427859106
#Sta/Elev= 30
       0 2414.49    18.8  2413.5    27.5 2409.93    42.6 2400.74      56 2398.95
    66.3 2396.15    75.8 2395.69    88.3 2398.11    99.9 2398.64   124.6 2397.87
   175.6 2391.85   246.7 2392.47   251.6 2391.68     262 2387.25   276.4 2385.25
   296.6 2384.78   299.8 2385.08   302.4 2387.53   307.8 2391.87   312.9 2392.94
   375.2 2391.34   386.3 2391.34   420.6 2392.88     456 2393.53   471.2 2394.79
   481.3 2401.07   490.6 2408.31   496.2 2411.41   509.3 2412.86   521.4 2419.31
#Mann= 8 ,-1,0
       0     .05       0    99.9    .016       0   124.6     .05       0
     262    .045       0   302.4     .05       0   375.2    .016       0
   386.3     .05       0   420.6      .1       0
Bank Sta=262,302.4
XS Rating Curve= 0 ,0
Exp/Cntr(USF)=0,0
Exp/Cntr=0.5,0.3

Type RM Length L Ch R = 1 ,21179   ,21.3,21.3,21.6
XS GIS Cut Line= 3
2196025.05405351429777.760251269 2195913.8472763429547.006188559
2195795.69007551429306.521532843
#Sta/Elev= 30
       0 2414.37    18.4 2414.08    27.3 2412.58    36.2 2408.62      45 2402.19
      49 2400.42    62.8 2398.87    71.7 2396.19      82 2395.28     100  2397.9
   121.8 2398.07   138.3 2397.05   178.3 2391.59   204.7 2390.81   252.8 2391.06
   262.6 2385.08   267.7 2383.89   289.4 2382.16   294.6 2384.47   298.3 2389.18
   302.8 2391.11   306.6 2391.48   375.3 2389.53   384.3 2389.55   445.4 2389.25
   463.2 2389.98     468 2391.47     481 2399.03   489.9 2403.14   524.1 2416.07
#Mann= 8 ,-1,0
       0     .05       0     100    .016       0   121.8     .05       0
   267.7    .045       0   294.6     .05       0   375.3    .016       0
   384.3     .05       0   489.9      .1       0
#XS Ineff= 3 ,-1
       0     247    2388     308     315    2388     315     550    2392
Permanent Ineff=
       F       F       F
#Block Obstruct= 1 ,-1
  323.78  350.54 2411.13
Bank Sta=267.7,294.6
XS Rating Curve= 0 ,0
Exp/Cntr(USF)=0,0
Exp/Cntr=0.5,0.3

Type RM Length L Ch R = 3 ,21169   ,,,
BEGIN DESCRIPTION:
Unnamed road
Survey ID:54075STA090
Deck information taken from LIDAR
Opening information taken from Survey
END DESCRIPTION:
Bridge Culvert--1,0,-1,-1, 0
Deck Dist Width WeirC Skew NumUp NumDn MinLoCord MaxHiCord MaxSubmerge Is_Ogee
8,6,2.6,0, 2, 2, , , 0.98, 0, 0,0,,
     200     305
2390.0472390.047
2389.8172389.817
     200     305
2390.0472390.047
2389.8172389.817
BR Coef=-1 ,-1 , 0 ,, 0 ,,,0.8,0,1.2,0,
WSPro=,,,, 1 ,,,, 0 ,,,, 0 ,,,,-1 ,-1 ,-1 , 0 , 0 , 0 , 0 , 0
BR U #Sta/Elev= 30
       0 2414.37    18.4 2414.08    27.3 2412.58    36.2 2408.62      45 2402.19
      49 2400.42    62.8 2398.87    71.7 2396.19      82 2395.28     100  2397.9
   121.8 2398.07   138.3 2397.05   178.3 2391.59   204.7 2390.81   252.8 2391.06
   262.6 2385.08   267.7 2383.89   289.4 2382.16   294.6 2384.47   298.3 2389.18
   302.8 2391.11   306.6 2391.48   375.3 2389.53   384.3 2389.55   445.4 2389.25
   463.2 2389.98     468 2391.47     481 2399.03   489.9 2403.14   524.1 2416.07
BR U #Mann= 8
       0     .05     100    .016   121.8     .05   267.7     .04   294.6     .05
   375.3    .016   384.3     .05   489.9      .1
BR D #Sta/Elev= 30
       0 2413.21    16.1 2412.89    26.9 2411.58    35.7 2407.84    50.4 2399.37
    53.4 2398.56    62.4 2398.29    75.6 2394.57    84.5  2394.7   101.4 2397.28
   111.1 2397.71   140.4 2396.76   179.4 2390.88   252.9 2390.89   257.3 2388.26
   261.7 2384.23   266.4 2382.62   279.5 2381.34   288.3 2382.35   292.8 2384.38
   297.2 2388.57   299.5 2389.84   305.5 2391.25   376.3 2388.77     401 2388.54
   459.8  2388.3   464.2 2388.98   471.6 2392.51   492.6 2404.48   518.7 2414.13
BR D #Mann= 8
       0     .05   111.1    .016   140.4     .05   261.7     .04   292.8     .05
   376.3    .016     401     .05   471.6      .1
BC Design=,, 0 ,, 0 ,,,,,,
BC Use User HTab Curves=0
BC User HTab FreeFlow(D)= 0

Type RM Length L Ch R = 1 ,21158   ,155.3,152.3,148
XS GIS Cut Line= 3
 2196043.1251548429769.419742979 2195913.8472763 429498.35322353
2195823.49176981429299.571109267
#Sta/Elev= 30
       0 2413.21    16.1 2412.89    26.9 2411.58    35.7 2407.84    50.4 2399.37
    53.4 2398.56    62.4 2398.29    75.6 2394.57    84.5  2394.7   101.4 2397.28
   111.1 2397.71   140.4 2396.76   179.4 2390.88   252.9 2390.89   257.3 2388.26
   261.7 2384.23   266.4 2382.62   279.5 2381.34   288.3 2382.35   292.8 2384.38
   297.2 2388.57   299.5 2389.84   305.5 2391.25   376.3 2388.77     401 2388.54
   459.8  2388.3   464.2 2388.98   471.6 2392.51   492.6 2404.48   518.7 2414.13
#Mann= 8 ,-1,0
       0     .05       0   111.1    .016       0   140.4     .05       0
   261.7    .045       0   292.8     .05       0   376.3    .016       0
     401     .05       0   471.6      .1       0
#XS Ineff= 2 , 0
             249 2387.14     304         2387.14
Permanent Ineff=
       F       F
#Block Obstruct= 1 ,-1
  323.62   351.1 2410.81
Bank Sta=261.7,292.8
XS Rating Curve= 0 ,0
Exp/Cntr(USF)=0,0
Exp/Cntr=0.5,0.3

Type RM Length L Ch R = 1 ,21006   ,218.6,217.2,215.2
XS GIS Cut Line= 3
2196219.86961162429667.5163351532196048.95881079429439.240385332
2195942.32595469429282.162231898
#Sta/Elev= 30
       0 2402.89    12.9 2402.25    47.9 2398.34    64.3 2393.76    82.9 2392.89
    97.9 2390.29   117.8 2390.01     130 2392.58   142.8 2392.98   161.5 2392.56
   179.7 2388.44   197.8  2386.3   219.7 2385.61   252.9 2386.76   257.8    2384
   261.5 2380.04   264.3  2378.7   275.8 2378.03   281.5 2378.63   286.6  2380.2
   297.3 2383.94   316.7 2386.12   355.3 2385.95   380.3 2385.06   405.3 2385.61
   432.7 2384.75   447.2 2385.48   457.5  2390.2   466.5 2397.62     475 2403.36
#Mann= 6 ,-1,0
       0     .05       0   142.8    .016       0   161.5     .05       0
   261.5    .045       0   286.6     .05       0   405.3      .1       0
Bank Sta=261.5,286.6
XS Rating Curve= 0 ,0
Exp/Cntr(USF)=0,0
Exp/Cntr=0.3,0.1

Type RM Length L Ch R = 1 ,20788   ,215.3,212.8,208.6
XS GIS Cut Line= 3
2196316.35309582429419.3759665842196202.05724146429288.090187934
2196135.64208285429210.863259316
#Sta/Elev= 30
       0 2387.64    18.8  2387.5      30 2386.65    45.3 2384.83    71.9 2384.02
    75.4 2383.41    82.5 2381.16    87.8 2380.34    92.4 2380.24    98.4 2381.31
   103.7 2381.05   112.3 2376.34     116  2375.5   132.1  2374.9   137.8 2375.28
   140.6 2375.79   143.6 2376.85   149.1 2378.76   158.7 2380.34   180.3 2378.38
   189.2 2376.97   207.6 2379.29   222.8 2379.01   228.5 2379.61   230.7 2380.12
   234.2 2381.78   250.6 2390.16   262.3 2397.22   267.6 2400.03   275.9 2403.55
#Mann= 4 ,-1,0
       0    .016       0      30     .08       0   112.3    .045       0
   143.6      .1       0
#XS Ineff= 2 , 0
           98.02 2382.42  159.08         2381.47
Permanent Ineff=
       F       F
Bank Sta=112.3,143.6
XS Rating Curve= 0 ,0
Exp/Cntr(USF)=0,0
Exp/Cntr=0.3,0.1

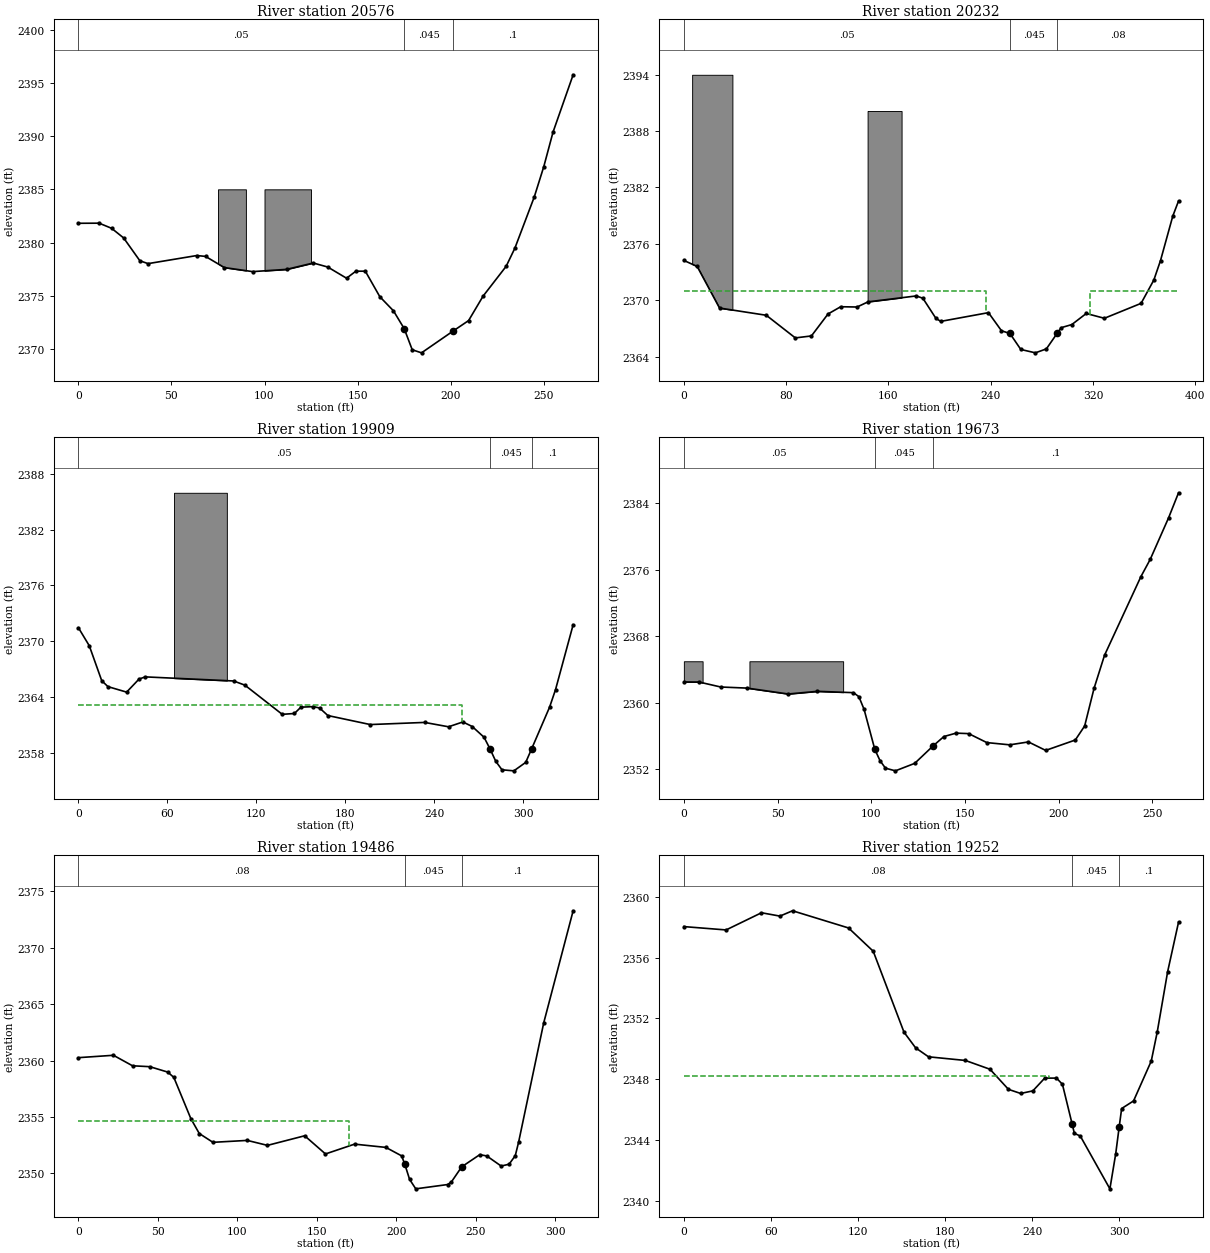
Type RM Length L Ch R = 1 ,20576   ,341.1,343.1,343.3
XS GIS Cut Line= 2
2196502.34256967429267.9757089812196291.64047866429105.834636395
#Sta/Elev= 30
       0 2381.81    11.1 2381.82    17.8 2381.34    24.3 2380.43      33 2378.29
    37.4 2378.02    63.6 2378.78    68.3  2378.7    78.4 2377.65    93.6 2377.27
   111.9 2377.48   126.2 2378.08     134  2377.7   144.1 2376.65   149.1 2377.31
   154.2 2377.31     162 2374.91   169.3 2373.59   175.1 2371.91   179.4 2369.93
   184.4 2369.64   201.4 2371.69   209.7 2372.67   217.5 2374.97   229.9 2377.77
   234.6 2379.48     245 2384.28   250.1 2387.12   255.1 2390.38   265.9 2395.76
#Mann= 3 ,-1,0
       0     .05       0   175.1    .045       0   201.4      .1       0
#Block Obstruct= 2 ,-1
      75      90    2385     100     125    2385
Bank Sta=175.1,201.4
XS Rating Curve= 0 ,0
Exp/Cntr(USF)=0,0
Exp/Cntr=0.3,0.1

Type RM Length L Ch R = 1 ,20232   ,307.6,323.9,340.3
XS GIS Cut Line= 4
2196737.95531617429030.0286616812196635.10494186428947.378697153
2196496.64999331428836.2600838912196437.43126048428786.298107683
#Sta/Elev= 30
       0 2374.23    10.4 2373.59    27.9 2369.16    64.5 2368.39    87.2 2365.98
    99.8 2366.19   112.8 2368.53   122.7  2369.3   135.5 2369.27   144.1 2369.82
   181.9 2370.45     187  2370.2   197.2 2368.06     201 2367.74   238.3 2368.67
   248.5 2366.74   255.1 2366.45   263.6 2364.75     275 2364.39   283.6 2364.81
   292.1 2366.48   295.2 2367.07   303.5  2367.4   314.8 2368.58     329 2368.07
   357.7 2369.66   367.7 2372.15   372.9 2374.22   382.5 2378.95     387 2380.56
#Mann= 3 ,-1,0
       0     .05       0   255.1    .045       0   292.1     .08       0
#XS Ineff= 2 , 0
          236.23 2370.99     318         2370.99
Permanent Ineff=
       F       F
#Block Obstruct= 2 ,-1
    6.48   37.98    2394  143.74  170.33 2390.14
Bank Sta=255.1,292.1
XS Rating Curve= 0 ,0
Exp/Cntr(USF)=0,0
Exp/Cntr=0.3,0.1

Type RM Length L Ch R = 1 ,19909   ,249.3,235.4,203.3
XS GIS Cut Line= 3
2196856.94159615428976.0933963172196788.98189896428764.491611903
2196779.71466753428653.284834693
#Sta/Elev= 30
       0 2371.44     7.3 2369.51    15.7 2365.75    19.9 2365.11    32.5 2364.52
    40.9 2365.93    45.1 2366.16   104.7 2365.72   112.3 2365.27   137.5 2362.13
   145.7 2362.22   150.1  2362.9   158.5 2362.96   162.7 2362.81   168.3    2362
   196.9 2361.03   233.6 2361.26   249.7 2360.79   259.4 2361.31   265.7 2360.82
   273.7 2359.66   277.8 2358.38   281.6 2357.07   285.8 2356.16   293.8 2356.05
   301.8 2356.96   305.8 2358.42   317.9  2362.9   321.9 2364.78   333.8 2371.77
#Mann= 3 ,-1,0
       0     .05       0   277.8    .045       0   305.8      .1       0
#XS Ineff= 2 , 0
          258.75 2363.13
Permanent Ineff=
       F       F
#Block Obstruct= 1 ,-1
   64.49  100.13 2385.97
Bank Sta=277.8,305.8
XS Rating Curve= 0 ,0
Exp/Cntr(USF)=0,0
Exp/Cntr=0.3,0.1

Type RM Length L Ch R = 1 ,19673   ,190.6,186.9,175.7
XS GIS Cut Line= 3
2197087.07784343428685.7201447132196978.96014336428596.136907516
2196880.10967473428521.999056042
#Sta/Elev= 30
       0 2362.51     8.1  2362.5    19.7  2361.9    33.7 2361.77    55.7 2361.06
    71.3 2361.38    90.5 2361.22    93.4 2360.74    96.2  2359.2   101.9  2354.4
   104.7 2353.03   107.6 2352.13   112.9 2351.81   123.2 2352.71   133.1 2354.83
   138.8 2355.94   145.3 2356.35     152 2356.29   161.7 2355.21   173.9 2354.94
   183.9 2355.29   193.1 2354.27   208.9 2355.52   213.9 2357.21   218.9 2361.73
   224.5 2365.72   243.9 2375.18   248.9 2377.27   258.7 2382.27     264 2385.28
#Mann= 3 ,-1,0
       0     .05       0   101.9    .045       0   133.1      .1       0
#Block Obstruct= 2 ,-1
       0      10    2365      35      85    2365
Bank Sta=101.9,133.1
XS Rating Curve= 0 ,0
Exp/Cntr(USF)=0,0
Exp/Cntr=0.3,0.1

Type RM Length L Ch R = 1 ,19486   ,199.7,233.8,248.9
XS GIS Cut Line= 3
2197256.97708639428583.7805989372197130.32492345428471.029283154
2197003.67276052428407.703201687
#Sta/Elev= 30
       0 2360.26      22 2360.47      34 2359.54    44.9 2359.46    56.2 2358.98
      60 2358.51    70.7 2354.86      76 2353.54    84.6 2352.76   106.2 2352.93
   118.9 2352.49   142.3 2353.34   155.4 2351.73   173.7  2352.6   193.4 2352.31
   203.3 2351.56   205.3 2350.82   208.3 2349.48   212.2 2348.64   232.2 2349.02
   234.6 2349.25   241.1 2350.59   252.5 2351.67   256.9 2351.55   265.9 2350.66
   270.9 2350.82   274.8 2351.58   276.9 2352.78   292.7 2363.35   311.2 2373.27
#Mann= 3 ,-1,0
       0     .08       0   205.3    .045       0   241.1      .1       0
#XS Ineff= 2 , 0
          170.19 2354.65
Permanent Ineff=
       F       F
Bank Sta=205.3,241.1
XS Rating Curve= 0 ,0
Exp/Cntr(USF)=0,0
Exp/Cntr=0.3,0.1

Type RM Length L Ch R = 1 ,19252   ,253.7,256.7,259.7
XS GIS Cut Line= 4
2197335.74855358 428579.146983222197292.50147355428466.395667437
2197253.88800924428355.188890227 2197233.8090078428254.793883024
#Sta/Elev= 30
       0 2358.04    29.1 2357.82    53.5 2358.95    66.2 2358.73    74.9 2359.08
   113.5 2357.95   130.5 2356.42   151.7  2351.1   159.7 2350.07   168.6 2349.48
     194 2349.24     211 2348.66   223.7 2347.34   232.1 2347.07   240.5 2347.24
   248.7 2348.08   256.8 2348.08   260.9 2347.67   267.6 2345.05   269.1 2344.45
   273.2 2344.27   293.6  2340.8   297.6  2343.1     300 2344.87   301.7 2346.08
   309.9 2346.58   322.1  2349.2   326.2  2351.1   333.4 2355.08   340.9 2358.33
#Mann= 3 ,-1,0
       0     .08       0   267.6    .045       0     300      .1       0
#XS Ineff= 2 , 0
          251.43 2348.22
Permanent Ineff=
       F       F
Bank Sta=267.6,300
XS Rating Curve= 0 ,0
Exp/Cntr(USF)=0,0
Exp/Cntr=0.3,0.1

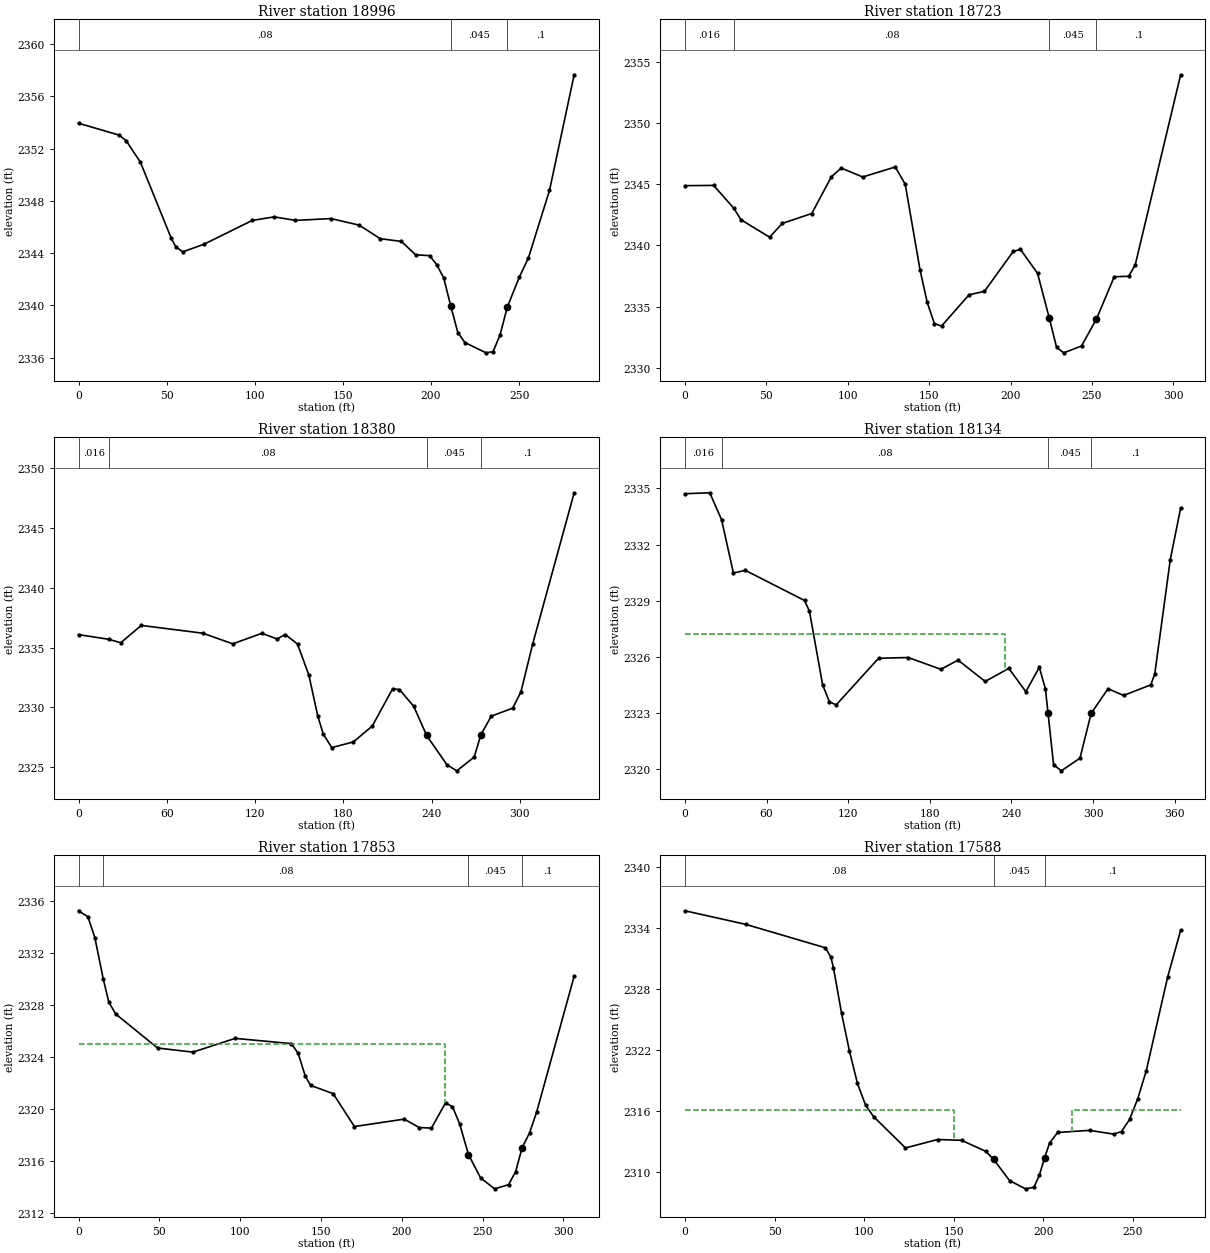
Type RM Length L Ch R = 1 ,18996   ,279.1,272.6,263
XS GIS Cut Line= 2
2197494.83602653428480.2965145882197488.65787224428199.190494419
#Sta/Elev= 30
       0 2353.94    23.1 2353.03    27.1 2352.59    35.1 2350.96    52.6 2345.14
    55.1  2344.5    59.1 2344.09    71.1 2344.67    98.6  2346.5   111.1 2346.77
   123.1  2346.5   143.2 2346.64   159.2 2346.14   171.2  2345.1   183.2 2344.89
   191.2 2343.87   199.2  2343.8   203.2 2343.12   207.2 2342.09   211.2 2339.94
   215.2 2337.91   219.2 2337.15   231.2 2336.36   235.2 2336.45   239.2 2337.75
   243.2 2339.84     250 2342.13   255.2 2343.61   267.2 2348.79   281.2 2357.65
#Mann= 3 ,-1,0
       0     .08       0   211.2    .045       0   243.2      .1       0
Bank Sta=211.2,243.2
XS Rating Curve= 0 ,0
Exp/Cntr(USF)=0,0
Exp/Cntr=0.3,0.1

Type RM Length L Ch R = 1 ,18723   ,344.9,343.6,341.6
XS GIS Cut Line= 3
2197848.14092218428412.4880368792197768.44343435428238.401043489
2197719.75435024428136.370744232
#Sta/Elev= 30
       0  2344.9    17.6 2344.92      30 2343.05    34.4 2342.11      52 2340.68
    59.8 2341.81    77.9 2342.62      90 2345.64      96 2346.34   109.2 2345.61
   129.2 2346.43   135.3 2345.02   144.4    2338   148.8 2335.35   153.2 2333.61
   157.6  2333.4   174.5 2335.96     184 2336.25   201.7 2339.52   206.1 2339.68
   216.6 2337.72   223.8 2334.06   228.3 2331.65   232.7 2331.21   243.6 2331.77
   252.8 2333.98   263.7 2337.44   272.6 2337.48   276.6 2338.41   304.5 2353.98
#Mann= 4 ,-1,0
       0    .016       0      30     .08       0   223.8    .045       0
   252.8      .1       0
Bank Sta=223.8,252.8
XS Rating Curve= 0 ,0
Exp/Cntr(USF)=0,0
Exp/Cntr=0.3,0.1

Type RM Length L Ch R = 1 ,18380   ,247.3,245.2,242.3
XS GIS Cut Line= 2
2198174.43299837428250.1602673062198006.07829398 427958.24247713
#Sta/Elev= 30
       0 2336.09    20.5  2335.7    28.7 2335.41    42.7 2336.86    84.4 2336.21
   104.9 2335.32   124.6  2336.2     135 2335.73   140.6  2336.1   148.9  2335.3
   156.6 2332.71   162.7 2329.27   166.4 2327.78   172.2 2326.64   186.9 2327.12
   199.7 2328.44   213.5 2331.55   218.2  2331.5   227.9  2330.1   236.7 2327.66
   236.7 2327.65   250.5 2325.21   257.2  2324.7     269 2325.85   273.6 2327.72
   280.6 2329.27   295.2 2329.94   300.8  2331.3   308.8 2335.31     337 2347.95
#Mann= 4 ,-1,0
       0    .016       0    20.5     .08       0   236.7    .045       0
   273.6      .1       0
Bank Sta=236.7,273.6
XS Rating Curve= 0 ,0
Exp/Cntr(USF)=0,0
Exp/Cntr=0.3,0.1

Type RM Length L Ch R = 1 ,18134   ,277.3,281.8,287.3
XS GIS Cut Line= 3
2198415.40704519428130.9400134032198365.35287673 428050.19640286
 2198205.0308619427833.725129924
#Sta/Elev= 30
       0 2334.72    18.2 2334.77    26.9 2333.33    35.6 2330.48    44.4 2330.62
    87.9 2329.01    91.5 2328.44   101.2  2324.5   106.2 2323.59   111.2 2323.43
   142.3 2325.92   164.2 2325.96   188.1 2325.33   200.8 2325.82   220.7 2324.68
   238.1 2325.38   250.6 2324.13   260.5 2325.44     265 2324.28   266.9 2322.99
     271 2320.23   276.7  2319.9   290.4 2320.58   298.6 2322.97     311 2324.29
   322.5 2323.93   342.5  2324.5   345.4 2325.09   356.8  2331.2   364.4 2333.95
#Mann= 4 ,-1,0
       0    .016       0    26.9     .08       0   266.9    .045       0
   298.6      .1       0
#XS Ineff= 2 , 0
             235 2327.24
Permanent Ineff=
       F       F
Bank Sta=266.9,298.6
XS Rating Curve= 0 ,0
Exp/Cntr(USF)=0,0
Exp/Cntr=0.3,0.1

Type RM Length L Ch R = 1 ,17853   ,265.6,264.6,262.9
XS GIS Cut Line= 2
2198606.90379863428018.4794814522198487.97432856 427735.82892271
#Sta/Elev= 30
       0 2335.25     5.8 2334.79    10.1 2333.19    15.3    2330    18.8 2328.19
    23.1 2327.29    48.9 2324.68    70.8 2324.36    96.9 2325.42   131.6 2325.02
   135.9 2324.28   140.3 2322.52   143.6  2321.8   157.6 2321.16   170.7 2318.63
   201.6  2319.2   210.8 2318.55   218.4 2318.51   227.1 2320.45   231.4 2320.16
   235.8 2318.85   241.3 2316.47   248.8 2314.67   257.5 2313.83   266.1 2314.15
   270.5 2315.16   274.5 2317.01   279.1 2318.14   283.5 2319.75   306.7 2330.21
#Mann= 4 ,-1,0
       0    .016       0    15.3     .08       0   241.3    .045       0
   274.5      .1       0
#XS Ineff= 2 , 0
             227    2325
Permanent Ineff=
       F       F
Bank Sta=241.3,274.5
XS Rating Curve= 0 ,0
Exp/Cntr(USF)=0,0
Exp/Cntr=0.3,0.1

Type RM Length L Ch R = 1 ,17588   ,225,234.1,240.7
XS GIS Cut Line= 2
2198823.11309542427831.4141547112198699.89334906427583.711551228
#Sta/Elev= 30
       0  2335.7    33.8 2334.37    78.4 2332.06    81.4 2331.16    82.9 2330.09
    87.4 2325.63    91.8 2321.92    96.3 2318.72   100.8 2316.59   105.3 2315.46
   123.1 2312.38     141 2313.21   154.4 2313.13   167.8 2312.06   172.3 2311.26
   181.2 2309.17   190.1 2308.36   194.8 2308.51   197.8 2309.69   200.8 2311.42
   203.5 2312.85     208  2313.9   225.9 2314.11   239.3 2313.74   243.7 2313.99
   248.2 2315.19   252.7 2317.19   257.5 2319.96   269.4 2329.15   276.7 2333.78
#Mann= 3 ,-1,0
       0     .08       0   172.3    .045       0   200.8      .1       0
#XS Ineff= 2 , 0
             150 2316.16  215.84         2316.16
Permanent Ineff=
       F       F
#Block Obstruct= 2 , 0
              10    2337
Bank Sta=172.3,200.8
XS Rating Curve= 0 ,0
Exp/Cntr(USF)=0,0
Exp/Cntr=0.3,0.1