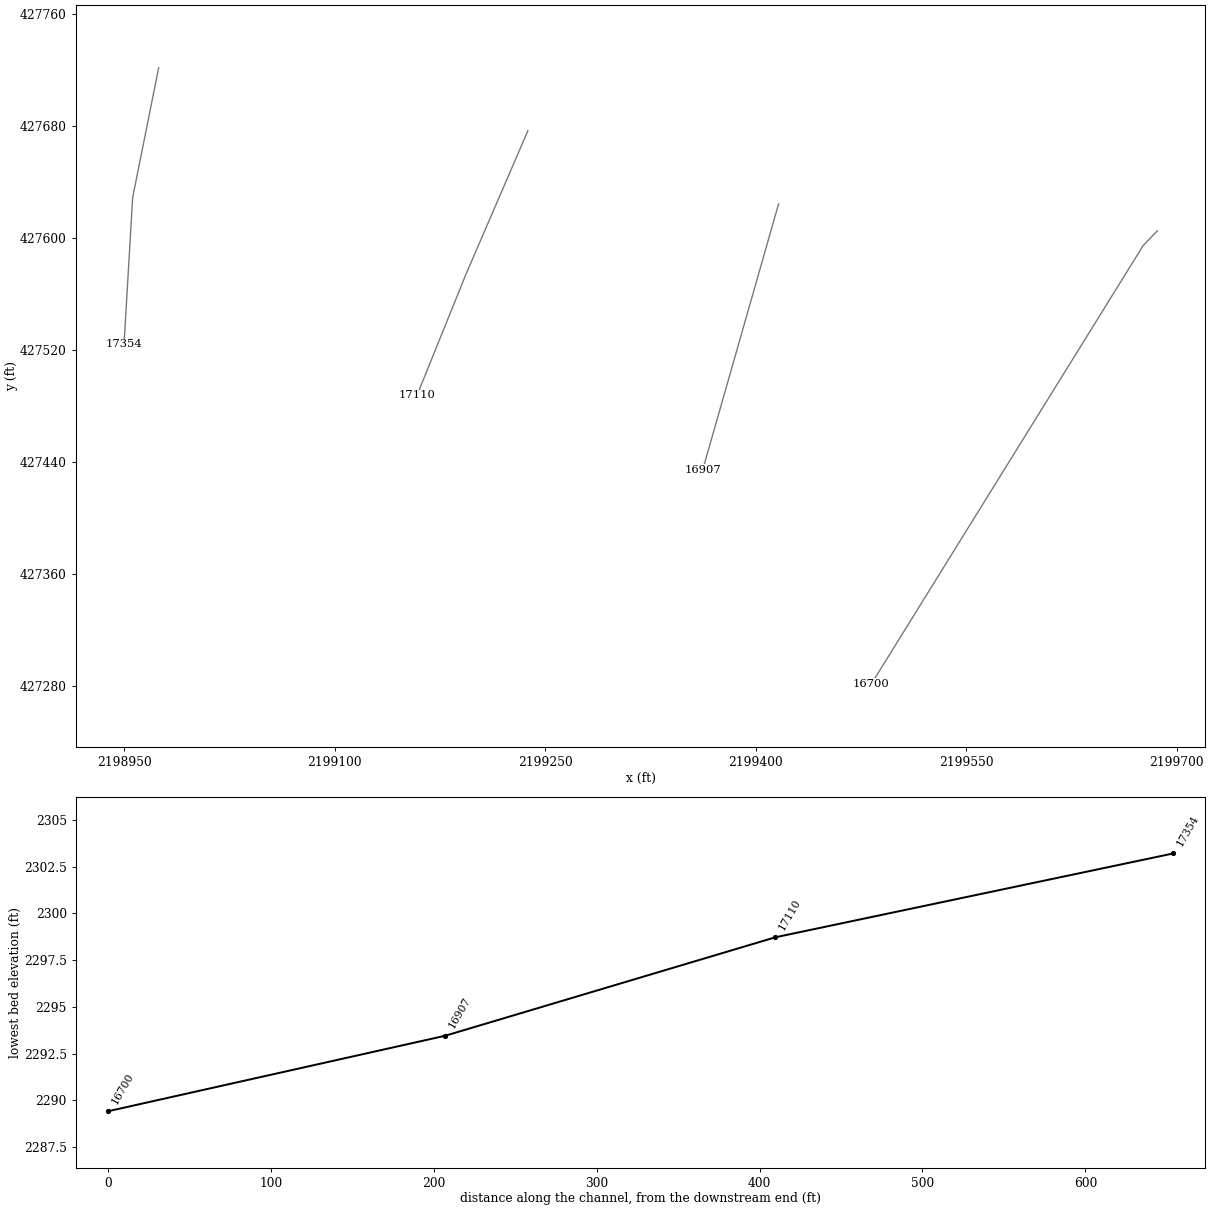
HEC-RAS study STMPNGCRK.prj: STMPNGCRK

--- STMPNGCRK.g01 (geometry) --- (continued)

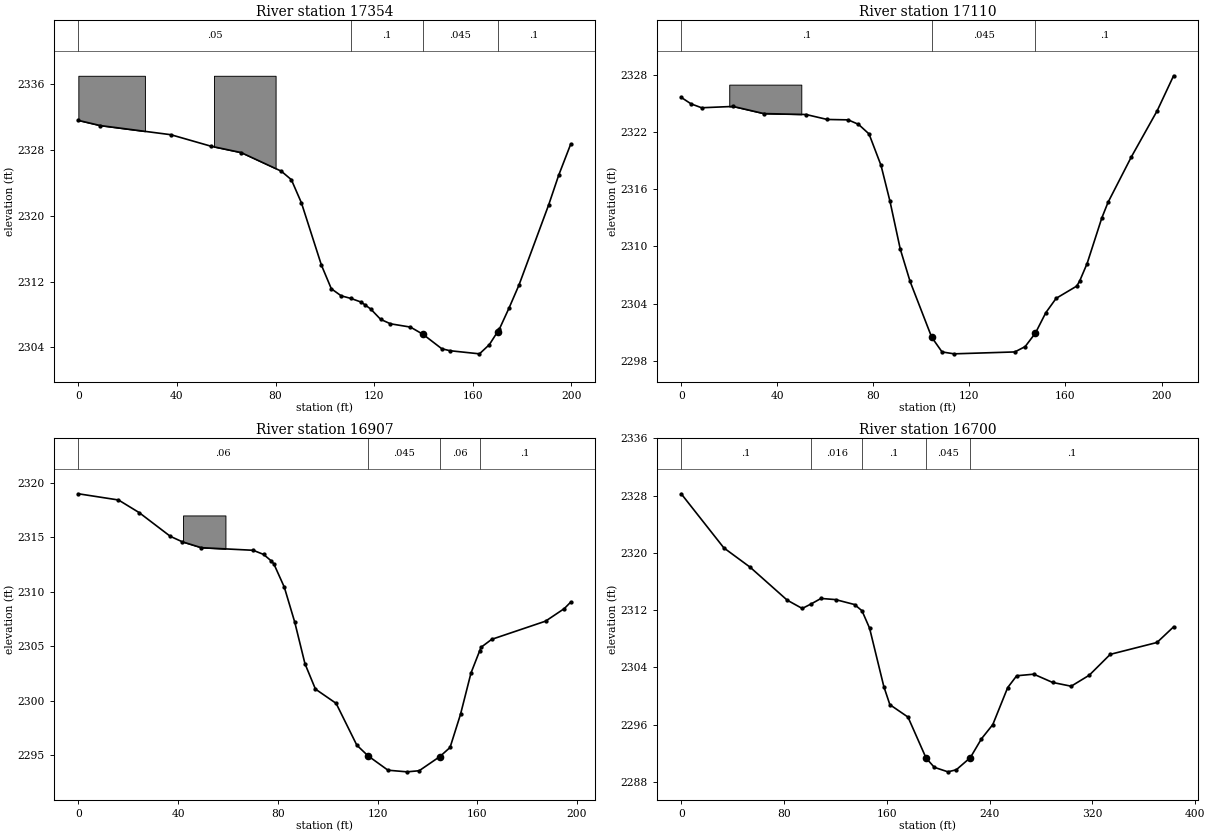
Type RM Length L Ch R = 1 ,17354   ,253.4,244.4,234.6
XS GIS Cut Line= 3
2198974.50397885427721.9280755592198955.96951599427629.255761217
 2198949.7913617427524.227138296
#Sta/Elev= 30
       0 2331.58     8.9 2330.95    37.5 2329.84    53.8 2328.44      66 2327.67
    82.3 2325.41    86.4 2324.37    90.5 2321.54    98.6 2313.98   102.6 2311.12
   106.6 2310.26   110.6 2309.94   114.6 2309.51   116.1  2309.2   118.6 2308.65
   122.6  2307.4   126.6 2306.86   134.7 2306.46   139.8 2305.58   147.4 2303.83
   150.7 2303.59   162.7 2303.21   166.7 2304.33   170.1 2305.92   170.7 2306.18
   174.7 2308.79   178.7 2311.56   190.8 2321.35   194.8  2324.9   199.7  2328.7
#Mann= 4 ,-1,0
       0     .05       0   110.6      .1       0   139.8    .045       0
   170.1      .1       0
#Block Obstruct= 2 ,-1
       0      27    2337      55      80    2337
Bank Sta=139.8,170.1
XS Rating Curve= 0 ,0
Exp/Cntr(USF)=0,0
Exp/Cntr=0.3,0.1

Type RM Length L Ch R = 1 ,17110   ,199.7,202.7,205.2
XS GIS Cut Line= 3
2199237.61368303427676.9901318682199193.52433733427574.449641217
2199158.59485672427487.803630844
#Sta/Elev= 30
       0 2325.66     4.1 2324.98     8.5 2324.57    21.6 2324.71    34.4 2323.96
      52 2323.86    60.8 2323.34    69.5  2323.3    73.8 2322.83    78.2 2321.82
    83.2 2318.51    86.9 2314.77    91.2 2309.73    95.3 2306.32   104.3 2300.46
   108.6 2298.92   113.6 2298.72   138.9 2298.92   143.2 2299.48   147.5 2300.91
   151.8 2303.04   156.1 2304.55   164.7 2305.84   165.9 2306.37     169 2308.21
   175.1 2312.98   177.7 2314.63   187.4  2319.4   198.2 2324.27     205 2327.93
#Mann= 3 ,-1,0
       0      .1       0   104.3    .045       0   147.5      .1       0
#Block Obstruct= 1 ,-1
      20      50    2327
Bank Sta=104.3,147.5
XS Rating Curve= 0 ,0
Exp/Cntr(USF)=0,0
Exp/Cntr=0.3,0.1

Type RM Length L Ch R = 1 ,16907   ,212.5,207,200.5
XS GIS Cut Line= 2
2199416.24201055  427624.62214552199362.18316052427434.643901099
#Sta/Elev= 30
       0 2318.99    16.1 2318.42    24.4 2317.26    36.9 2315.08    41.7 2314.58
    49.3 2314.04    70.1  2313.8    74.3 2313.42    77.3 2312.84    78.4 2312.56
    82.6 2310.42    86.8  2307.2    90.9 2303.38    95.1 2301.05   103.4 2299.74
   111.7  2295.9   116.2 2294.92   124.2  2293.6   131.8 2293.45   136.7 2293.55
     145 2294.85   149.1 2295.69   153.3 2298.74   157.5 2302.53     161 2304.58
   161.6  2304.9   165.8 2305.62   187.4 2307.29   194.9 2308.44   197.5 2309.04
#Mann= 4 ,-1,0
       0     .06       0   116.2    .045       0     145     .06       0
     161      .1       0
#Block Obstruct= 1 ,-1
      42      59    2317
Bank Sta=116.2,145
XS Rating Curve= 0 ,0
Exp/Cntr(USF)=0,0
Exp/Cntr=0.3,0.1

Type RM Length L Ch R = 1 ,16700   ,347.7,333.9,313
XS GIS Cut Line= 3
2199686.17556461427605.4467546942199675.96752259427594.731575645
2199482.30341619427281.399570784
#Sta/Elev= 30
       0 2328.25    33.2 2320.69    53.6    2318    82.5 2313.39    94.2 2312.23
   101.3 2312.88   108.8 2313.63   120.1 2313.47   134.9 2312.78   140.7 2311.91
   146.6 2309.48   157.7 2301.32   162.4 2298.79   176.5 2297.06   190.6 2291.33
     197 2290.04   207.6 2289.41   214.1  2289.7     225 2291.39   233.7 2294.03
   242.5 2296.01   254.1 2301.18   261.1 2302.83   274.4 2303.05     289  2301.9
   303.5 2301.37   317.6 2302.91   333.9 2305.82   370.3 2307.48   383.2 2309.66
#Mann= 5 ,-1,0
       0      .1       0   101.3    .016       0   140.7      .1       0
   190.6    .045       0     225      .1       0
Bank Sta=190.6,225
XS Rating Curve= 0 ,0
Exp/Cntr(USF)=0,0
Exp/Cntr=0.3,0.1