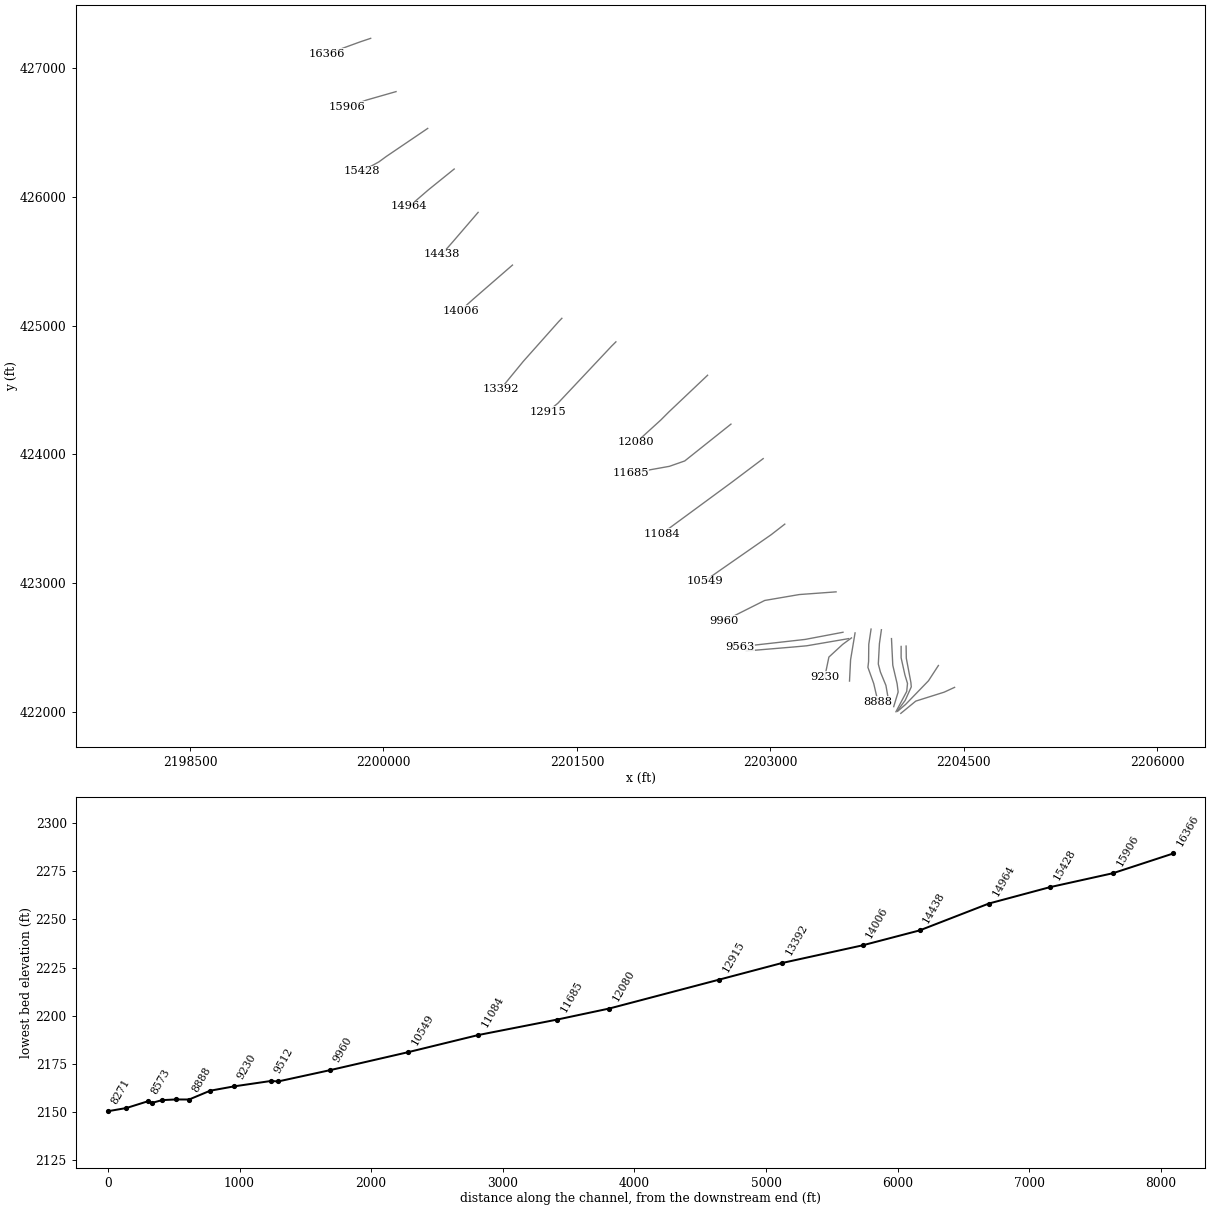
HEC-RAS study STMPNGCRK.prj: STMPNGCRK

--- STMPNGCRK.g01 (geometry) --- (continued)

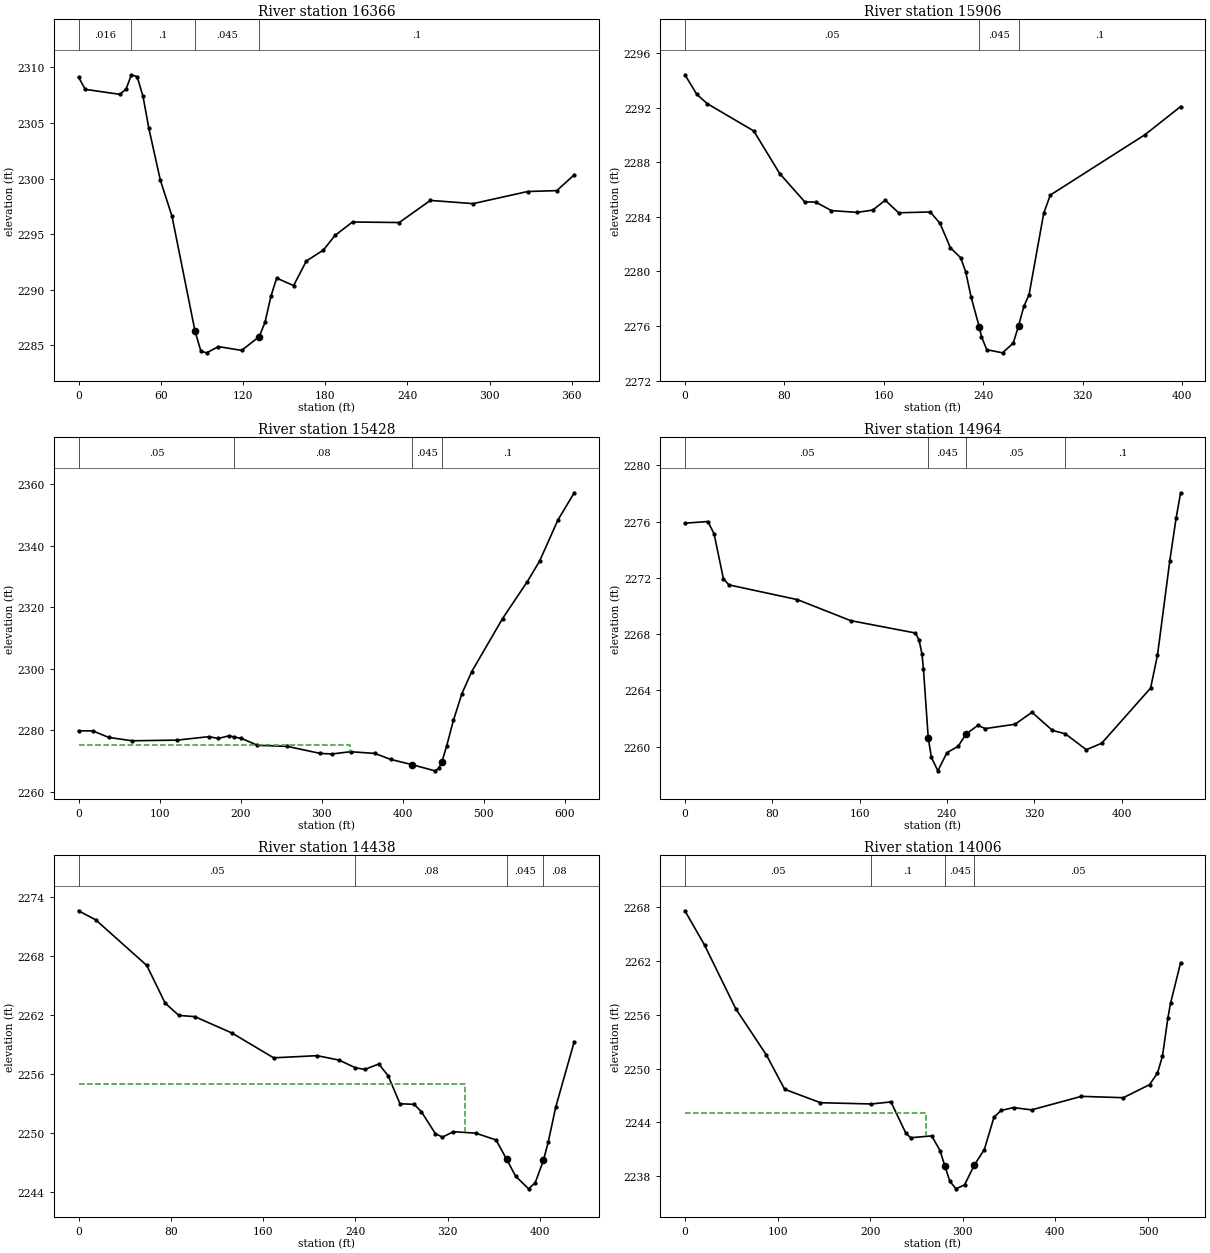
Type RM Length L Ch R = 1 ,16366   ,458.7,459.7,454.3
XS GIS Cut Line= 3
2199900.79477683427228.4477922812199818.78785058427200.927286654
2199560.21513968427106.469358519
#Sta/Elev= 30
       0 2309.12     4.9 2308.02    30.2 2307.57    34.7 2308.04    38.6 2309.33
    42.8 2309.15    47.1 2307.38    51.3 2304.53    59.7 2299.86    68.2 2296.62
      85 2286.29    89.3 2284.48    93.5 2284.32   102.1 2284.88   119.1 2284.54
   131.9 2285.78   136.1 2287.06   140.4 2289.39   144.6 2291.04     157 2290.37
   166.3 2292.58   178.8 2293.57   187.2 2294.88     200 2296.09   234.1 2296.04
   256.8 2298.03     288 2297.74   327.8 2298.83   349.1 2298.91   361.8 2300.33
#Mann= 4 ,-1,0
       0    .016       0    38.6      .1       0      85    .045       0
   131.9      .1       0
Bank Sta=85,131.9
XS Rating Curve= 0 ,0
Exp/Cntr(USF)=0,0
Exp/Cntr=0.3,0.1

Type RM Length L Ch R = 1 ,15906   ,467.6,479.1,484.1
XS GIS Cut Line= 4
2200097.45118355426815.0699091172199869.81948686426749.923122838
2199804.90242089426726.3216904942199717.12093839426696.074049976
#Sta/Elev= 30
       0 2294.42     9.6 2292.98      18  2292.3    55.4  2290.3    76.2 2287.18
    96.4  2285.1   105.3 2285.08   117.8 2284.46   138.6 2284.33   151.1  2284.5
   161.1 2285.22   171.9  2284.3   197.3 2284.36   205.2 2283.52   213.5 2281.74
   221.8    2281   225.8 2279.98   230.2 2278.11   236.8 2275.92   238.5 2275.22
   242.8 2274.26   255.5 2274.03   264.1 2274.75   268.3    2276   272.6 2277.43
   276.8  2278.3   288.6 2284.27   293.9  2285.6   370.1 2290.03   398.7 2292.09
#Mann= 3 ,-1,0
       0     .05       0   236.8    .045       0   268.3      .1       0
Bank Sta=236.8,268.3
XS Rating Curve= 0 ,0
Exp/Cntr(USF)=0,0
Exp/Cntr=0.3,0.1

Type RM Length L Ch R = 1 ,15428   ,430.5,463,421
XS GIS Cut Line= 4
2200342.96515397426529.5442976952200021.70113092426311.764358992
2199964.83626819426270.0273954772199830.69486554426196.208050746
#Sta/Elev= 30
       0 2279.82    17.9 2279.76    37.2 2277.66    66.2 2276.56   121.8 2276.78
   160.7  2277.9   172.5 2277.33     186 2278.19   192.4 2277.74     201 2277.37
   220.8 2275.08   257.3 2274.76   298.1 2272.46   312.6 2272.26   335.7    2273
   365.8 2272.45   385.1 2270.51411.1957 2268.83   439.8 2266.78   444.6 2267.59
448.48862269.691   454.5    2275   462.7 2283.21   473.1 2291.85   485.3 2299.07
   523.3 2316.31     554 2328.39     569    2335   591.8 2348.47   611.8 2357.26
#Mann= 4 ,-1,0
       0     .05       0   192.4     .08       0411.1957    .045       0
448.4886      .1       0
#XS Ineff= 2 , 0
          334.98 2275.11
Permanent Ineff=
       F       F
Bank Sta=411.1957,448.4886
XS Rating Curve= 0 ,0
Exp/Cntr(USF)=0,0
Exp/Cntr=0.3,0.1

Type RM Length L Ch R = 1 ,14964   ,520.8,526.6,467.8
XS GIS Cut Line= 3
2200548.38878409426214.4584289342200347.59876968426052.281878836
2200199.32306674 425924.08517733
#Sta/Elev= 30
       0 2275.88      21    2276    26.7 2275.13    35.2 2271.95    40.2  2271.5
   103.1 2270.45   151.8 2268.96   211.1 2268.08   214.4  2267.6   217.2 2266.58
   218.5 2265.52   222.9 2260.63   225.8 2259.24   231.7 2258.29     240 2259.58
   250.3 2260.03   257.4  2260.9   268.4 2261.52   275.1 2261.29   302.4  2261.6
   317.9 2262.45   336.7 2261.16   348.5 2260.92   367.7 2259.79   381.8 2260.25
   426.6 2264.17   432.9 2266.51   444.2 2273.22   449.9 2276.22   454.1 2278.04
#Mann= 4 ,-1,0
       0     .05       0   222.9    .045       0   257.4     .05       0
   348.5      .1       0
Bank Sta=222.9,257.4
XS Rating Curve= 0 ,0
Exp/Cntr(USF)=0,0
Exp/Cntr=0.3,0.1

Type RM Length L Ch R = 1 ,14438   ,434.6,432.1,429.1
XS GIS Cut Line= 3
2200733.89418333  425878.10933372200531.83983015425642.941852249
2200452.40173897 425553.18073402
#Sta/Elev= 30
       0 2272.59    14.9 2271.67    59.2 2267.03    75.1 2263.21      87 2261.95
   100.8 2261.83   133.1 2260.16   169.2 2257.64   206.9 2257.86     226 2257.41
   240.1 2256.63   248.2 2256.46   260.4 2257.01   268.5 2255.82   278.8 2252.97
   291.1 2252.91   297.3 2252.17   309.5 2249.93   315.6 2249.58   325.2 2250.13
   344.5 2249.98   362.1 2249.29   371.2 2247.34   379.1  2245.6   390.4 2244.32
   396.1 2244.95   403.2 2247.22   407.4  2249.1   413.9 2252.65   429.9 2259.28
#Mann= 4 ,-1,0
       0     .05       0   240.1     .08       0   371.2    .045       0
   403.2     .08       0
#XS Ineff= 2 , 0
             335    2255
Permanent Ineff=
       F       F
Bank Sta=371.2,403.2
XS Rating Curve= 0 ,0
Exp/Cntr(USF)=0,0
Exp/Cntr=0.3,0.1

Type RM Length L Ch R = 1 ,14006   ,609.1,613.6,616.7
XS GIS Cut Line= 4
2201000.17216886425469.1775147672200805.07607036425299.709746379
2200693.57540989425202.7856640372200597.60127865425116.428981785
#Sta/Elev= 30
       0 2267.62    21.2 2263.79    54.9 2256.68    87.9 2251.54   107.7  2247.7
   146.4  2246.2   201.3 2246.06   222.5 2246.29   238.4 2242.84   243.7 2242.29
   266.5  2242.5   275.5 2240.85   280.7 2239.14   286.1 2237.43   292.8 2236.59
     302 2237.04   312.6 2239.26   323.3 2240.97   333.8  2244.6   341.5 2245.34
     355 2245.66   374.3  2245.4   428.1 2246.91   473.4 2246.76   501.8 2248.22
   510.3 2249.51   515.7  2251.4   521.6  2255.7   524.4  2257.3   535.3 2261.83
#Mann= 4 ,-1,0
       0     .05       0   201.3      .1       0   280.7    .045       0
   312.6     .05       0
#XS Ineff= 2 , 0
             260    2245
Permanent Ineff=
       F       F
Bank Sta=280.7,312.6
XS Rating Curve= 0 ,0
Exp/Cntr(USF)=0,0
Exp/Cntr=0.3,0.1

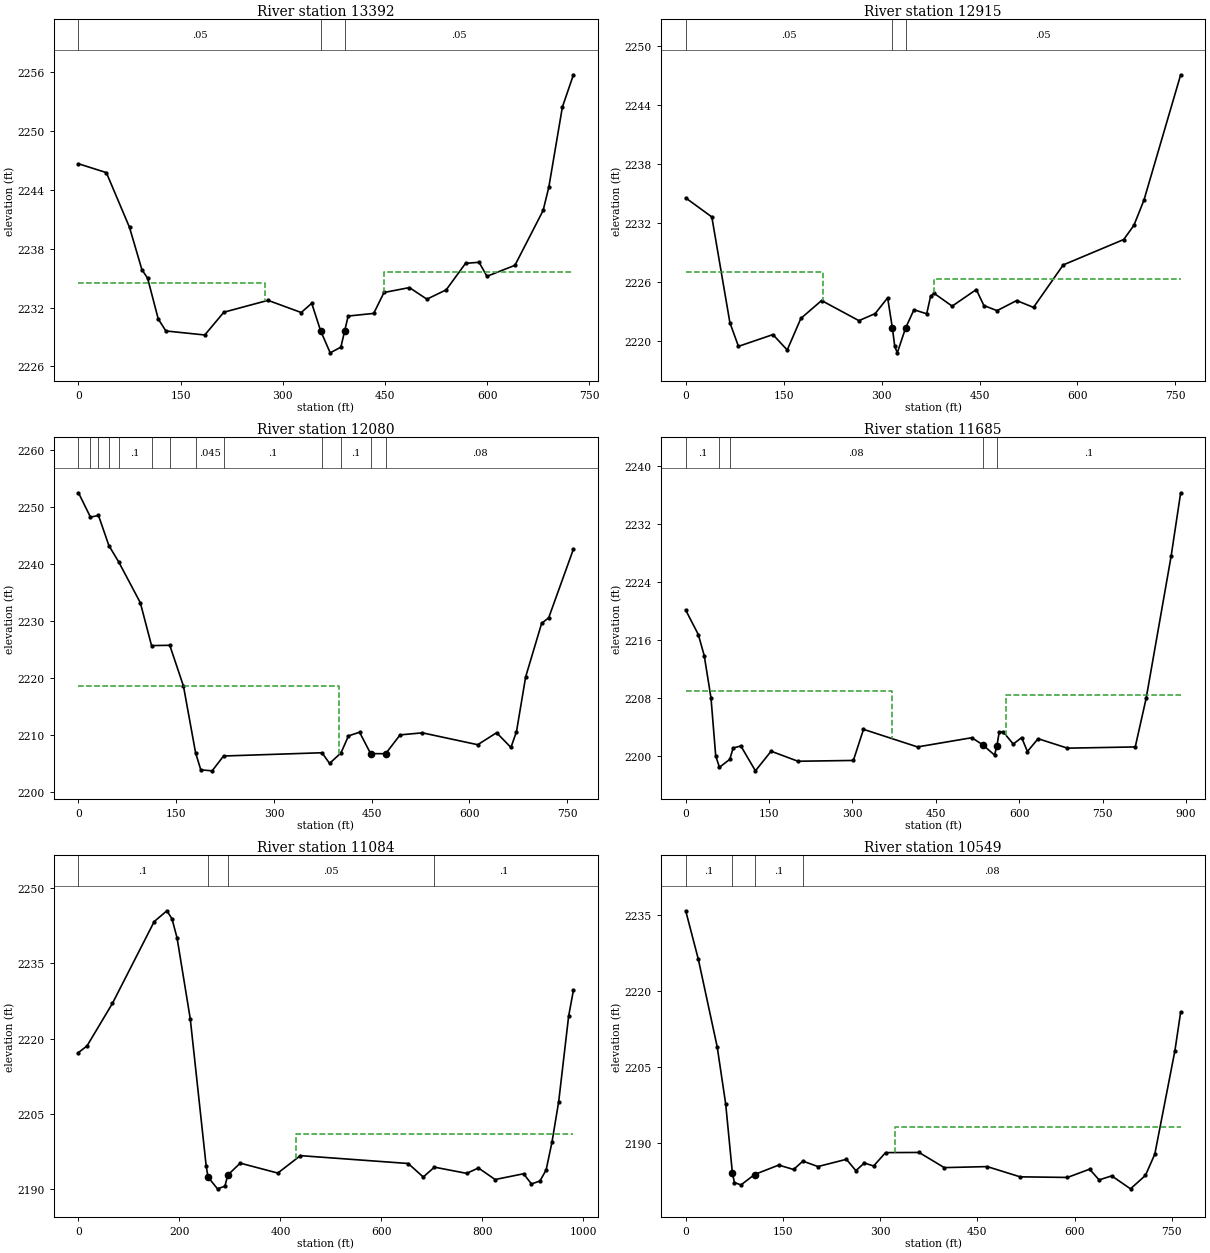
Type RM Length L Ch R = 1 ,13392   ,465.2,477.2,479.6
XS GIS Cut Line= 4
2201383.07717216425056.0424907522201358.63363873425030.710716488
2201083.92365021424721.8689949082200907.70341309424506.745446854
#Sta/Elev= 30
       0 2246.65    40.9 2245.75    74.9 2240.17    93.1 2235.86   101.5 2234.98
   117.1 2230.83   128.3 2229.61   185.4  2229.2   213.4 2231.52   278.2 2232.73
     327 2231.49   342.4 2232.43   355.4 2229.64   369.5 2227.38   385.2 2227.96
   390.6 2229.57   395.9 2231.13   433.4  2231.4   448.5 2233.53   485.8 2234.03
   511.5 2232.85   539.8  2233.8   568.2  2236.5   588.1 2236.61   599.6 2235.18
   640.7  2236.3   682.1 2241.89   690.5 2244.28   710.4 2252.44   726.6 2255.72
#Mann= 3 ,-1,0
       0     .05       0   355.4    .045       0   390.6     .05       0
#XS Ineff= 2 , 0
          274.48  2234.5  448.45          2235.6
Permanent Ineff=
       F       F
Bank Sta=355.4,390.6
XS Rating Curve= 0 ,0
Exp/Cntr(USF)=0,0
Exp/Cntr=0.3,0.1

Type RM Length L Ch R = 1 ,12915   ,835.9,834.5,834.6
XS GIS Cut Line= 4
2201802.13454649424873.4001795912201768.45292955 424839.91435609
2201351.61324179424396.4240245812201272.45886425424332.103105742
#Sta/Elev= 30
       0 2234.54      40  2232.6    67.7 2221.82    80.8 2219.41   133.6 2220.61
   155.5 2219.04   176.4 2222.26   208.1 2224.08   265.3 2222.03   290.2 2222.75
   309.3 2224.36   316.6 2221.26   320.2  2219.4   324.1 2218.75   336.7 2221.27
   349.6 2223.14   369.1 2222.73   375.1 2224.51   380.6 2224.81   408.1 2223.51
   445.1  2225.2   456.7 2223.57   476.9 2223.05   506.9 2224.08   532.7 2223.38
   578.2 2227.71   670.9  2230.3   686.5 2231.75   701.8  2234.3   758.1 2247.09
#Mann= 3 ,-1,0
       0     .05       0   316.6    .045       0   336.7     .05       0
#XS Ineff= 2 , 0
          210.03 2226.96  380.39          2226.3
Permanent Ineff=
       F       F
Bank Sta=316.6,336.7
XS Rating Curve= 0 ,0
Exp/Cntr(USF)=0,0
Exp/Cntr=0.3,0.1

Type RM Length L Ch R = 1 ,12080   ,385.7,395,390.5
XS GIS Cut Line= 4
2202513.04184813424614.3164679672202214.94590367424331.665909225
2202150.07528363424266.7952891862201960.09703923424093.806969081
#Sta/Elev= 30
       0 2252.48    18.4 2248.21    30.7 2248.51    46.7 2243.22    61.8 2240.35
    94.9 2233.21   112.1  2225.7   140.1 2225.75   161.1  2218.6   179.7 2206.91
   187.7 2203.92   205.1 2203.75   222.6 2206.35   373.7 2206.92   385.3 2205.05
   402.8 2206.89   414.3 2209.87   431.3 2210.52   448.3 2206.77   471.3 2206.75
   493.5 2210.05   527.7 2210.41   612.6 2208.33   641.6 2210.43   663.6 2207.85
   672.1 2210.62   686.2 2220.23   710.7  2229.6   721.5 2230.57   759.5 2242.61
#Mann= 13 ,-1,0
       0      .1       0    18.4    .016       0    30.7      .1       0
    46.7    .016       0    61.8      .1       0   112.1    .016       0
   140.1      .1       0   179.7    .045       0   222.6      .1       0
   373.7    .045       0   402.8      .1       0   448.3    .045       0
   471.3     .08       0
#XS Ineff= 2 , 0
          399.31 2218.59
Permanent Ineff=
       F       F
Bank Sta=448.3,471.3
XS Rating Curve= 0 ,0
Exp/Cntr(USF)=0,0
Exp/Cntr=0.3,0.1

Type RM Length L Ch R = 1 ,11685   ,442.6,600.1,543.7
XS GIS Cut Line= 4
2202694.18933049424235.051219614 2202335.8563817423949.311583726
2202216.92691163423907.6090422732201915.74189002 423853.55019224
#Sta/Elev= 30
       0 2220.14    22.7 2216.77    33.3 2213.88    45.5 2208.05      54 2200.06
    60.7 2198.51    79.3  2199.6    85.3 2201.16    99.2 2201.44   125.4 2198.02
   153.6 2200.72   201.9 2199.34   301.6 2199.45   319.8 2203.73     417 2201.31
   514.7 2202.58   534.3  2201.6   555.5 2200.19   559.7 2201.43   563.9 2203.35
   571.1 2203.38   589.2  2201.7   604.3  2202.6   614.6 2200.68   633.9 2202.44
   686.7 2201.14   808.6 2201.31   828.3 2208.03   873.1 2227.54   890.3 2236.28
#Mann= 5 ,-1,0
       0      .1       0    60.7    .045       0    79.3     .08       0
   534.3    .045       0   559.7      .1       0
#XS Ineff= 2 , 0
          371.77 2209.02  576.59         2208.41
Permanent Ineff=
       F       F
Bank Sta=534.3,559.7
XS Rating Curve= 0 ,0
Exp/Cntr(USF)=0,0
Exp/Cntr=0.3,0.1

Type RM Length L Ch R = 1 ,11084   ,533.3,536,509.7
XS GIS Cut Line= 3
2202944.07004607423967.3613801472202697.30529982423781.501269749
2202156.56234563423383.937041224
#Sta/Elev= 30
       0  2217.2    16.9 2218.52    67.2 2227.01     150 2243.36   175.1 2245.51
   185.2 2243.89   195.2  2240.1   221.4  2223.9   252.8  2194.6256.44172192.335
   275.3 2189.98     290 2190.51295.52542192.724   320.3 2195.11   394.7 2193.13
   439.4 2196.61   652.9 2195.04   682.7 2192.34   704.8 2194.31   768.7 2193.07
   791.9 2194.15     825 2191.84   881.3 2192.99     897 2190.96   913.7 2191.54
     926 2193.74   937.5 2199.25   950.9  2207.4   970.6 2224.48   980.1 2229.65
#Mann= 4 ,-1,0
       0      .1       0256.4417    .045       0295.5254     .05       0
   704.8      .1       0
#XS Ineff= 2 , 0
                             430         2200.84
Permanent Ineff=
       F       F
Bank Sta=256.4417,295.5254
XS Rating Curve= 0 ,0
Exp/Cntr(USF)=0,0
Exp/Cntr=0.3,0.1

Type RM Length L Ch R = 1 ,10549   ,585.5,589.2,496.6
XS GIS Cut Line= 3
2203111.55054493 423459.001615842203005.90410658423376.986617648
2202488.79259255423016.954676431
#Sta/Elev= 30
       0 2235.91    19.5 2226.33    48.6 2209.05    61.7 2197.78    72.1 2184.08
    75.2 2182.28    85.3  2181.8   106.3 2183.86   143.5 2185.72   166.5 2184.85
   180.8  2186.5   204.1 2185.43     248 2186.86   262.6 2184.61   275.6 2186.13
     290 2185.54   308.4 2188.18   360.1 2188.21     399 2185.22   465.3 2185.42
     516  2183.4   589.1 2183.28   623.3 2184.91   637.9 2182.79   657.4 2183.59
   686.4 2181.03   709.5 2183.69   723.9 2187.89   754.9 2208.28   763.8 2215.92
#Mann= 4 ,-1,0
       0      .1       0    72.1    .045       0   106.3      .1       0
   180.8     .08       0
#XS Ineff= 2 , 0
                          322.99         2193.32
Permanent Ineff=
       F       F
Bank Sta=72.1,106.3
XS Rating Curve= 0 ,0
Exp/Cntr(USF)=0,0
Exp/Cntr=0.3,0.1

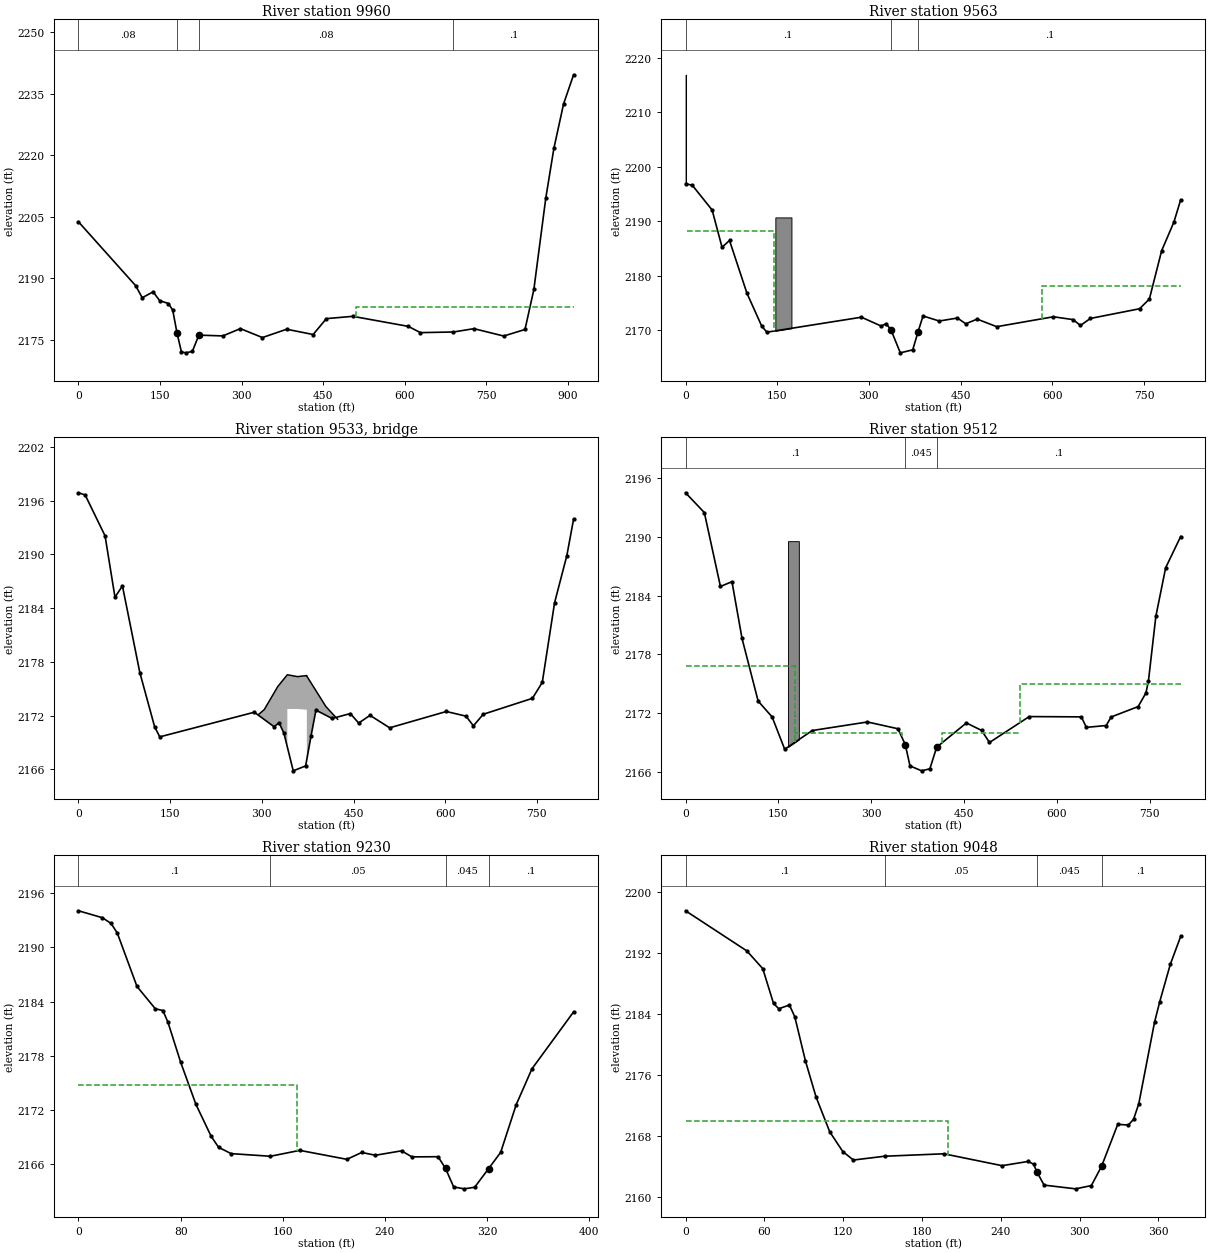
Type RM Length L Ch R = 1 ,9960    ,349.6,396.6,355.5
XS GIS Cut Line= 4
2203509.11477345422933.5495935232203224.14740685422912.698322796
2202955.86105683422866.825527197 2202640.3118265422708.355869673
#Sta/Elev= 30
       0 2203.72   105.2 2188.14   117.3 2185.19   137.3 2186.64   149.3  2184.5
   165.4 2183.79   173.4 2182.17   181.4 2176.53   189.4 2171.98   197.5 2171.75
   209.5  2172.1   221.5 2176.07   265.6 2175.88   297.9 2177.66   338.5 2175.48
   383.1 2177.51   431.8 2176.22   456.1  2180.1   504.8 2180.66   606.8 2178.21
   629.2 2176.68     690 2176.84   727.6 2177.65   782.4 2175.85   821.6 2177.45
   837.9 2187.21   859.8 2209.47   874.7 2221.62   892.6 2232.51     911 2239.61
#Mann= 4 ,-1,0
       0     .08       0   181.4    .045       0   221.5     .08       0
     690      .1       0
#XS Ineff= 2 , 0
                          509.86         2183.02
Permanent Ineff=
       F       F
Bank Sta=181.4,221.5
XS Rating Curve= 0 ,0
Exp/Cntr(USF)=0,0
Exp/Cntr=0.5,0.3

Type RM Length L Ch R = 1 ,9563    ,53.7,51.7,51.6
BEGIN DESCRIPTION:
Channel burned based on survey STA082BU
END DESCRIPTION:
XS GIS Cut Line= 3
2203562.86566621422620.1311569522203269.40333746422564.527768347
2202761.25014715422507.379841169
#Sta/Elev= 30
       0 2196.87    10.9 2196.63    43.5 2192.06    59.7 2185.22    71.9 2186.48
   100.4  2176.8   124.6 2170.76     133 2169.64   287.7 2172.39     320 2170.77
   328.2 2171.21   336.1 2170.05  351.35 2165.85  371.65  2166.4   380.4 2169.72
   388.5 2172.62     415 2171.69   444.8 2172.24   458.4 2171.18     477 2172.04
   509.1 2170.65   601.8 2172.47     634 2171.95   646.1 2170.87   662.2 2172.16
   742.7 2173.94   758.8 2175.72   778.9  2184.6     799 2189.87     810 2193.93
#Mann= 3 ,0,0
       0      .1       0   336.1    .045       0   380.4      .1       0
#XS Ineff= 4 ,-1
  144.58     315 2169.45    1.72  144.58 2188.21     399     530 2170.66
  583.16  903.162178.124
Permanent Ineff=
       F       F       F       F
#Block Obstruct= 2 ,-1
       0     .81 2216.89   146.9  173.23 2190.71
Bank Sta=336.1,380.4
XS Rating Curve= 0 ,0
Exp/Cntr(USF)=0,0
Exp/Cntr=0.5,0.3

Type RM Length L Ch R = 3 ,9533    ,,,
BEGIN DESCRIPTION:
Unnamed Road
Survey ID: 54075STA080
Deck information taken from LIDAR
Opening information taken from Survey
END DESCRIPTION:
Bridge Culvert--1,0,-1,-1, 0
Deck Dist Width WeirC Skew NumUp NumDn MinLoCord MaxHiCord MaxSubmerge Is_Ogee
26,14,2.6,0, 10, 9, , , 0.98, 0, 0,0,,
     294     304   326.2  341.69   358.3  372.72   373.6   373.6  404.79     424
  2172.1 2172.69 2175.27 2176.57 2176.362176.473 2176.48 2176.41 2173.02  2171.6
                         2172.75 2172.75 2172.67 2172.67 2172.67
     314     324   346.2  363.05  366.27   383.3   394.9  424.79     444
    2170 2172.69 2175.27 2176.51 2176.36 2176.36 2176.53 2173.02  2170.6
                         2172.73 2172.73 2172.74 2172.74
BR Coef=-1 ,-1 , 0 ,, 0 ,,,0.8,0,1.2,0,
WSPro=,,,, 1 ,,,, 0 ,,,, 0 ,,,,-1 ,-1 ,-1 , 0 , 0 , 0 , 0 , 0
BR U #Sta/Elev= 30
       0 2196.87    10.9 2196.63    43.5 2192.06    59.7 2185.22    71.9 2186.48
   100.4  2176.8   124.6 2170.76     133 2169.64   287.7 2172.39     320 2170.77
   328.2 2171.21   336.1 2170.05  351.35 2165.85  371.65  2166.4   380.4 2169.72
   388.5 2172.62     415 2171.69   444.8 2172.24   458.4 2171.18     477 2172.04
   509.1 2170.65   601.8 2172.47     634 2171.95   646.1 2170.87   662.2 2172.16
   742.7 2173.94   758.8 2175.72   778.9  2184.6     799 2189.87     810 2193.93
BR U #Mann= 3
       0      .1   336.1     .04   380.4      .1
BR D #Sta/Elev= 30
       0 2194.47   30.37 2192.45   56.38 2184.92   75.02 2185.41   91.25 2179.63
  117.33 2173.24  139.95 2171.62  160.24 2168.33  204.88 2170.24  294.01 2171.11
  346.74 2170.29  358.09 2167.92  362.81 2166.63  381.73 2166.13  394.94 2166.34
  402.27 2168.02  453.94 2171.01  478.54 2170.25   491.3 2169.02  555.53 2171.66
  639.82 2171.63  647.85 2170.56  679.96 2170.75  687.99 2171.62  731.66 2172.68
  744.19 2174.07   748.2 2175.26  760.24 2181.88   776.1 2186.83  800.34 2190.01
BR D #Mann= 3
       0      .1  358.09     .04  402.27      .1
BC Design=,, 0 ,, 0 ,,,,,,
BC Use User HTab Curves=0
BC User HTab FreeFlow(D)= 0

Type RM Length L Ch R = 1 ,9512    ,150,282,340.1
BEGIN DESCRIPTION:
Channel burned based on survey STA078BD
END DESCRIPTION:
XS GIS Cut Line= 4
2203606.11274623422570.7059226362203281.75964604422515.102534031
2203179.82010026422505.8353025972202812.21992004 422474.94453115
#Sta/Elev= 30
       0 2194.47   30.37 2192.45   56.38 2184.92   75.02 2185.41   91.25 2179.63
  117.33 2173.24  139.95 2171.62  160.24 2168.33  204.88 2170.24  294.01 2171.11
  343.36 2170.42   355.22168.799  362.81 2166.63  381.73 2166.13  394.94 2166.34
  405.95 2168.54  453.94 2171.01  478.54 2170.25   491.3 2169.02  555.53 2171.66
  639.82 2171.63  647.85 2170.56  679.96 2170.75  687.99 2171.62  731.66 2172.68
  744.19 2174.07   748.2 2175.26  760.24 2181.88   776.1 2186.83  800.34 2190.01
#Mann= 3 ,0,0
       0      .1       0   355.2    .045       0  405.95      .1       0
#XS Ineff= 4 ,-1
   -18.6  176.81 2176.85  176.81  350.19    2170     414     540    2170
     540     850    2175
Permanent Ineff=
       F       F       F       F
#Block Obstruct= 1 ,-1
  165.59  183.12 2189.54
Bank Sta=355.2,405.95
XS Rating Curve= 0 ,0
Exp/Cntr(USF)=0,0
Exp/Cntr=0.5,0.3

Type RM Length L Ch R = 1 ,9230    ,174.1,182,186
XS GIS Cut Line= 4
2203628.66205895422576.2978217362203560.54790791422526.254771991
2203453.51138485422427.558757217 2203421.5394364422273.259353838
#Sta/Elev= 30
       0 2194.03    18.8 2193.26    25.5 2192.63    30.4 2191.57    45.8 2185.67
    60.2  2183.2    66.1 2183.01    70.1  2181.7      80  2177.3      92 2172.63
   103.8 2169.14   109.7  2167.9   119.5  2167.2   150.3 2166.91   173.3 2167.56
   210.2 2166.57   221.8 2167.33   232.5 2167.02     253 2167.51   261.1 2166.84
   281.6 2166.86   287.4 2165.57   293.8 2163.52     302 2163.31   310.2 2163.48
   321.2 2165.55   330.6 2167.34   342.8 2172.62   355.1 2176.57   387.7 2182.86
#Mann= 4 ,-1,0
       0      .1       0   150.3     .05       0   287.4    .045       0
   321.2      .1       0
#XS Ineff= 2 , 0
          171.43 2174.75
Permanent Ineff=
       F       F
Bank Sta=287.4,321.2
XS Rating Curve= 0 ,0
Exp/Cntr(USF)=0,0
Exp/Cntr=0.3,0.1

Type RM Length L Ch R = 1 ,9048    ,141.6,160.1,182.4
XS GIS Cut Line= 3
2203656.46375325422615.2201937592203621.71163538 422406.70748649
2203613.37112709 422241.28740539
#Sta/Elev= 30
       0 2197.55    46.7 2192.28    58.8 2189.95      67 2185.38      71 2184.69
    79.1 2185.18    83.2 2183.62    91.3 2177.83    99.4 2173.09   109.8 2168.53
   119.7 2165.95   127.8 2164.83   151.5 2165.33   196.7 2165.65     241 2164.09
     261 2164.65     265 2164.28   267.7 2163.22     273 2161.54     297 2161.05
     309 2161.48   316.8 2164.02   329.1 2169.52   337.1 2169.42   341.1 2170.16
   345.1 2172.21   357.1 2182.91   361.1 2185.64   369.1 2190.51     377 2194.18
#Mann= 4 ,-1,0
       0      .1       0   151.5     .05       0   267.7    .045       0
   316.8      .1       0
#XS Ineff= 2 , 0
             200    2170
Permanent Ineff=
       F       F
Bank Sta=267.7,316.8
XS Rating Curve= 0 ,0
Exp/Cntr(USF)=0,0
Exp/Cntr=0.5,0.3

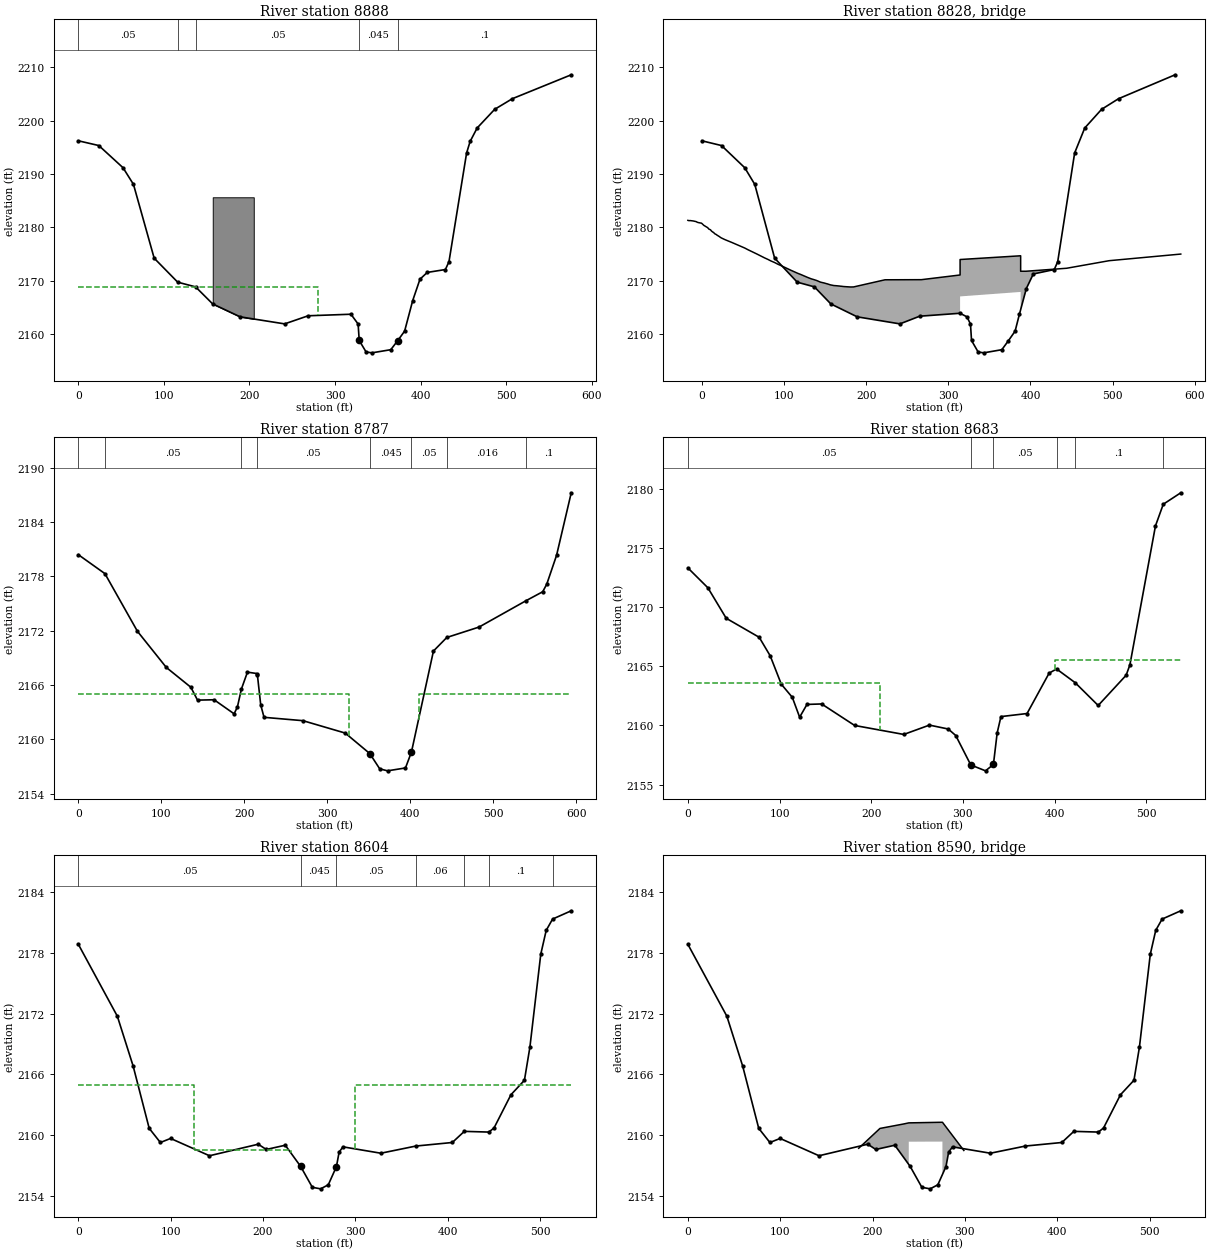
Type RM Length L Ch R = 1 ,8888    ,95,100.9,89.5
BEGIN DESCRIPTION:
Channel burned based on survey STA072BU
END DESCRIPTION:
XS GIS Cut Line= 6
2203780.51407973422644.8476139872203762.78412746422526.647932212
2203761.30663144422392.9345422052203756.13539536422347.870913529
2203801.26350667422221.681648651 2203833.7671392422082.059554514
#Sta/Elev= 30
       0 2196.24    23.9 2195.35    52.2 2191.19    64.4 2188.07    88.6 2174.23
   116.1 2169.73     137 2168.85     157 2165.65   189.1 2163.23   241.1 2161.91
   268.6 2163.43   318.6 2163.72     327 2161.88  328.27  2158.8  336.31 2156.64
  343.13 2156.48  365.17 2157.07  373.26 2158.77  381.33 2160.55   390.8 2166.29
   399.3 2170.29   407.8 2171.56     429  2172.1   433.2 2173.58   453.8 2193.96
   457.9 2196.12   466.1 2198.64   486.6 2202.14   507.2 2204.13   576.1 2208.62
#Mann= 5 ,-1,0
       0     .05       0   116.1    .016       0     137     .05       0
  328.27    .045       0  373.26      .1       0
#XS Ineff= 2 , 0
             280 2168.83     426         2171.78
Permanent Ineff=
       F       F
#Block Obstruct= 1 ,-1
  157.05     205 2185.65
Bank Sta=328.27,373.26
XS Rating Curve= 0 ,0
Exp/Cntr(USF)=0,0
Exp/Cntr=0.5,0.3

Type RM Length L Ch R = 3 ,8828    ,,,
BEGIN DESCRIPTION:
Seneca Trail
Survey ID: 54075STA070
Included 2.9ft railing
END DESCRIPTION:
Bridge Culvert--1,0,-1,-1, 0
Deck Dist Width WeirC Skew NumUp NumDn MinLoCord MaxHiCord MaxSubmerge Is_Ogee
41,36,2.6,0, 79, 79, , , 0.98, 0, 0,0,,
     -17   -16.6   -15.1   -14.2   -10.6    -7.1    -5.6    -4.5     -.4     -.1
     2.5     3.5     3.6     3.8       7     8.5    10.5    11.7    13.3    14.1
    15.7    17.6      18    19.8    21.1    22.7    23.8    27.9    36.9    52.1
    56.2      67    76.4    80.4    84.2    88.5    92.5    96.5   108.6   116.6
   120.6   128.6   129.8   131.4   132.6   133.7   135.6   139.8   140.6   143.9
   144.6   149.1   151.3   152.3   152.6   156.6   156.7   160.6   164.1   164.6
   165.3   167.9   168.6   169.5   171.7   172.7   180.7   182.3   184.7     223
  267.22  314.35  314.35  388.08  388.08  394.53  444.06  495.87     583
 2181.32 2181.29 2181.27 2181.28 2181.21 2181.09 2180.97 2180.91 2180.79 2180.75
 2180.37 2180.29 2180.28 2180.25 2179.96 2179.69 2179.55 2179.32 2179.12 2179.07
 2178.81 2178.66  2178.6 2178.42  2178.3 2178.12 2178.02 2177.72 2177.15 2176.14
 2175.81 2175.01 2174.28    2174  2173.7 2173.42  2173.1 2172.83 2171.95  2171.4
 2171.16 2170.63 2170.56 2170.46 2170.39 2170.33 2170.25 2170.04 2169.99 2169.77
 2169.73 2169.57 2169.47 2169.43 2169.42 2169.22 2169.22  2169.1 2169.06 2169.05
 2169.04    2169 2168.98 2168.97 2168.93 2168.91 2168.83 2168.83 2168.84 2170.18
  2170.2 2171.08 2173.98 2174.68 2171.78 2171.78 2172.34 2173.76    2175
                                                                                
                                                                                
                                                                                
                                                                                
                                                                                
                                                                                
                                                                                
         2167.06 2167.06  2167.9  2167.9
       0      .4     1.9     2.8     6.4     9.9    11.4    12.5    16.6    16.9
    19.5    20.5    20.6    20.8      24    25.5    27.5    28.7    30.3    31.1
    32.7    34.6      35    36.8    38.1    39.7    40.8    44.9    53.9    69.1
    73.2      84    93.4    97.4   101.2   105.5   109.5   113.5   125.6   133.6
   137.6   145.6   146.8   148.4   149.6   150.7   152.6   156.8   157.6   160.9
   161.6   166.1   168.3   169.3   169.6   173.6   173.7   177.6   181.1   181.6
   182.3   184.9   185.6   186.5   188.7   189.7   197.7   199.3   201.7     240
  284.22  331.35  331.35  405.08  405.08  411.53  461.06  512.87     600
 2181.32 2181.29 2181.27 2181.28 2181.21 2181.09 2180.97 2180.91 2180.79 2180.75
 2180.37 2180.29 2180.28 2180.25 2179.96 2179.69 2179.55 2179.32 2179.12 2179.07
 2178.81 2178.66  2178.6 2178.42  2178.3 2178.12 2178.02 2177.72 2177.15 2176.14
 2175.81 2175.01 2174.28    2174  2173.7 2173.42  2173.1 2172.83 2171.95  2171.4
 2171.16 2170.63 2170.56 2170.46 2170.39 2170.33 2170.25 2170.04 2169.99 2169.77
 2169.73 2169.57 2169.47 2169.43 2169.42 2169.22 2169.22  2169.1 2169.06 2169.05
 2169.04    2169 2168.98 2168.97 2168.93 2168.91 2168.83 2168.83 2168.84 2170.18
  2170.2 2171.08 2173.98 2174.68 2171.78 2171.78 2172.34 2173.76    2175
                                                                                
                                                                                
                                                                                
                                                                                
                                                                                
                                                                                
                                                                                
         2167.06 2167.06  2167.9  2167.9
BR Coef=-1 ,-1 , 0 ,, 0 ,,,0.8,0,1.2,0,
WSPro=,,,, 1 ,,,, 0 ,,,, 0 ,,,,-1 ,-1 ,-1 , 0 , 0 , 0 , 0 , 0
BR U #Sta/Elev= 30
       0 2196.24    23.9 2195.35    52.2 2191.19    64.4 2188.07    88.6 2174.23
   116.1 2169.73     137 2168.85     157 2165.65   189.1 2163.23   241.1 2161.91
   265.2 2163.35   314.3  2163.9   322.7 2163.23     327 2161.88  328.27  2158.8
  336.31 2156.64  343.13 2156.48  365.17 2157.07  373.26 2158.77  381.33 2160.55
   386.5 2163.68     395 2168.54   403.5 2171.27     429  2172.1   433.2 2173.58
   453.8 2193.96   466.1 2198.64   486.6 2202.14   507.2 2204.13   576.1 2208.62
BR U #Mann= 5
       0     .05   116.1    .016     137     .05   314.3     .04  373.26      .1
BR U Banks=314.3,386.5
BR D #Sta/Elev= 30
       0 2180.38      32 2178.29    71.2 2171.92     106 2167.93   135.6 2165.74
   143.6 2164.32   163.6 2164.36   187.7 2162.81   191.7 2163.56   196.5 2165.54
   203.8 2167.41   214.9 2167.26   215.8  2167.1   219.8 2163.79   223.8 2162.42
   270.7 2162.05   321.7 2160.68  351.24 2158.42  363.25 2156.73  372.67 2156.51
   394.3 2156.83   401.5 2158.59     428 2169.74   444.1 2171.24     483 2172.39
     540 2175.32   559.7 2176.29   564.6 2177.13   576.4 2180.31   594.1 2187.22
BR D #Mann= 8
       0    .016      32     .05   196.5    .016   214.9     .05  351.24     .04
   401.5     .05   444.1    .016     540      .1
BC Design=,, 0 ,, 0 ,,,,,,
BC Use User HTab Curves=0
BC User HTab FreeFlow(D)= 0

Type RM Length L Ch R = 1 ,8787    ,117.4,104.1,98.1
BEGIN DESCRIPTION:
Channel burned based on survey STA068BD
END DESCRIPTION:
XS GIS Cut Line= 6
2203860.70112023422639.659738441 2203845.2557345422531.542038375
2203836.65892857422373.7270939172203852.91138482422311.672260985
2203895.75876946422207.5087914222203921.61494985422059.759189204
#Sta/Elev= 30
       0 2180.38      32 2178.29    71.2 2171.92     106 2167.93   135.6 2165.74
   143.6 2164.32   163.6 2164.36   187.7 2162.81   191.7 2163.56   196.5 2165.54
   203.8 2167.41   214.9 2167.26   215.8  2167.1   219.8 2163.79   223.8 2162.42
   270.7 2162.05   321.7 2160.68  351.24 2158.42  363.25 2156.73  372.67 2156.51
   394.3 2156.83   401.5 2158.59     428 2169.74   444.1 2171.24     483 2172.39
     540 2175.32   559.7 2176.29   564.6 2177.13   576.4 2180.31   594.1 2187.22
#Mann= 8 ,-1,0
       0    .016       0      32     .05       0   196.5    .016       0
   214.9     .05       0  351.24    .045       0   401.5     .05       0
   444.1    .016       0     540      .1       0
#XS Ineff= 2 , 0
             326    2165     410            2165
Permanent Ineff=
       F       F
Bank Sta=351.24,401.5
XS Rating Curve= 0 ,0
Exp/Cntr(USF)=0,0
Exp/Cntr=0.5,0.3

Type RM Length L Ch R = 1 ,8683    ,82.9,79,83.9
XS GIS Cut Line= 5
2203938.81289011422570.9073562852203948.94660768 422364.17951779
2203982.38787568422221.2941000082203990.49484973422156.438307539
2203956.04020999422042.940670718
#Sta/Elev= 30
       0 2173.33    21.8 2171.65    41.8 2169.07    77.8 2167.46    89.8 2165.89
   101.9 2163.49   113.9 2162.38   121.9  2160.7   129.9 2161.78   145.9 2161.82
   181.9    2160   235.5 2159.24   263.5 2160.03     284  2159.7   292.2 2159.15
   308.6 2156.66   324.7 2156.16   333.3  2156.7   337.4 2159.37   341.5 2160.75
     370 2161.01   394.1 2164.43   402.2 2164.78   422.5 2163.62   447.6 2161.69
   478.1 2164.25   482.2 2165.13   510.1 2176.89   518.6 2178.72   537.7 2179.69
#Mann= 6 ,-1,0
       0     .05       0   308.6    .045       0   333.3     .05       0
   402.2    .016       0   422.5      .1       0   518.6    .016       0
#XS Ineff= 2 , 0
             210 2163.61  400.66         2165.54
Permanent Ineff=
       F       F
Bank Sta=308.6,333.3
XS Rating Curve= 0 ,0
Exp/Cntr(USF)=0,0
Exp/Cntr=0.5,0.3

Type RM Length L Ch R = 1 ,8604    ,32.4,30.5,28.3
BEGIN DESCRIPTION:
Channel burned based on survey STA062BU
END DESCRIPTION:
XS GIS Cut Line= 6
2204013.61043889422509.9184983622204013.61043889422421.879799738
2204042.95667177422289.0494825152204063.03567321422222.634323904
2204056.85751892422160.8527810092203973.45243601422003.309846629
#Sta/Elev= 30
       0 2178.85    42.2 2171.75    59.3 2166.83    76.7 2160.67    88.8 2159.27
    99.9 2159.67     142 2157.96   194.8  2159.1   203.5 2158.58   224.1    2159
   240.7 2156.91  253.39 2154.84  262.38 2154.69  270.68 2155.09   279.5 2156.89
   282.4 2158.32   286.6 2158.84   327.6 2158.21   365.6 2158.92     405 2159.27
     418 2160.37   444.6  2160.3   450.2 2160.71   468.5 2163.99   483.1 2165.42
     489 2168.68   500.8 2177.88   506.7 2180.24   513.6 2181.35   533.8 2182.17
#Mann= 7 ,-1,0
       0     .05       0   240.7    .045       0   279.5     .05       0
   365.6     .06       0     418    .016       0   444.6      .1       0
   513.6    .016       0
#XS Ineff= 4 ,-1
       0     125    2165     125     230 2158.48     284     300 2158.48
     300     550    2165
Permanent Ineff=
       F       F       F       F
Bank Sta=240.7,279.5
XS Rating Curve= 0 ,0
Exp/Cntr(USF)=0,0
Exp/Cntr=0.5,0.3

Type RM Length L Ch R = 3 ,8590    ,,,
BEGIN DESCRIPTION:
Pedestrian bridge
Survey ID:54075STA060
Deck information taken from LIDAR
Opening information taken from Survey
END DESCRIPTION:
Bridge Culvert--1,0,-1,-1, 0
Deck Dist Width WeirC Skew NumUp NumDn MinLoCord MaxHiCord MaxSubmerge Is_Ogee
9,8,2.6,0, 6, 6, , , 0.98, 0, 0,0,,
     185     208  233.61  239.24  275.69  298.86
  2158.7 2160.66  2161.1 2161.21 2161.27 2158.48
                         2159.35 2159.36
     175     208  233.61  239.24  275.69  298.86
  2158.5 2160.66  2161.1 2161.21 2161.27 2158.48
                         2159.35 2159.36
BR Coef=-1 ,-1 , 0 ,, 0 ,,,0.8,0,1.2,0,
WSPro=,,,, 1 ,,,, 0 ,,,, 0 ,,,,-1 ,-1 ,-1 , 0 , 0 , 0 , 0 , 0
BR U #Sta/Elev= 30
       0 2178.85    42.2 2171.75    59.3 2166.83    76.7 2160.67    88.8 2159.27
    99.9 2159.67     142 2157.96   194.8  2159.1   203.5 2158.58   224.1    2159
   240.7 2156.91  253.39 2154.84  262.38 2154.69  270.68 2155.09   279.5 2156.89
   282.4 2158.32   286.6 2158.84   327.6 2158.21   365.6 2158.92     405 2159.27
     418 2160.37   444.6  2160.3   450.2 2160.71   468.5 2163.99   483.1 2165.42
     489 2168.68   500.8 2177.88   506.7 2180.24   513.6 2181.35   533.8 2182.17
BR U #Mann= 7
       0     .05   240.7     .04   279.5     .05   365.6     .06     418    .016
   444.6      .1   513.6    .016
BR D #Sta/Elev= 30
       0 2190.57    31.8 2184.15    55.8 2177.15    79.8  2161.1    83.8 2159.38
    99.9 2159.06     108 2158.17   160.6 2157.32   176.8 2158.44   201.2 2157.62
   217.6 2158.63   225.8 2157.04     234 2156.98   242.2 2156.03   262.7 2155.53
   276.1 2156.26   283.2  2158.5   341.3 2157.51   389.3 2158.85   431.6 2158.76
   450.1 2159.93   466.1 2160.19     493 2161.79     498 2162.62     503 2164.73
   507.9 2168.09   517.1  2176.6   520.4 2178.78   526.2 2181.08   533.2 2181.97
BR D #Mann= 5
       0     .05   242.2     .04   276.1     .05   450.1    .016   466.1      .1
BC Design=,, 0 ,, 0 ,,,,,,
BC Use User HTab Curves=0
BC User HTab FreeFlow(D)= 0

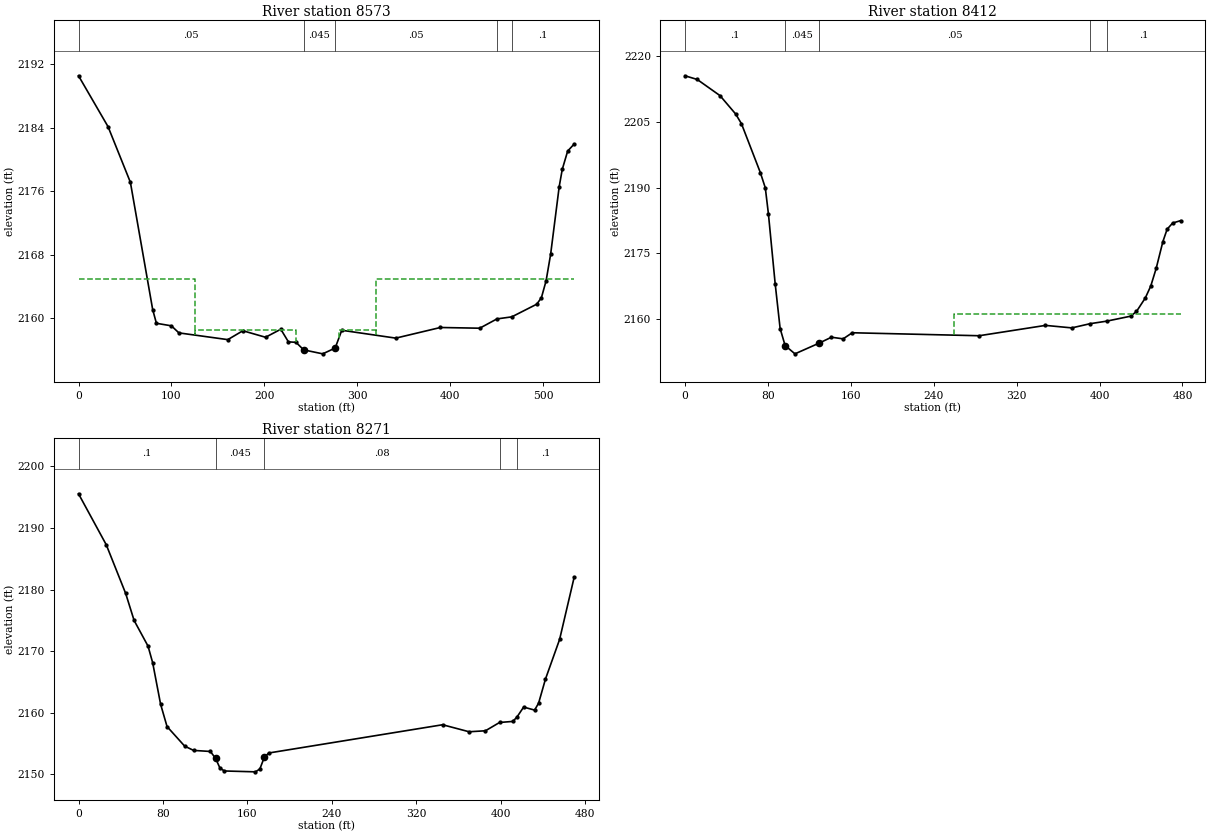
Type RM Length L Ch R = 1 ,8573    ,178.3,161,94.6
XS GIS Cut Line= 6
 2204052.2239032422513.0075755072204053.76844177422418.790722593
2204089.29282894422230.3570167662204092.38190608422196.377168174
2204044.87459914422091.3640155782203986.60904381422012.911132264
#Sta/Elev= 30
       0 2190.57    31.8 2184.15    55.8 2177.15    79.8  2161.1    83.8 2159.38
    99.9 2159.06     108 2158.17   160.6 2157.32   176.8 2158.44   201.2 2157.62
   217.6 2158.63   225.8 2157.04     234 2156.98   242.2 2156.03   262.7 2155.53
   276.1 2156.26   283.2  2158.5   341.3 2157.51   389.3 2158.85   431.6 2158.76
   450.1 2159.93   466.1 2160.19     493 2161.79     498 2162.62     503 2164.73
   507.9 2168.09   517.1  2176.6   520.4 2178.78   526.2 2181.08   533.2 2181.97
#Mann= 5 ,-1,0
       0     .05       0   242.2    .045       0   276.1     .05       0
   450.1    .016       0   466.1      .1       0
#XS Ineff= 4 ,-1
       0     125    2165     125     234  2158.5     280     320  2158.5
     320     550    2165
Permanent Ineff=
       F       F       F       F
Bank Sta=242.2,276.1
XS Rating Curve= 0 ,0
Exp/Cntr(USF)=0,0
Exp/Cntr=0.5,0.3

Type RM Length L Ch R = 1 ,8412    ,155.6,141.2,99.6
XS GIS Cut Line= 4
2204302.61335099422362.1527742762204225.59709743422243.588278669
 2204048.2570399422060.1679905932203986.31332945422006.948746398
#Sta/Elev= 30
       0 2215.51    11.8 2214.67    33.8 2210.98    48.9 2206.79    54.5 2204.57
    72.7 2193.43    77.5 2189.94    80.5 2184.01      87  2168.1    91.8 2157.85
    96.6 2153.97   106.1 2152.07   129.3  2154.5   141.3 2155.86   152.6 2155.49
   161.4 2156.88   283.8  2156.2   347.8 2158.56   373.2 2157.99   390.9 2158.95
   406.7 2159.52   429.9 2160.66   435.6 2161.73   444.1 2164.81   449.4 2167.55
   454.6 2171.56   461.1  2177.7   465.2 2180.52   470.5 2181.91   478.2 2182.46
#Mann= 5 ,-1,0
       0      .1       0    96.6    .045       0   129.3     .05       0
   390.9    .016       0   406.7      .1       0
#XS Ineff= 2 , 0
                             260         2161.17
Permanent Ineff=
       F       F
Bank Sta=96.6,129.3
XS Rating Curve= 0 ,0
Exp/Cntr(USF)=0,0
Exp/Cntr=0.3,0.1

Type RM Length L Ch R = 1 ,8271    ,156,148.8,144.8
XS GIS Cut Line= 4
2204428.04754563422192.5809488992204346.89152084422155.191460446
2204127.21680351422085.9579589772204011.14139896421990.700737428
#Sta/Elev= 30
       0 2195.56    26.3 2187.28    44.7 2179.37    52.7 2174.98    65.9 2170.81
    70.3 2168.11    77.8 2161.38    83.9 2157.75   100.6 2154.57   109.1 2153.87
     125  2153.7   129.9 2152.58   134.1 2150.99   138.3 2150.53   167.7 2150.39
   171.9 2150.86   176.1 2152.75   180.3 2153.45   345.1 2158.04   370.2  2156.9
   385.7 2157.06   399.1 2158.41   411.6 2158.58   415.5 2159.27   421.9 2160.91
   432.3 2160.42   436.1 2161.55   442.6 2165.46     456  2171.9   469.8    2182
#Mann= 5 ,-1,0
       0      .1       0   129.9    .045       0   176.1     .08       0
   399.1    .016       0   415.5      .1       0
Bank Sta=129.9,176.1
XS Rating Curve= 0 ,0
Exp/Cntr(USF)=0,0
Exp/Cntr=0.5,0.3