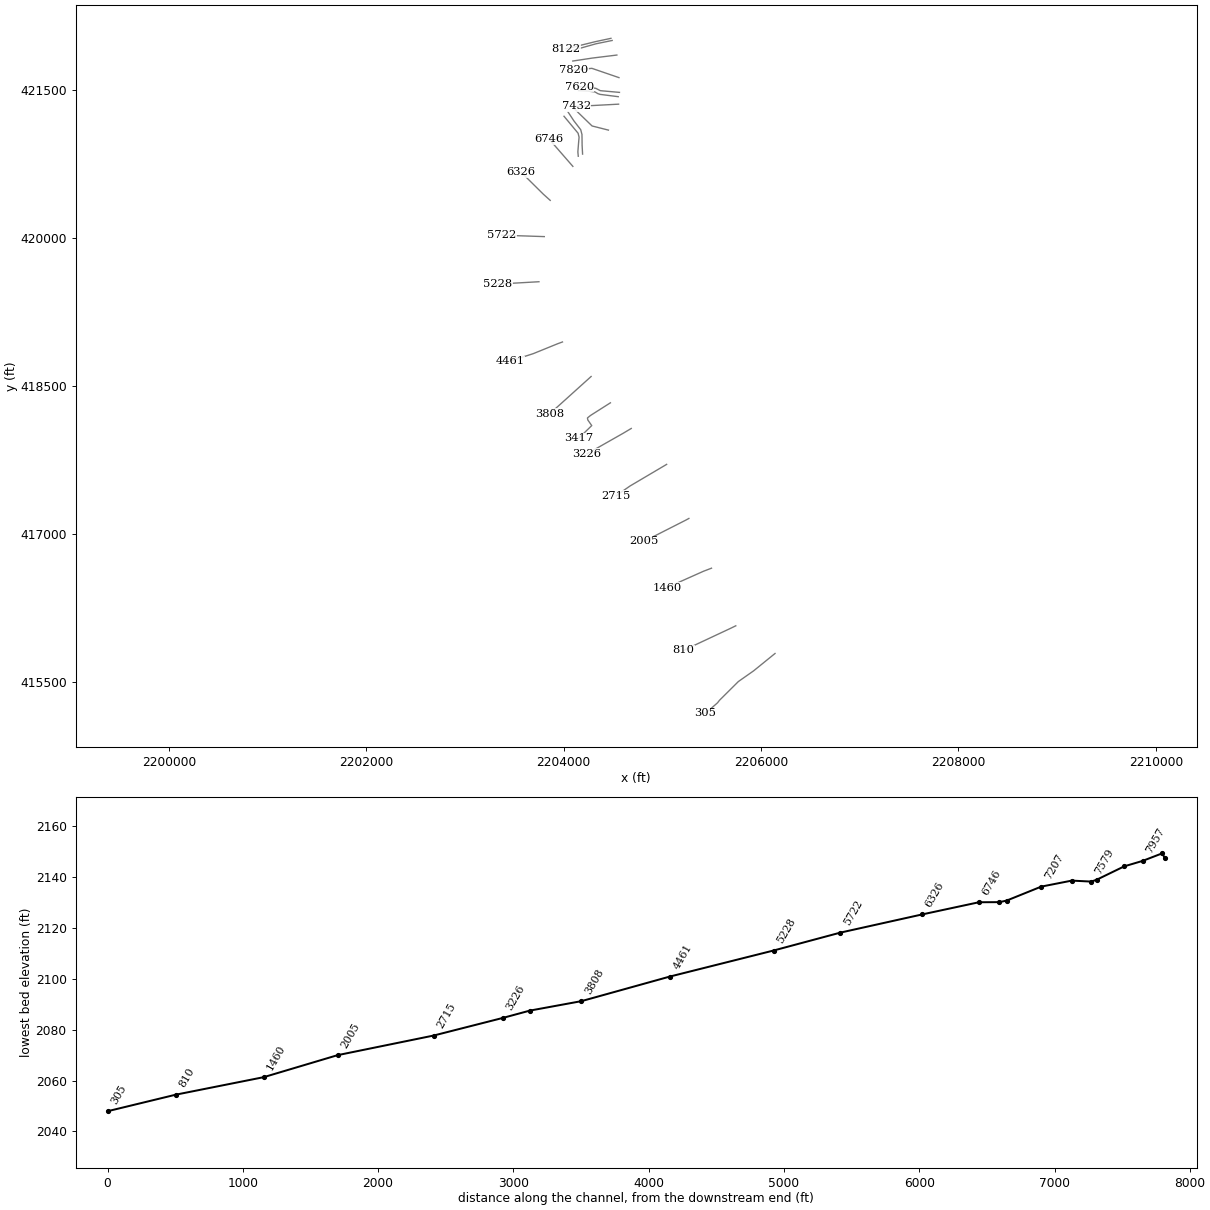
HEC-RAS study STMPNGCRK.prj: STMPNGCRK

--- STMPNGCRK.g01 (geometry) --- (continued)

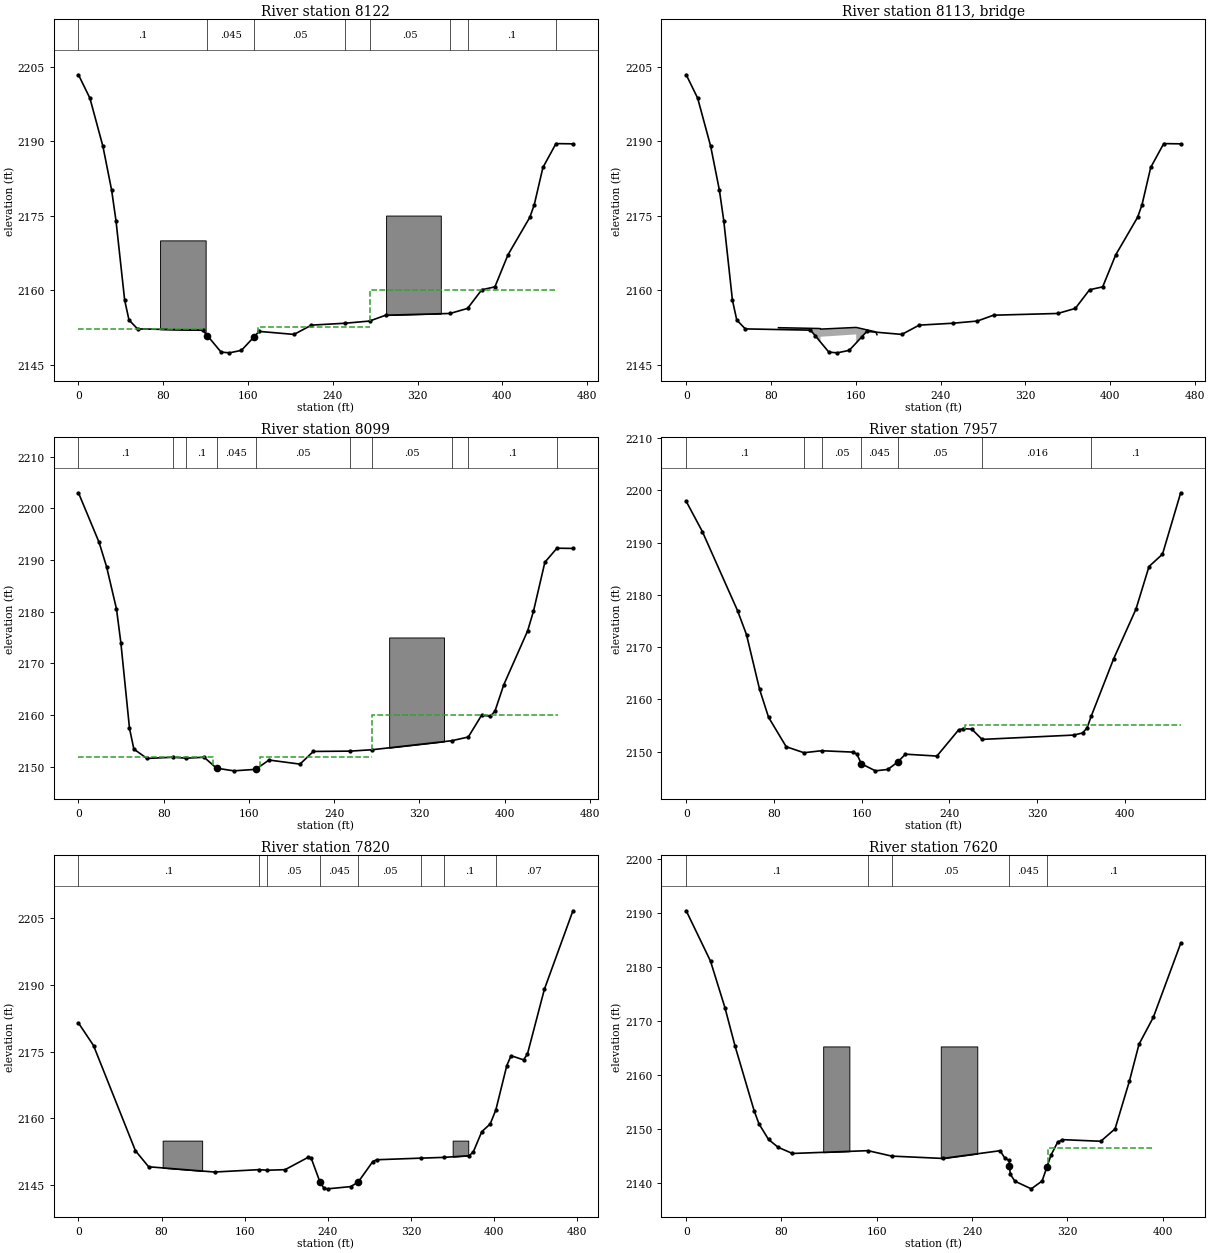
Type RM Length L Ch R = 1 ,8122    ,22.9,22.8,23.5
BEGIN DESCRIPTION:
Channel burned from survey STA052BU
END DESCRIPTION:
XS GIS Cut Line= 3
2204478.77703962422027.0283451662204319.68956666421993.048496574
2204024.68269934421920.455183673
#Sta/Elev= 30
       0 2203.35    10.8 2198.64    23.1 2188.92    31.3 2180.11    35.4 2173.99
    43.6 2157.95    47.7 2153.95    55.8 2152.17   117.2 2151.92   121.7  2150.8
  134.54  2147.5  142.43 2147.35  153.78 2147.85   165.5 2150.53   170.4 2151.67
   203.4 2151.06   219.8 2152.93   251.4 2153.31   274.6 2153.75   289.9 2154.93
   350.6 2155.28   367.1  2156.3   380.5 2160.05   392.9 2160.64   405.2 2167.08
   425.8 2174.63     430 2177.16   438.2 2184.68   450.5 2189.49   466.5 2189.44
#Mann= 8 ,-1,0
       0      .1       0   121.7    .045       0   165.5     .05       0
   251.4    .016       0   274.6     .05       0   350.6    .016       0
   367.1      .1       0   450.5    .016       0
#XS Ineff= 3 ,-1
       0     117 2152.25     169     275 2152.58     275     450    2160
Permanent Ineff=
       F       F       F
#Block Obstruct= 2 ,-1
      77     120    2170  290.23  341.85    2175
Bank Sta=121.7,165.5
XS Rating Curve= 0 ,0
Exp/Cntr(USF)=0,0
Exp/Cntr=0.5,0.3

Type RM Length L Ch R = 3 ,8113    ,,,
BEGIN DESCRIPTION:
Pedestrian bridge
Survey ID: 54075STA050
Deck information taken from LIDAR
Opening information taken from Survey
END DESCRIPTION:
Bridge Culvert--1,0,-1,-1, 0
Deck Dist Width WeirC Skew NumUp NumDn MinLoCord MaxHiCord MaxSubmerge Is_Ogee
9,8.5,2.6,0, 6, 6, , , 0.98, 0, 0,0,,
      87  126.32  126.66  160.35  178.74     180
 2152.42 2152.25 2152.13 2152.47 2151.58    2151
                 2150.59 2151.06
      87  126.32  131.66  165.35  178.74     180
 2152.42 2152.25 2152.13 2152.47 2151.58    2151
                 2150.59 2151.06
BR Coef=-1 ,-1 , 0 ,, 0 ,,,0.8,0,1.2,0,
WSPro=,,,, 1 ,,,, 0 ,,,, 0 ,,,,-1 ,-1 ,-1 , 0 , 0 , 0 , 0 , 0
BR U #Sta/Elev= 30
       0 2203.35    10.8 2198.64    23.1 2188.92    31.3 2180.11    35.4 2173.99
    43.6 2157.95    47.7 2153.95    55.8 2152.17   117.2 2151.92   121.7  2150.8
  134.54  2147.5  142.43 2147.35  153.78 2147.85   165.5 2150.53   170.4 2151.67
   203.4 2151.06   219.8 2152.93   251.4 2153.31   274.6 2153.75   289.9 2154.93
   350.6 2155.28   367.1  2156.3   380.5 2160.05   392.9 2160.64   405.2 2167.08
   425.8 2174.63     430 2177.16   438.2 2184.68   450.5 2189.49   466.5 2189.44
BR U #Mann= 8
       0      .1   121.7     .04   165.5     .05   251.4    .016   274.6     .05
   350.6    .016   367.1      .1   450.5    .016
BR D #Sta/Elev= 30
       0 2203.01    19.4  2193.4    26.4  2188.7    35.7 2180.53    39.8    2174
    47.9 2157.46      52 2153.44    64.3 2151.64    88.8 2151.87     101 2151.69
   117.9 2151.87   129.6 2149.75   145.9 2149.24   166.4 2149.53   178.8 2151.33
   207.9 2150.54   220.4 2152.99   254.8 2153.05   275.6 2153.32   350.2 2155.06
   365.8 2155.78   378.3 2159.99   386.6 2159.81   390.8 2160.76   399.1 2165.88
   421.5 2176.31     427 2180.12   437.7 2189.59     449 2192.29     464 2192.25
BR D #Mann= 10
       0      .1    88.8    .016     101      .1   129.6     .04   166.4     .05
   254.8    .016   275.6     .05   350.2    .016   365.8      .1     449    .016
BC Design=,, 0 ,, 0 ,,,,,,
BC Use User HTab Curves=0
BC User HTab FreeFlow(D)= 0

Type RM Length L Ch R = 1 ,8099    ,144.6,142.6,137.3
XS GIS Cut Line= 3
 2204491.1333482422005.4048051532204325.86772095421971.424956561
2204041.67262364421891.108950798
#Sta/Elev= 30
       0 2203.01    19.4  2193.4    26.4  2188.7    35.7 2180.53    39.8    2174
    47.9 2157.46      52 2153.44    64.3 2151.64    88.8 2151.87     101 2151.69
   117.9 2151.87   129.6 2149.75   145.9 2149.24   166.4 2149.53   178.8 2151.33
   207.9 2150.54   220.4 2152.99   254.8 2153.05   275.6 2153.32   350.2 2155.06
   365.8 2155.78   378.3 2159.99   386.6 2159.81   390.8 2160.76   399.1 2165.88
   421.5 2176.31     427 2180.12   437.7 2189.59     449 2192.29     464 2192.25
#Mann= 10 ,-1,0
       0      .1       0    88.8    .016       0     101      .1       0
   129.6    .045       0   166.4     .05       0   254.8    .016       0
   275.6     .05       0   350.2    .016       0   365.8      .1       0
     449    .016       0
#XS Ineff= 3 ,-1
       0     126    2152     170     275    2152     275     450    2160
Permanent Ineff=
       F       F       F
#Block Obstruct= 1 ,-1
  291.56  343.01 2175.03
Bank Sta=129.6,166.4
XS Rating Curve= 0 ,0
Exp/Cntr(USF)=0,0
Exp/Cntr=0.5,0.3

Type RM Length L Ch R = 1 ,7957    ,163.5,136.5,117.8
XS GIS Cut Line= 3
2204538.72897045421857.4936391282204291.46626166421827.092486408
2204091.83202547421796.691333688
#Sta/Elev= 30
       0 2197.92    14.7 2192.14    46.9 2176.95      55 2172.38    66.9 2161.94
    75.1 2156.57    91.2 2150.93   107.4 2149.78   123.5 2150.16   151.7  2149.9
   155.7 2149.54   159.7 2147.67   172.6 2146.31   183.9 2146.58   192.8 2147.97
     200  2149.5   228.7 2149.14   248.4 2154.12   252.5 2154.39   260.5  2154.3
   269.9 2152.33   353.6 2153.16   361.7 2153.57   365.7 2154.55   369.6 2156.84
     390  2167.8   410.3 2177.28   422.2 2185.44   434.5  2187.8   451.1 2199.56
#Mann= 7 ,-1,0
       0      .1       0   107.4    .016       0   123.5     .05       0
   159.7    .045       0   192.8     .05       0   269.9    .016       0
   369.6      .1       0
#XS Ineff= 2 , 0
                             254            2155
Permanent Ineff=
       F       F
Bank Sta=159.7,192.8
XS Rating Curve= 0 ,0
Exp/Cntr(USF)=0,0
Exp/Cntr=0.3,0.1

Type RM Length L Ch R = 1 ,7820    ,185.8,203.8,207.4
XS GIS Cut Line= 3
2204560.00977735421628.4716219722204285.38603112421722.715195403
2204100.95237128421704.474503771
#Sta/Elev= 30
       0 2181.44    14.5 2176.37    54.8 2152.73    67.5 2149.12   130.9 2147.94
   173.6 2148.47   181.7 2148.34   198.8 2148.47   220.8 2151.22     224    2151
   232.4 2145.66   236.3 2144.25   239.7 2144.16   261.8 2144.66     269 2145.65
   283.2  2150.3   286.9  2150.7   329.4 2151.06   351.4 2151.23     376 2151.61
     380 2152.54     388    2157   396.1 2158.74   401.5 2161.86   412.1 2171.88
   416.2 2174.09   428.2 2173.15   431.9 2174.43   448.3 2189.06   475.7 2206.66
#Mann= 8 ,-1,0
       0      .1       0   173.6    .016       0   181.7     .05       0
   232.4    .045       0     269     .05       0   329.4    .016       0
   351.4      .1       0   401.5     .07       0
#Block Obstruct= 2 ,-1
      81     119    2155     360     375    2155
Bank Sta=232.4,269
XS Rating Curve= 0 ,0
Exp/Cntr(USF)=0,0
Exp/Cntr=0.5,0.3

Type RM Length L Ch R = 1 ,7620    ,39.3,40.3,43
BEGIN DESCRIPTION:
Channel burned from survey STA042BU
END DESCRIPTION:
XS GIS Cut Line= 5
2204565.03349414421478.8287680992204371.55557148421496.033826839
2204325.31590029421520.0261090582204228.30130045421530.681043487
2204157.25252612421536.859197777
#Sta/Elev= 30
       0 2190.39    20.4 2181.06    32.5 2172.46      41 2165.34    57.1 2153.31
    61.1 2150.93    69.1 2148.05    77.2 2146.59    89.2 2145.45   152.6 2145.97
   172.6 2144.96   215.4 2144.53   263.6 2145.96   267.6 2144.56  271.23 2144.15
  271.41 2143.04  272.13 2141.61  275.95 2140.32  289.72  2138.9  298.84 2140.35
  302.99 2143.02   306.4 2145.18   311.9 2147.55   315.9 2148.01   348.1 2147.71
   360.1 2150.01   372.2  2158.9   380.2 2165.68   392.2 2170.65   415.2 2184.36
#Mann= 5 ,-1,0
       0      .1       0   152.6    .016       0   172.6     .05       0
  271.41    .045       0  302.99      .1       0
#XS Ineff= 2 ,-1
       0     253 2145.54     304   391.3 2146.39
Permanent Ineff=
       F       F
#Block Obstruct= 2 ,-1
     115     137 2165.27  213.74  244.39 2165.27
Bank Sta=271.41,302.99
XS Rating Curve= 0 ,0
Exp/Cntr(USF)=0,0
Exp/Cntr=0.5,0.3

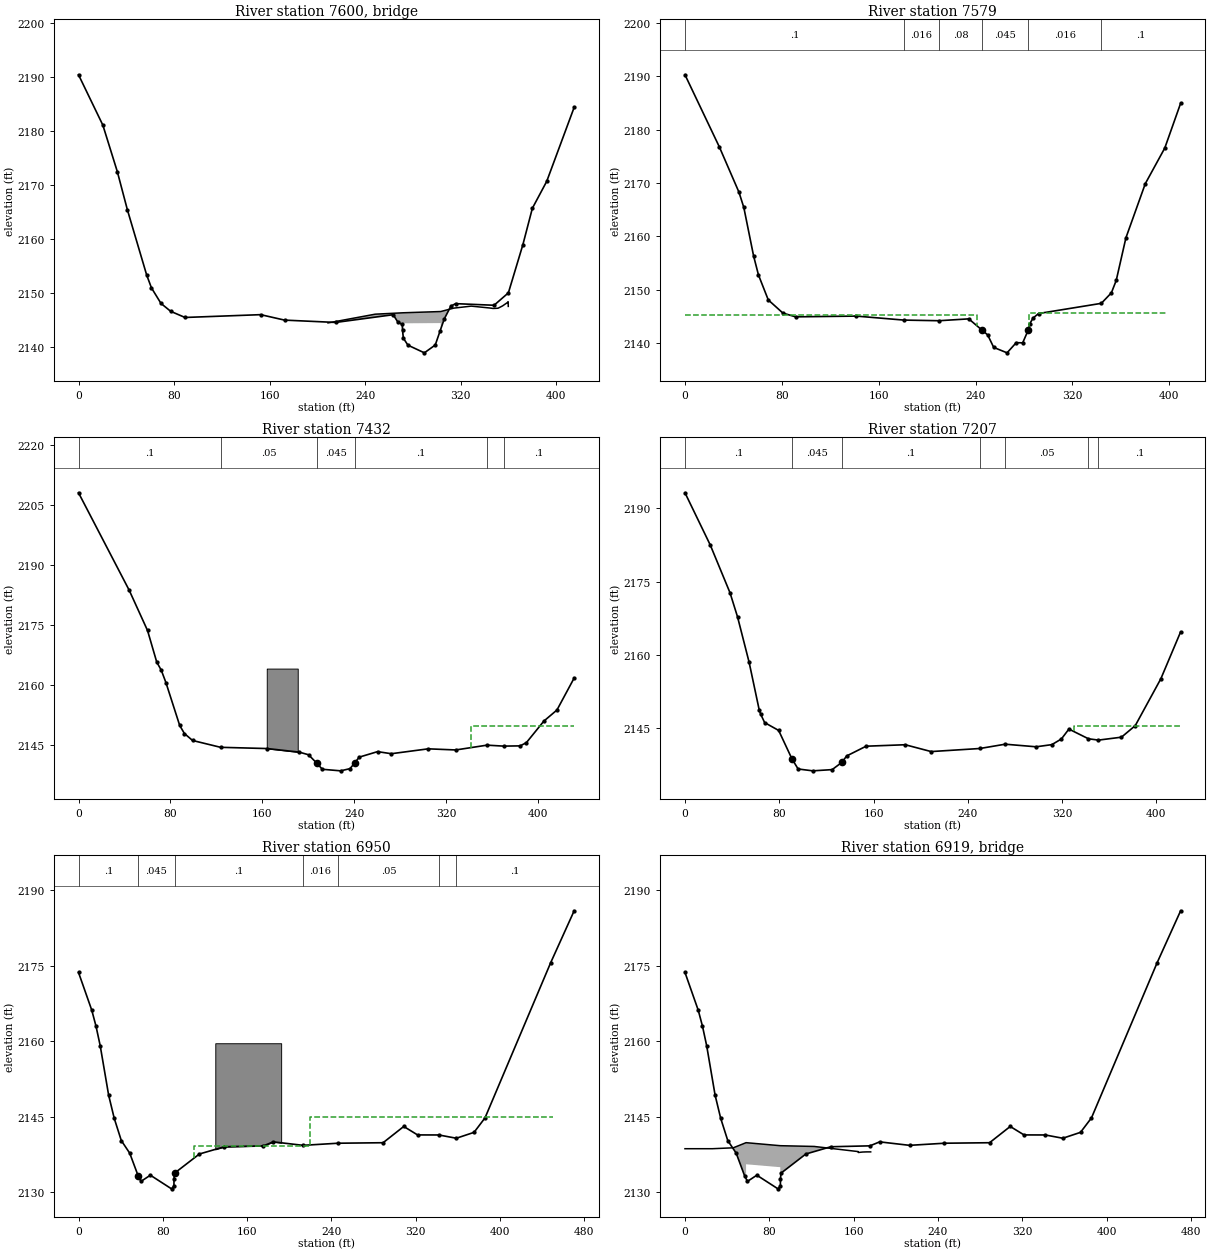
Type RM Length L Ch R = 3 ,7600    ,,,
BEGIN DESCRIPTION:
Unnamed Road
Survey ID: 54075STA040
Deck information taken from LIDAR
Opening information taken from Survey
END DESCRIPTION:
Bridge Culvert--1,0,-1,-1, 0
Deck Dist Width WeirC Skew NumUp NumDn MinLoCord MaxHiCord MaxSubmerge Is_Ogee
10,18,2.6,0, 20, 20, , , 0.98, 0, 0,0,,
     209  248.52   272.1  303.44  314.36  328.99   343.3   343.9   346.9   347.3
   350.5   351.3   351.7   355.1   355.3   355.6   358.8   359.3   359.9     360
 2144.44 2146.06 2146.32 2146.55 2147.18 2147.55 2147.23 2147.22 2147.13 2147.12
 2147.15 2147.16 2147.19 2147.58  2147.6 2147.65 2148.14 2148.22 2148.37  2147.5
                 2144.37 2144.41
                                                                                
     206   250.1  281.44   293.6  311.36  325.99   340.3   340.9   343.9   344.3
   347.5   348.3   348.7   352.1   352.3   352.6   355.8   356.3   356.9     357
 2144.44 2146.32 2146.55 2146.32 2147.18 2147.55 2147.23 2147.22 2147.13 2147.12
 2147.15 2147.16 2147.19 2147.58  2147.6 2147.65 2148.14 2148.22 2148.37  2147.5
         2144.37 2144.41
                                                                                
BR Coef=-1 ,-1 , 0 ,, 0 ,,,0.8,0,1.2,0,
WSPro=,,,, 1 ,,,, 0 ,,,, 0 ,,,,-1 ,-1 ,-1 , 0 , 0 , 0 , 0 , 0
BC Design=,, 0 ,, 0 ,,,,,,
BC Use User HTab Curves=0
BC User HTab FreeFlow(D)= 0

Type RM Length L Ch R = 1 ,7579    ,101.8,143.8,145
BEGIN DESCRIPTION:
Channel burned from survey STA038BD
END DESCRIPTION:
XS GIS Cut Line= 6
2204552.38301806421435.109950806 2204368.9382316421458.518621915
2204347.12706594421465.4981949242204316.59143403 421483.38335076
2204245.29122475421492.0675791782204151.07437183421496.701194895
#Sta/Elev= 30
       0  2190.3    28.4 2176.77    44.6 2168.28    48.6 2165.42    56.7 2156.31
    60.7 2152.77    68.8 2148.09    80.9 2145.62    91.4 2144.92   141.5 2145.06
   180.8 2144.31   209.8 2144.19   234.4 2144.54   245.2 2142.46  250.02 2141.53
     255 2139.19  266.04 2138.17  273.61 2140.08  278.94 2140.04  283.48 2142.42
   284.7 2143.59   287.5 2144.69   292.1 2145.54   343.9 2147.45   352.2 2149.42
   356.2 2151.74   364.2 2159.73   380.2 2169.88   396.3 2176.56   409.4 2184.96
#Mann= 6 ,-1,0
       0      .1       0   180.8    .016       0   209.8     .08       0
   245.2    .045       0  283.48    .016       0   343.9      .1       0
#XS Ineff= 2 ,-1
       0   241.1  2145.3     284   397.8  2145.6
Permanent Ineff=
       F       F
Bank Sta=245.2,283.48
XS Rating Curve= 0 ,0
Exp/Cntr(USF)=0,0
Exp/Cntr=0.5,0.3

Type RM Length L Ch R = 1 ,7432    ,239.3,225.7,174.8
XS GIS Cut Line= 2
2204556.19946171421359.2627972442204125.25413165 421336.38074432
#Sta/Elev= 30
       0 2208.05    44.1 2183.71    60.1 2173.63    68.1 2165.75    72.1 2163.68
    76.1 2160.62    88.1  2149.9    92.2 2147.88    99.3 2146.14   123.7 2144.43
   164.3 2144.12   192.3 2143.22   200.3 2142.57   207.4 2140.49   212.3 2138.94
   228.3 2138.55   236.4  2139.1   240.4 2140.48   244.4 2141.97   260.4 2143.35
   272.4 2142.83   304.5 2144.05   328.5 2143.77   355.7 2144.97   370.1 2144.73
   384.6 2144.79     390  2145.6   405.2 2150.98   416.6 2153.75   431.6 2161.75
#Mann= 6 ,-1,0
       0      .1       0   123.7     .05       0   207.4    .045       0
   240.4      .1       0   355.7    .016       0   370.1      .1       0
#XS Ineff= 2 , 0
                          342.13         2149.82
Permanent Ineff=
       F       F
#Block Obstruct= 1 ,-1
  163.91  190.89 2164.11
Bank Sta=207.4,240.4
XS Rating Curve= 0 ,0
Exp/Cntr(USF)=0,0
Exp/Cntr=0.3,0.1

Type RM Length L Ch R = 1 ,7207    ,290.2,256.3,168.4
XS GIS Cut Line= 3
2204453.23022355421096.1191886192204287.33533986 421138.06961898
2204108.09259195421311.591853652
#Sta/Elev= 30
       0 2193.19    21.5 2182.46    38.2  2172.7    44.6 2167.75    54.4 2158.47
      63 2148.67    64.3 2147.77    67.6 2146.08    79.5 2144.47    90.7 2138.68
      96 2136.57   108.4 2136.19   124.9 2136.44   133.1 2137.92   137.2 2139.24
   153.7 2141.24   186.9 2141.54   208.9 2140.14   250.3 2140.77   271.7 2141.65
     298 2141.12   311.3 2141.56   319.4 2142.72   325.8 2144.75   342.4 2142.76
   350.9 2142.49   370.4 2143.09   382.1 2145.46   403.8 2155.06   420.6 2164.68
#Mann= 7 ,-1,0
       0      .1       0    90.7    .045       0   133.1      .1       0
   250.3    .016       0   271.7     .05       0   342.4    .016       0
   350.9      .1       0
#XS Ineff= 2 , 0
                          329.86         2145.39
Permanent Ineff=
       F       F
Bank Sta=90.7,133.1
XS Rating Curve= 0 ,0
Exp/Cntr(USF)=0,0
Exp/Cntr=0.5,0.3

Type RM Length L Ch R = 1 ,6950    ,52.7,53.6,47.6
BEGIN DESCRIPTION:
Channel burned from survey STA032BU
END DESCRIPTION:
XS GIS Cut Line= 6
2204191.23237471420852.628610222  2204186.598759420942.211847419
2204185.05422042421051.8740860562204172.22404727421100.413063645
2204103.04530911421190.0952756272204043.87875813421279.843342549
#Sta/Elev= 30
       0 2173.67    12.6 2166.16    16.6    2163    20.6  2159.1    28.6 2149.28
    33.9 2144.69    40.6 2140.28    48.6 2137.77    56.6 2133.27    59.3 2132.17
   68.17  2133.4   88.25 2130.69   90.52 2131.25   90.62 2132.71    91.1  2133.8
   114.7 2137.61   138.4 2139.05   175.5 2139.23   184.7 2140.02   213.1 2139.33
   246.2 2139.75     289 2139.85   308.6 2143.08   321.7  2141.4   341.9 2141.39
   358.5 2140.74   375.3 2141.91   385.7 2144.78     448  2175.6   470.3 2185.92
#Mann= 7 ,-1,0
       0      .1       0    56.6    .045       0    91.1      .1       0
   213.1    .016       0   246.2     .05       0   341.9    .016       0
   358.5      .1       0
#XS Ineff= 3 ,-1
       0      37 2138.84     110     220 2139.11     220     450    2145
Permanent Ineff=
       F       F       F
#Block Obstruct= 1 ,-1
  129.78  192.28 2159.61
Bank Sta=56.6,91.1
XS Rating Curve= 0 ,0
Exp/Cntr(USF)=0,0
Exp/Cntr=0.5,0.3

Type RM Length L Ch R = 3 ,6919    ,,,
BEGIN DESCRIPTION:
Unnnamed Road
Survey ID:  54075STA030
Deck information taken from LIDAR
Opening information taken from Survey
END DESCRIPTION:
Bridge Culvert--1,0,-1,-1, 0
Deck Dist Width WeirC Skew NumUp NumDn MinLoCord MaxHiCord MaxSubmerge Is_Ogee
16.15011,20,2.6,0, 11, 11, , , 0.98, 0, 0,0,,
       0      26   45.81   57.96   90.44  122.62  164.36   164.5   168.5   172.4
   176.2
 2138.66 2138.66 2138.84 2139.86 2139.26 2139.11 2138.09 2137.91    2138 2138.03
 2138.03
                         2135.57 2134.99
        
       0      26   45.81   57.96   90.44  122.62  164.36   164.5   168.5   172.4
   176.2
 2138.66 2138.66 2138.84 2139.86 2139.26 2139.11 2138.09 2137.91    2138 2138.03
 2138.03
                         2135.57 2134.99
        
BR Coef=-1 ,-1 , 0 ,, 0 ,,,0.8,0,1.2,0,
WSPro=,,,, 1 ,,,, 0 ,,,, 0 ,,,,-1 ,-1 ,-1 , 0 , 0 , 0 , 0 , 0
BR U #Sta/Elev= 30
       0 2173.67    12.6 2166.16    16.6    2163    20.6  2159.1    28.6 2149.28
    33.9 2144.69    40.6 2140.28    48.6 2137.77    56.6 2133.27    59.3 2132.17
   68.17  2133.4   88.25 2130.69   90.52 2131.25   90.62 2132.71    91.1  2133.8
   114.7 2137.61   138.4 2139.05   175.5 2139.23   184.7 2140.02   213.1 2139.33
   246.2 2139.75     289 2139.85   308.6 2143.08   321.7  2141.4   341.9 2141.39
   358.5 2140.74   375.3 2141.91   385.7 2144.78     448  2175.6   470.3 2185.92
BR U #Mann= 7
       0      .1    56.6     .04    91.1      .1   213.1    .016   246.2     .05
   341.9    .016   358.5      .1
BR D #Sta/Elev= 30
       0 2156.95     6.3 2150.51    14.3 2140.43    18.3 2138.45    38.4 2137.87
    46.4 2134.03    50.2 2132.97   53.08 2132.79   63.33 2132.25   80.75 2130.09
    90.6 2132.67    94.6 2132.79    98.1 2133.49   106.6 2137.11   110.6 2137.69
   154.8 2137.32   166.8 2137.94   190.9 2138.28   207.3 2139.45   215.6 2139.18
   262.6 2139.47   288.1 2140.08   319.8 2139.94   350.7 2140.87   361.1 2141.67
   370.6  2145.2   390.5 2154.53   418.9  2168.7   451.1 2186.23   459.2 2191.07
BR D #Mann= 3
       0      .1   53.08     .04    90.6      .1
BC Design=,, 0 ,, 0 ,,,,,,
BC Use User HTab Curves=0
BC User HTab FreeFlow(D)= 0

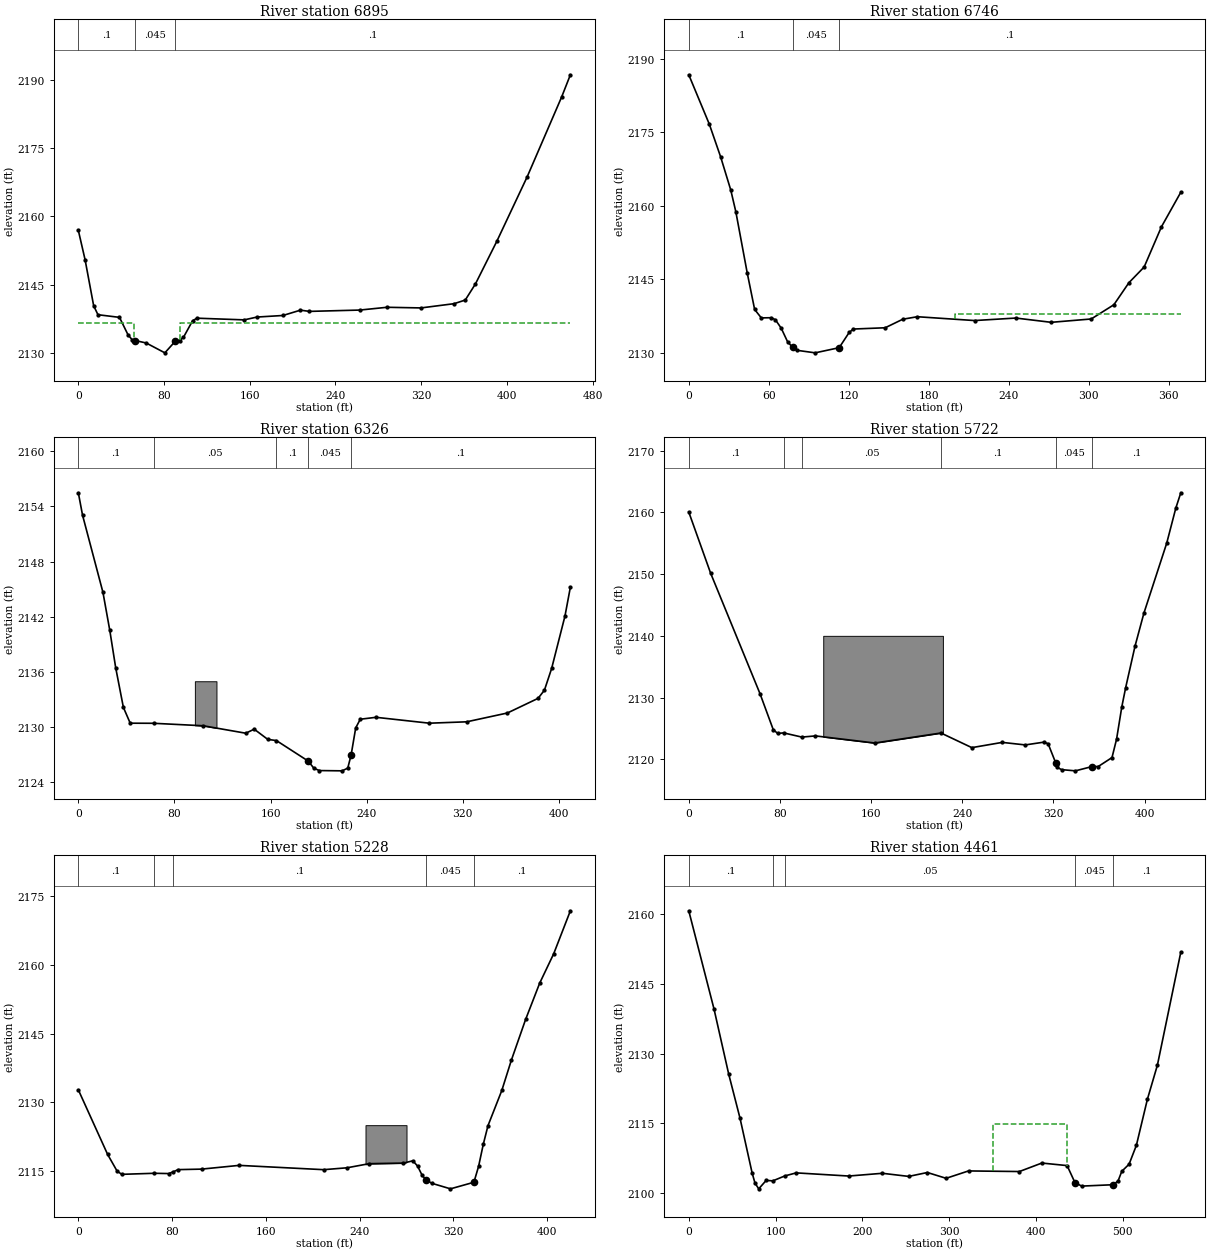
Type RM Length L Ch R = 1 ,6895    ,135.8,150.7,214.2
BEGIN DESCRIPTION:
Channel burned from survey STA028BD
END DESCRIPTION:
XS GIS Cut Line= 6
2204147.58303938  420830.93674772204143.44646736420874.816549782
2204149.52983326420953.0236174252204155.70798755421024.072391754
2204145.84483267421064.3520672642204003.01891579 421236.71920737
#Sta/Elev= 30
       0 2156.95     6.3 2150.51    14.3 2140.43    18.3 2138.45    38.4 2137.87
    46.4 2134.03    50.2 2132.97   53.08 2132.79   63.33 2132.25   80.75 2130.09
    90.6 2132.67    94.6 2132.79    98.1 2133.49   106.6 2137.11   110.6 2137.69
   154.8 2137.32   166.8 2137.94   190.9 2138.28   207.3 2139.45   215.6 2139.18
   262.6 2139.47   288.1 2140.08   319.8 2139.94   350.7 2140.87   361.1 2141.67
   370.6  2145.2   390.5 2154.53   418.9  2168.7   451.1 2186.23   459.2 2191.07
#Mann= 3 ,-1,0
       0      .1       0   53.08    .045       0    90.6      .1       0
#XS Ineff= 2 , 0
              52  2136.6      95          2136.6
Permanent Ineff=
       F       F
Bank Sta=53.08,90.6
XS Rating Curve= 0 ,0
Exp/Cntr(USF)=0,0
Exp/Cntr=0.5,0.3

Type RM Length L Ch R = 1 ,6746    ,417.6,419.8,427.6
XS GIS Cut Line= 2
   2204092.83789420728.0995040942203850.66949656421006.497814668
#Sta/Elev= 30
       0 2186.72    15.4 2176.66    23.9 2169.99    31.5 2163.23    35.3  2158.8
    43.8 2146.39    49.4 2138.89    54.4 2137.17      62 2137.21      65 2136.78
    69.3 2135.09    74.1 2132.31    77.8 2131.19      81 2130.57    94.8 2130.05
   112.8  2131.1   120.3 2134.21   123.4  2134.9   147.3 2135.16   160.5  2136.9
   171.4 2137.41   214.3 2136.63   245.3 2137.14   271.8 2136.27   301.8 2136.95
   318.8 2139.85   330.1 2144.35   341.5 2147.54   354.5 2155.75     369 2162.78
#Mann= 3 ,-1,0
       0      .1       0    77.8    .045       0   112.8      .1       0
#XS Ineff= 2 , 0
                             200            2138
Permanent Ineff=
       F       F
Bank Sta=77.8,112.8
XS Rating Curve= 0 ,0
Exp/Cntr(USF)=0,0
Exp/Cntr=0.3,0.1

Type RM Length L Ch R = 1 ,6326    ,507,604,614.3
XS GIS Cut Line= 3
2203863.28012115420383.2783398612203792.39492378420447.143424544
2203569.26583937420668.376656961
#Sta/Elev= 30
       0 2155.49     3.5 2153.06    20.5 2144.66    26.2 2140.52    31.1 2136.47
    37.5 2132.16    43.2 2130.44    62.6 2130.43     104 2130.16   139.4 2129.35
   146.4 2129.79   157.7 2128.68   164.9 2128.55   191.5 2126.31     196 2125.55
   200.6 2125.29   219.6 2125.26   224.3 2125.56   227.1    2127   230.9 2129.93
   234.7 2130.87   247.8 2131.08   292.2 2130.44   323.3 2130.59   357.2 2131.55
   382.7 2133.14     388 2134.03     394 2136.39   405.1 2142.09   409.6 2145.23
#Mann= 5 ,-1,0
       0      .1       0    62.6     .05       0   164.9      .1       0
   191.5    .045       0   227.1      .1       0
#Block Obstruct= 1 ,-1
      97     115    2135
Bank Sta=191.5,227.1
XS Rating Curve= 0 ,0
Exp/Cntr(USF)=0,0
Exp/Cntr=0.3,0.1

Type RM Length L Ch R = 1 ,5722    ,483.6,494.3,496.5
XS GIS Cut Line= 3
2203803.31585393420015.7530720332203404.36789822420029.168448096
2203371.79372468420030.610045285
#Sta/Elev= 30
       0 2160.06    19.2 2150.14    62.5 2130.63    74.1 2124.81      78 2124.18
    83.2 2124.27    99.2 2123.59   111.2 2123.78   163.2 2122.63   221.3 2124.25
   248.4 2121.88   275.1 2122.73   295.3 2122.32   311.3 2122.76   315.3 2122.53
   321.9 2119.46   323.3 2118.67   327.3 2118.31   339.3 2118.12   353.8 2118.81
   359.3 2118.82   371.4 2120.27   375.4 2123.25     380 2128.49   383.4 2131.62
   391.6 2138.33   399.4 2143.68   419.4 2155.01   427.4  2160.7431.7795 2163.18
#Mann= 6 ,-1,0
       0      .1       0    83.2    .016       0    99.2     .05       0
   221.3      .1       0   321.9    .045       0   353.8      .1       0
#Block Obstruct= 1 ,-1
     118     223    2140
Bank Sta=321.9,353.8
XS Rating Curve= 0 ,0
Exp/Cntr(USF)=0,0
Exp/Cntr=0.3,0.1

Type RM Length L Ch R = 1 ,5228    ,718.4,766.5,773.7
XS GIS Cut Line= 3
2203749.14420866419558.0863012242203684.62950963419554.390747509
2203330.00986615419534.140068914
#Sta/Elev= 30
       0 2132.72      25  2118.6      33 2114.99      37 2114.25    64.6 2114.48
    77.1 2114.42    81.1 2114.81    85.1 2115.28   105.1 2115.39   137.2 2116.21
   209.3 2115.27   229.2 2115.68   248.1 2116.58   277.4 2116.71   285.4 2117.21
   289.4 2116.07   293.4    2114   296.4 2113.12   301.5  2112.3   317.5 2111.08
   337.5 2112.52   341.5 2116.01   345.5 2120.82   349.5 2124.89   361.3 2132.59
   369.4 2139.17   381.6 2148.11   393.6 2156.04   405.6 2162.49   419.8 2171.87
#Mann= 5 ,-1,0
       0      .1       0    64.6    .016       0    81.1      .1       0
   296.4    .045       0   337.5      .1       0
#Block Obstruct= 1 ,-1
     245     280    2125
Bank Sta=296.4,337.5
XS Rating Curve= 0 ,0
Exp/Cntr(USF)=0,0
Exp/Cntr=0.3,0.1

Type RM Length L Ch R = 1 ,4461    ,547.9,653.5,666.7
XS GIS Cut Line= 6
2203987.46820857418947.0888908932203937.68677225 418928.71096424
2203692.40196384418828.8891114142203486.46348752418762.149790386
2203476.54251423418757.7902524532203455.74215153418751.573176008
#Sta/Elev= 30
       0 2160.78    29.1  2139.6    46.1 2125.51      59 2116.11      73 2104.27
    76.3 2102.09    80.6 2100.85    89.2 2102.67    96.8 2102.57   110.8 2103.64
   123.8 2104.29   184.3 2103.61   223.1  2104.2   253.4 2103.53   274.9 2104.37
   296.5 2103.12   322.3 2104.71   380.9 2104.58   406.8 2106.41   435.9 2105.86
   444.9 2102.21   452.7 2101.44   489.3 2101.74   494.7 2102.59   498.9 2104.63
   507.3 2106.16   515.7 2110.22   528.4 2120.16   539.9 2127.49   566.9 2151.87
#Mann= 5 ,-1,0
       0      .1       0    96.8    .016       0   110.8     .05       0
   444.9    .045       0   489.3      .1       0
#XS Ineff= 1 ,-1
  350.09   435.82114.854
Permanent Ineff=
       F
Bank Sta=444.9,489.3
XS Rating Curve= 0 ,0
Exp/Cntr(USF)=0,0
Exp/Cntr=0.3,0.1

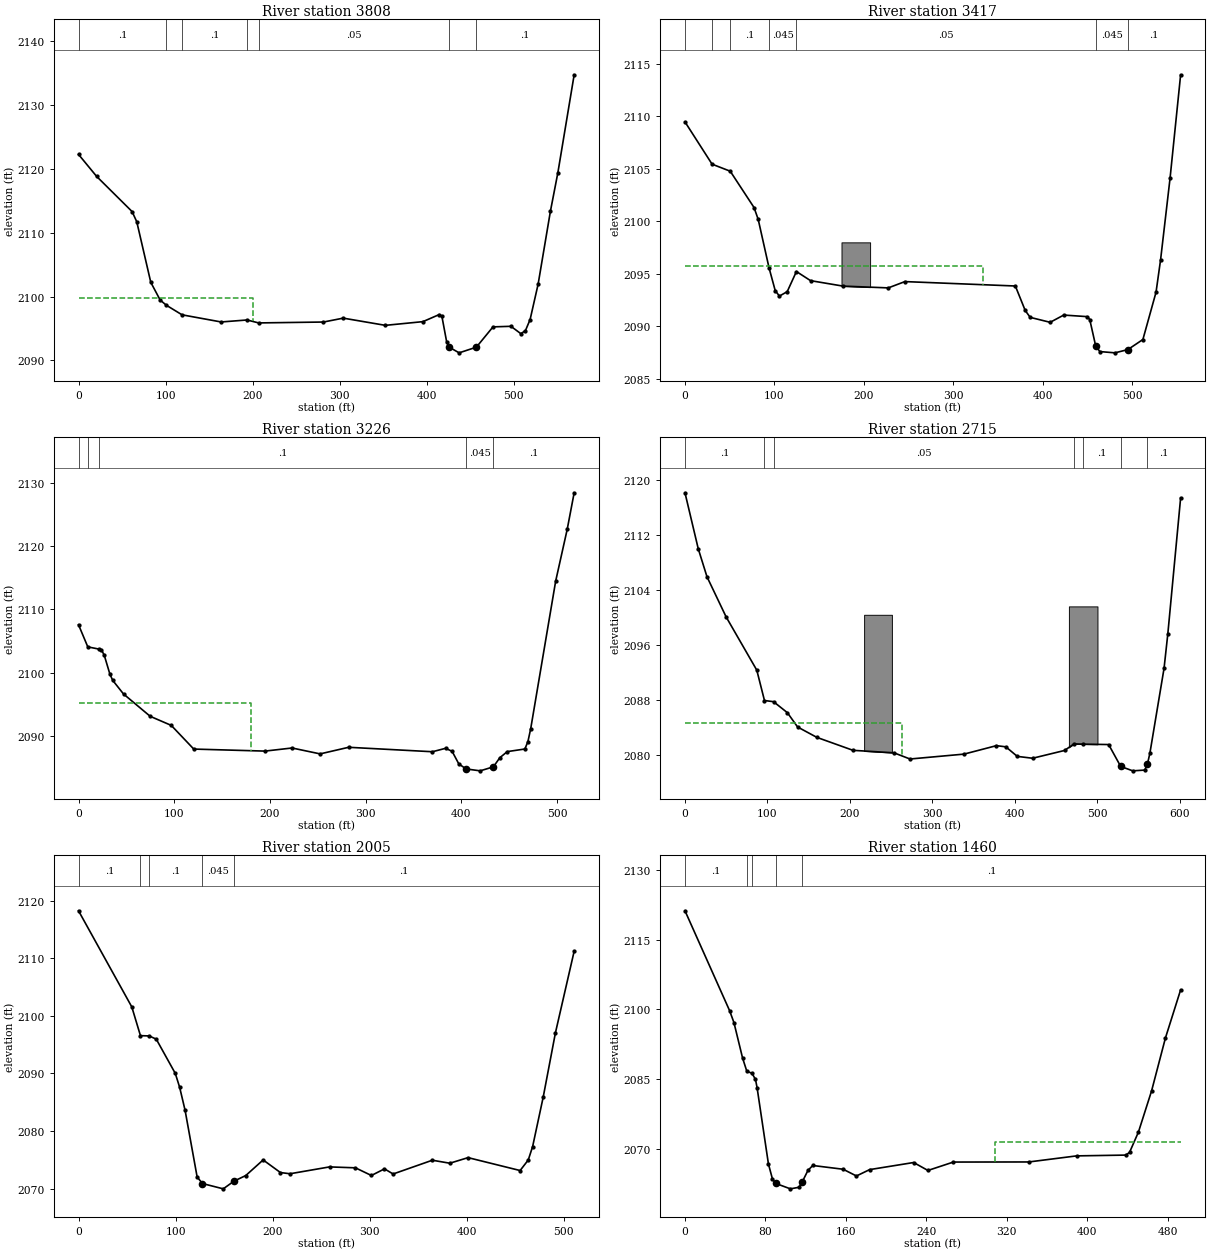
Type RM Length L Ch R = 1 ,3808    ,380.1,381.3,382.2
XS GIS Cut Line= 3
2204277.80875562 418596.858581512203940.93847299418292.876418016
2203854.07486107418216.798915425
#Sta/Elev= 30
       0  2122.3    20.8 2118.85    61.5 2113.34    66.9 2111.74      83 2102.24
    93.8 2099.46     101 2098.64   118.9 2097.15   163.8 2096.03   193.5 2096.34
   206.9 2095.88   281.3 2096.02     304 2096.63   352.4  2095.5   395.5 2096.08
   414.4  2097.2   417.3 2096.92   422.9 2092.82   425.8 2092.07   437.1 2091.19
   456.9 2092.08     476 2095.26   496.6 2095.35     508 2094.19   513.3 2094.69
   518.6 2096.41   527.8 2101.95   541.9 2113.37   550.5 2119.44   569.2 2134.78
#Mann= 7 ,-1,0
       0      .1       0     101    .016       0   118.9      .1       0
   193.5    .016       0   206.9     .05       0   425.8    .045       0
   456.9      .1       0
#XS Ineff= 2 , 0
             200 2099.86
Permanent Ineff=
       F       F
Bank Sta=425.8,456.9
XS Rating Curve= 0 ,0
Exp/Cntr(USF)=0,0
Exp/Cntr=0.3,0.1

Type RM Length L Ch R = 1 ,3417    ,224,200.9,195.1
XS GIS Cut Line= 6
2204473.29054526  418329.88885362204272.38311052418202.072938376
2204240.45939665418176.2884002482204244.33106244418155.518598375
2204284.04754444418098.9347858652204151.72482608417970.001968793
#Sta/Elev= 30
       0 2109.48    30.3 2105.45    50.6 2104.78    77.2 2101.32    81.9 2100.18
      94 2095.57   100.9  2093.4   105.6 2092.88   114.3  2093.3   124.6 2095.22
   140.4 2094.35   176.7 2093.83   227.3 2093.66   245.9 2094.26   369.4 2093.84
   380.4 2091.51     386 2090.85   408.3 2090.38   423.5 2091.07   449.8 2090.92
   452.6 2090.64  459.24 2088.12   463.9 2087.59   480.8 2087.47 495.187 2087.78
     512 2088.74   526.7 2093.25   531.8 2096.35   542.4 2104.13   554.2 2113.97
#Mann= 7 ,-1,0
       0      .1       0    30.3    .016       0    50.6      .1       0
      94    .045       0   124.6     .05       0  459.24    .045       0
 495.187      .1       0
#XS Ineff= 2 , 0
          332.67 2095.74
Permanent Ineff=
       F       F
#Block Obstruct= 1 ,-1
     175     207    2098
Bank Sta=459.24,495.187
XS Rating Curve= 0 ,0
Exp/Cntr(USF)=0,0
Exp/Cntr=0.3,0.1

Type RM Length L Ch R = 1 ,3226    ,509.9,510.5,512.1
XS GIS Cut Line= 4
2204684.53183905418069.6972910342204602.36614086418020.762722422
2204255.52542345417823.4968548382204235.55408764417811.757910499
#Sta/Elev= 30
       0  2107.6     9.7 2104.11    21.1 2103.77      24 2103.63    26.9 2102.79
    32.7 2099.86    35.7 2098.84      47 2096.69    74.9 2093.17    96.9 2091.74
   120.4 2088.01   194.8 2087.69   223.1 2088.18   252.4 2087.25   282.2 2088.29
   369.7 2087.59   383.5 2088.13   390.3 2087.65   397.3 2085.67   404.9 2084.88
   419.6 2084.58   433.4 2085.21   440.1 2086.64   447.9 2087.61   466.3 2088.02
   469.5  2089.2   472.4 2091.22   498.5 2114.49   510.5 2122.61   517.8 2128.39
#Mann= 5 ,-1,0
       0      .1       0     9.7    .016       0    21.1      .1       0
   404.9    .045       0   433.4      .1       0
#XS Ineff= 2 , 0
             180 2095.33
Permanent Ineff=
       F       F
Bank Sta=404.9,433.4
XS Rating Curve= 0 ,0
Exp/Cntr(USF)=0,0
Exp/Cntr=0.3,0.1

Type RM Length L Ch R = 1 ,2715    ,601.3,710,567.7
XS GIS Cut Line= 4
2205043.12006429417705.3913962642204672.40138006417486.207834875
2204550.00717039417401.0448375982204533.95545215417386.970599691
#Sta/Elev= 30
       0 2118.08    16.1 2109.94    26.7 2105.87    49.9 2100.04    87.1  2092.3
    96.4 2087.89   107.4 2087.72   124.2 2086.12   136.6 2084.04     160 2082.53
   203.8 2080.65   253.4 2080.29   272.9 2079.39   338.4  2080.1   377.7 2081.33
   389.1 2081.16     403 2079.77   421.6  2079.5   460.3 2080.63   471.8 2081.59
   483.3 2081.55   513.8 2081.49   528.4 2078.31     543 2077.67   557.6 2077.78
   560.9 2078.69   563.8 2080.22     581 2092.57   585.6 2097.62   601.1 2117.35
#Mann= 7 ,-1,0
       0      .1       0    96.4    .016       0   107.4     .05       0
   471.8    .016       0   483.3      .1       0   528.4    .045       0
   560.9      .1       0
#XS Ineff= 2 , 0
          263.37 2084.58
Permanent Ineff=
       F       F
#Block Obstruct= 2 ,-1
  217.25  250.93 2100.35  465.59  500.25 2101.57
Bank Sta=528.4,560.9
XS Rating Curve= 0 ,0
Exp/Cntr(USF)=0,0
Exp/Cntr=0.3,0.1

Type RM Length L Ch R = 1 ,2005    ,546.4,545.5,547
XS GIS Cut Line= 3
2205268.57357982417156.9269190482205237.87266018 417140.12531011
 2204813.9616256416924.430602097
#Sta/Elev= 30
       0 2118.26    54.9 2101.56    63.8 2096.57    72.8 2096.52    80.1 2095.96
    99.7 2090.01   104.2 2087.59   109.8 2083.59   122.2 2072.02   127.7 2070.88
   149.1 2069.96   160.1 2071.29   172.3 2072.27   190.2 2074.98     208 2072.79
   217.9 2072.58   258.6 2073.77   285.3 2073.61   301.7 2072.28   315.2 2073.43
   324.1 2072.54   364.5 2074.93   382.5 2074.41   401.3 2075.38   454.9 2073.14
   463.3 2074.97   467.8  2077.3   478.7 2085.89   491.3 2097.06   510.6 2111.24
#Mann= 5 ,-1,0
       0      .1       0    63.8    .016       0    72.8      .1       0
   127.7    .045       0   160.1      .1       0
Bank Sta=127.7,160.1
XS Rating Curve= 0 ,0
Exp/Cntr(USF)=0,0
Exp/Cntr=0.3,0.1

Type RM Length L Ch R = 1 ,1460    ,647.4,649.7,647.2
XS GIS Cut Line= 3
2205497.61296675416652.3820937752205416.07230591416621.028155759
2205045.80460274 416455.60162405
#Sta/Elev= 30
       0 2121.22    44.4 2099.69    48.7 2097.13    57.3 2089.48    61.5 2086.65
    66.6 2086.22    70.1  2084.9    71.7 2083.13      83 2066.67    86.9 2063.51
    90.2 2062.49   104.8 2061.32   113.5 2061.66   116.4 2062.72   122.3  2065.3
   127.1 2066.35   157.3 2065.54   170.5 2064.09   183.6 2065.46   227.4 2066.99
   241.6 2065.28   266.9 2067.09   341.9 2067.11   389.5 2068.42   438.4 2068.59
   442.1 2069.18   450.9 2073.53     464 2082.41   477.8 2093.83   492.9 2104.19
#Mann= 5 ,-1,0
       0      .1       0    61.5    .016       0    66.6      .1       0
    90.2    .045       0   116.4      .1       0
#XS Ineff= 2 , 0
                          308.09         2071.44
Permanent Ineff=
       F       F
Bank Sta=90.2,116.4
XS Rating Curve= 0 ,0
Exp/Cntr(USF)=0,0
Exp/Cntr=0.3,0.1

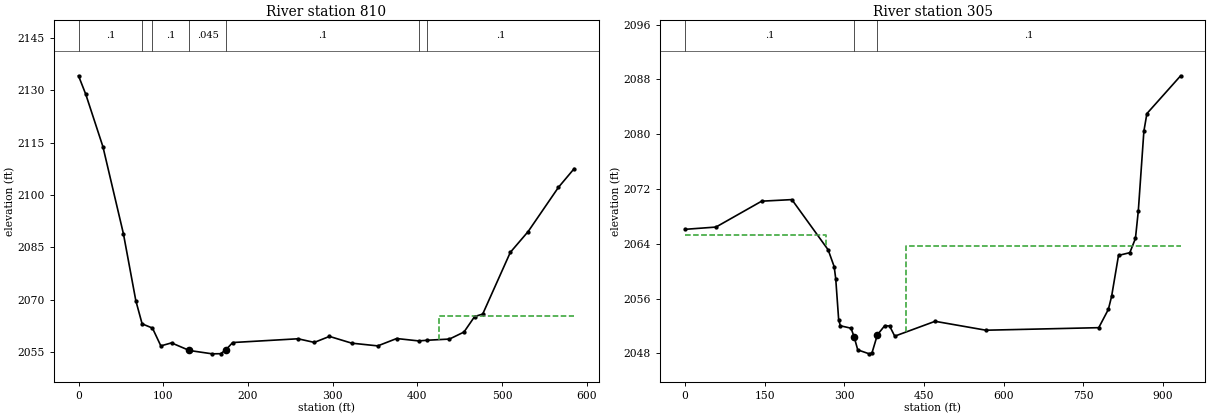
Type RM Length L Ch R = 1 ,810     ,501,505,523
XS GIS Cut Line= 4
2205743.88279897416067.9020763382205695.18547696  416044.2406056
2205251.14104656415835.8819778192205214.99956184415817.569745857
#Sta/Elev= 30
       0 2134.18     8.6 2128.85    28.8 2113.86      53  2088.9    67.7 2069.65
    75.1 2063.04    87.3 2061.83    97.2 2056.72   109.8 2057.58   130.9  2055.4
   157.9 2054.44   167.9 2054.48   174.3 2055.68     182 2057.68   259.1 2058.76
   278.4 2057.72   296.3 2059.44   322.6  2057.5   353.3 2056.72   375.6 2058.83
   401.5 2058.15     412 2058.34     438 2058.68   455.1 2060.69   467.7 2065.14
   477.2 2065.84   509.8 2083.54   530.9 2089.52   566.7 2102.21   585.2 2107.55
#Mann= 7 ,-1,0
       0      .1       0    75.1    .016       0    87.3      .1       0
   130.9    .045       0   174.3      .1       0   401.5    .016       0
     412      .1       0
#XS Ineff= 2 , 0
                          425.58         2065.25
Permanent Ineff=
       F       F
Bank Sta=130.9,174.3
XS Rating Curve= 0 ,0
Exp/Cntr(USF)=0,0
Exp/Cntr=0.5,0.3

Type RM Length L Ch R = 1 ,305     ,56.6,64.2,74.4
BEGIN DESCRIPTION:
Channel burned based on survey STA022BU
END DESCRIPTION:
XS GIS Cut Line= 6
2206141.45082289 415787.093657982205924.57916025415611.018771192
2205770.29902599415502.7119620542205578.64835019415312.312362496
2205558.73766569415286.8111699882205436.20762283415179.538477577
#Sta/Elev= 30
       0 2066.11    58.3 2066.44   144.4 2070.22   201.3 2070.45   269.6 2063.12
     281 2060.65   283.9 2058.89   289.4 2052.94   292.5 2052.03   312.7 2051.67
   318.5 2050.42  325.33 2048.51     347 2047.93  352.18 2048.07   362.3  2050.7
   376.2 2052.05   385.4 2051.99     395 2050.51     471 2052.68   566.7 2051.38
   779.2 2051.75   797.3 2054.42   803.4 2056.32   816.4  2062.3   837.7  2062.7
   848.3 2064.78   853.7  2068.8   864.2 2080.45   869.9 2083.01   933.4 2088.53
#Mann= 3 ,0,0
       0      .1       0   318.5    .045       0   362.3      .1       0
#XS Ineff= 2 , 0
             265 2065.23  416.52         2063.66
Permanent Ineff=
       F       F
Bank Sta=318.5,362.3
XS Rating Curve= 0 ,0
Exp/Cntr(USF)=0,0
Exp/Cntr=0.5,0.3