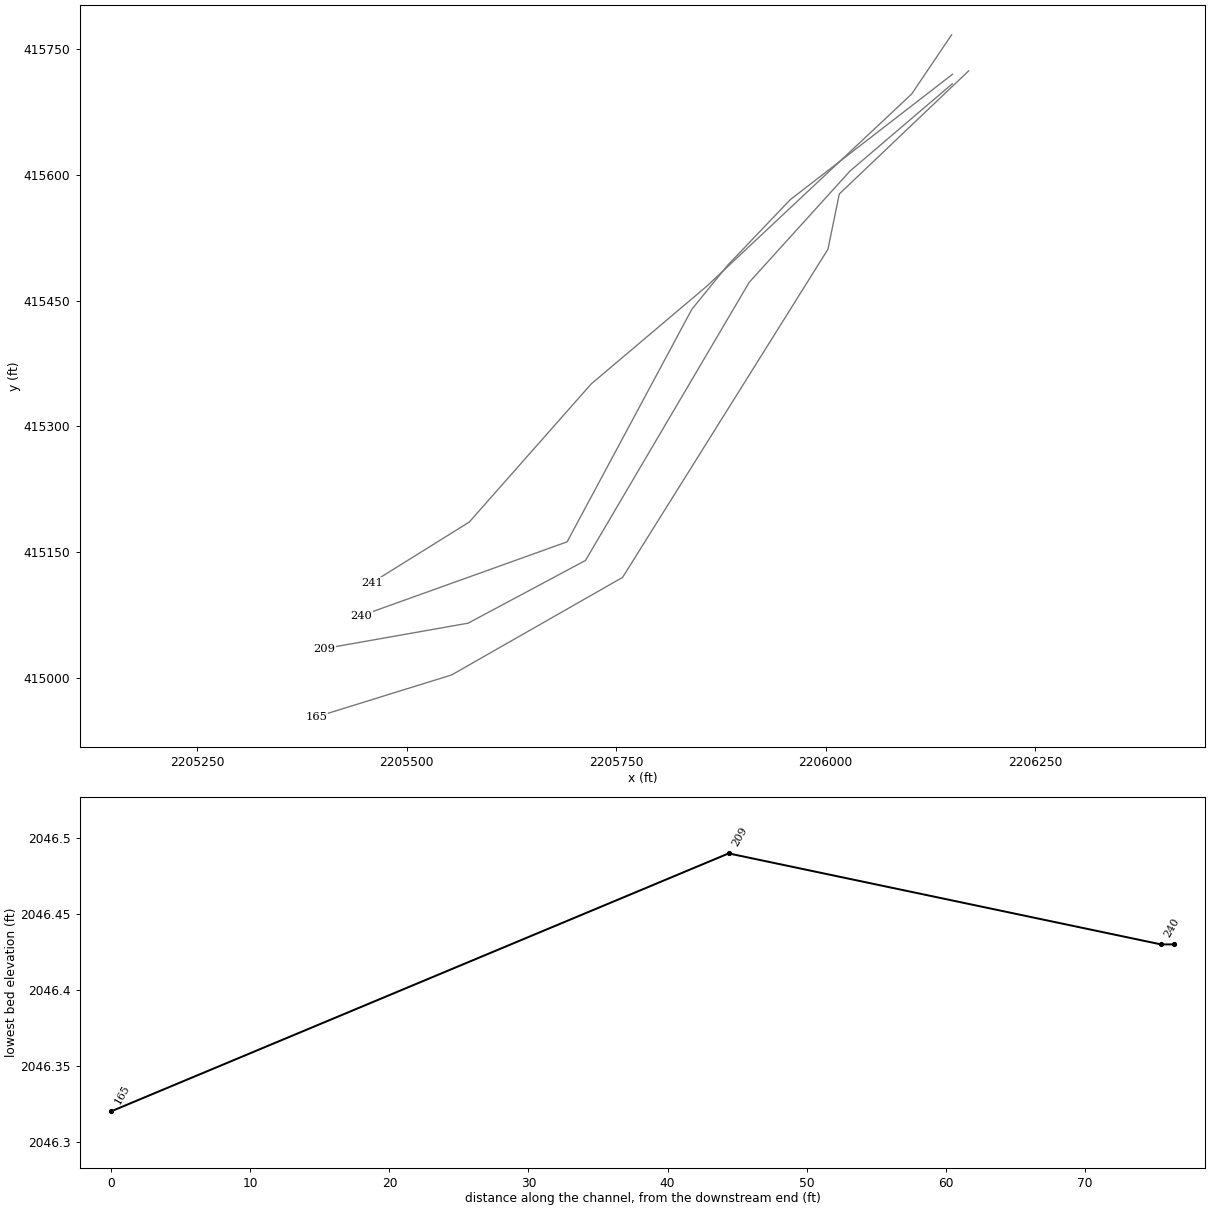
HEC-RAS study STMPNGCRK.prj: STMPNGCRK

--- STMPNGCRK.g01 (geometry) --- (continued)

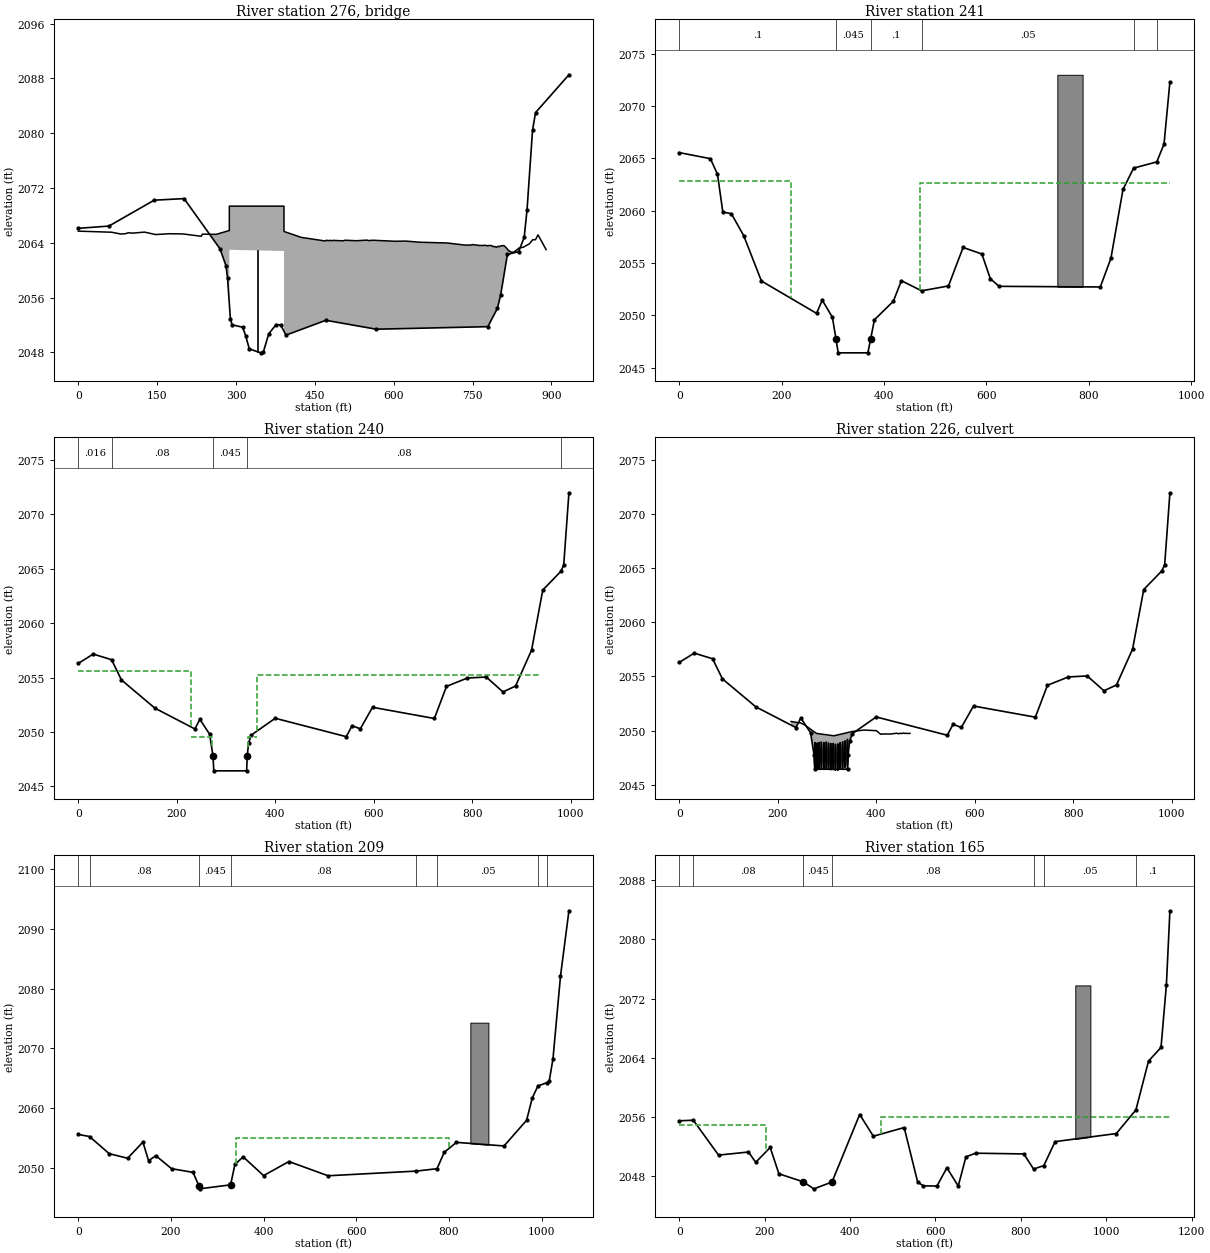
Type RM Length L Ch R = 3 ,276     ,,,
BEGIN DESCRIPTION:
Greenbrier River Trail
Survey ID:54075STA020
Included 3.7 ft railing
2-span bridge of width 6.6 ft
3-ft pier at the center of the structure, width assumed based on survey photos
END DESCRIPTION:
Bridge Culvert--1,0,-1,-1, 0
Deck Dist Width WeirC Skew NumUp NumDn MinLoCord MaxHiCord MaxSubmerge Is_Ogee
22,6.6,2.6,0, 60, 60, , , 0.98, 0, 0,0,,
       0    63.7    80.7    89.6    94.9   103.4   126.1     147   173.5   199.2
     234     236  262.27  287.38  287.38  391.36  391.36  424.12   469.9     472
   475.6     479   481.3   483.8   503.9   507.3   529.4   549.2     552   560.6
     603   622.5   650.6     702     736   747.3   749.5   764.3   775.5   778.5
   781.8     787   789.8   792.4   795.5   798.3   801.2   803.8   809.6   814.6
   818.2   824.6   829.6   838.2   846.8   858.2   864.6   869.7   874.6     890
  2065.7 2065.54 2065.28 2065.32 2065.46 2065.41 2065.56  2065.2 2065.32 2065.29
 2064.95 2065.26 2065.232065.789 2069.35 2069.35 2065.65 2064.79 2064.26 2064.38
  2064.3 2064.36 2064.29 2064.35 2064.29 2064.37  2064.3 2064.39 2064.32 2064.37
 2064.22 2064.25 2064.08 2063.97 2063.66 2063.67 2063.74  2063.6 2063.63 2063.54
 2063.61 2063.57 2063.42 2063.46 2063.34 2063.49 2063.43 2063.55 2063.59 2063.24
 2062.89  2062.6 2062.68 2063.22 2063.36 2063.85 2064.45 2064.44 2065.16    2063
                                                                                
                         2062.98 2062.98  2062.8  2062.8
                                                                                
                                                                                
                                                                                
                                                                                
       0    63.7    80.7    89.6    94.9   103.4   126.1     147   173.5   199.2
     234     236  262.27  287.38  287.38  391.36  391.36  424.12   469.9     472
   475.6     479   481.3   483.8   503.9   507.3   529.4   549.2     552   560.6
     603   622.5   650.6     702     736   747.3   749.5   764.3   775.5   778.5
   781.8     787   789.8   792.4   795.5   798.3   801.2   803.8   809.6   814.6
   818.2   824.6   829.6   838.2   846.8   858.2   864.6   869.7   874.6     890
  2065.7 2065.54 2065.28 2065.32 2065.46 2065.41 2065.56  2065.2 2065.32 2065.29
 2064.95 2065.26 2065.232065.789 2069.35 2069.35 2065.65 2064.79 2064.26 2064.38
  2064.3 2064.36 2064.29 2064.35 2064.29 2064.37  2064.3 2064.39 2064.32 2064.37
 2064.22 2064.25 2064.08 2063.97 2063.66 2063.67 2063.74  2063.6 2063.63 2063.54
 2063.61 2063.57 2063.42 2063.46 2063.34 2063.49 2063.43 2063.55 2063.59 2063.24
 2062.89  2062.6 2062.68 2063.22 2063.36 2063.85 2064.45 2064.44 2065.16    2063
                                                                                
                         2062.98 2062.98  2062.8  2062.8
                                                                                
                                                                                
                                                                                
                                                                                
Pier Skew, UpSta & Num, DnSta & Num=  ,340.48, 2 ,339.71, 2 , 0 , 0 , 0 ,,
       2       2
       0 2062.98
       2       2
       0 2062.98
BR Coef=-1 ,-1 , 0 ,1.25, 0 ,,,0.8,0,2,0,
WSPro=,,,, 1 ,,,, 0 ,,,, 0 ,,,,-1 ,-1 ,-1 , 0 , 0 , 0 , 0 , 0
BR U #Sta/Elev= 30
       0 2066.11    58.3 2066.44   144.4 2070.22   201.3 2070.45   269.6 2063.12
     281 2060.65   283.9 2058.89   289.4 2052.94   292.5 2052.03   312.7 2051.67
   318.5 2050.42  325.33 2048.51     347 2047.93  352.18 2048.07   362.3  2050.7
   376.2 2052.05   385.4 2051.99     395 2050.51     471 2052.68   566.7 2051.38
   779.2 2051.75   797.3 2054.42   803.4 2056.32   816.4  2062.3   837.7  2062.7
   848.3 2064.78   853.7  2068.8   864.2 2080.45   869.9 2083.01   933.4 2088.53
BR U #Mann= 3
       0      .1   318.5     .04   362.3      .1
BR D #Sta/Elev= 30
       0 2065.55   60.85 2064.97   74.67 2063.49   85.15 2059.87  101.76 2059.72
  125.99 2057.61  160.49 2053.29  268.19  2050.2  279.38 2051.46  299.18 2049.82
  306.192047.733   310.5 2046.43  368.44 2046.43     3742047.793  381.23 2049.59
  418.13 2051.35  433.92 2053.32  473.52 2052.35  525.86 2052.82  554.39 2056.49
  591.06 2055.87   607.6 2053.51  624.66 2052.78  822.42 2052.72  843.16 2055.46
  866.73 2062.03  887.47 2064.07   932.7 2064.66  946.84 2066.36  958.34  2072.3
BR D #Mann= 6
       0      .1  306.19     .04     374     .01  473.52     .05  887.47    .016
   932.7      .1
BC Design=,, 0 ,, 0 ,,,,,,
BC Use User HTab Curves=0
BC User HTab FreeFlow(D)= 0

Type RM Length L Ch R = 1 ,241     ,1,0.9,0.8
BEGIN DESCRIPTION:
survey STA018BD
channel burned per survey information
c/e of 0.6/0.8 used to prevent profile crossings
END DESCRIPTION:
XS GIS Cut Line= 6
2206150.20835659415767.0764380832206102.58005066415696.491811696
2205857.93061018415466.9918098922205720.30185571415350.638998146
2205574.69462273415185.7504420712205458.41348214415113.321383793
#Sta/Elev= 30
       0 2065.55   60.85 2064.97   74.67 2063.49   85.15 2059.87  101.76 2059.72
  125.99 2057.61  160.49 2053.29  268.19  2050.2  279.38 2051.46  299.18 2049.82
  306.192047.733   310.5 2046.43  368.44 2046.43     3742047.793  381.23 2049.59
  418.13 2051.35  433.92 2053.32  473.52 2052.35  525.86 2052.82  554.39 2056.49
  591.06 2055.87   607.6 2053.51  624.66 2052.78  822.42 2052.72  843.16 2055.46
  866.73 2062.03  887.47 2064.07   932.7 2064.66  946.84 2066.36  958.34  2072.3
#Mann= 6 ,-1,0
       0      .1       0  306.19    .045       0     374      .1       0
  473.52     .05       0  887.47    .016       0   932.7      .1       0
#XS Ineff= 2 , 0
          217.61 2062.81   470.1         2062.69
Permanent Ineff=
       F       F
#Block Obstruct= 1 ,-1
  738.47  787.79 2072.98
Bank Sta=306.19,374
XS Rating Curve= 0 ,0
Exp/Cntr(USF)=0,0
Exp/Cntr=0.7,0.5

Type RM Length L Ch R = 1 ,240     ,29.1,31.1,32.4
BEGIN DESCRIPTION:
xs 3
END DESCRIPTION:
XS GIS Cut Line= 6
2206151.23021739415719.9899870812205957.66813051415570.352006164
 2205883.2956775415492.4509331232205840.28237005415439.620212971
2205691.47190614415162.1769751732205446.18686182415074.214857735
#Sta/Elev= 30
       0  2056.3    30.4 2057.16    67.7 2056.64    87.7 2054.78   155.6 2052.19
   236.8 2050.28   246.9 2051.16   266.7  2049.8   273.62047.789   275.2 2046.43
  341.86 2046.43   343.12047.789   345.9 2049.02   351.5 2049.72   399.9 2051.26
   544.2 2049.57     556 2050.58   572.7 2050.29   597.5 2052.27   723.1 2051.24
   747.7 2054.19   790.2 2054.96   828.4 2055.05   862.4 2053.68   887.9 2054.22
   920.5 2057.53   943.2 2063.04   979.9 2064.76   985.7 2065.33   996.3 2071.98
#Mann= 5 ,-1,0
       0    .016       0    67.7     .08       0   273.6    .045       0
   343.1     .08       0   979.9      .1       0
#XS Ineff= 4 ,-1
       0  229.072055.633  229.07     271 2049.52     345     363 2049.52
     363  936.34 2055.21
Permanent Ineff=
       F       F       F       F
Bank Sta=273.6,343.1
XS Rating Curve= 0 ,0
Exp/Cntr(USF)=0,0
Exp/Cntr=0.5,0.3

Type RM Length L Ch R = 2 ,226     ,,,
BEGIN DESCRIPTION:
Seebert Road
Survey ID: 54075STA010
15 circular pipes of concrete fill
Width and rise of each pipe is 2.50 ft
Headwall Straight Inlet Type
END DESCRIPTION:
Bridge Culvert--1,0,-1,-1, 0
Deck Dist Width WeirC Skew NumUp NumDn MinLoCord MaxHiCord MaxSubmerge Is_Ogee
2,14,2.6,0, 30, 51, , , 0.98, 0, 0,0,,
     227   246.9  254.95  278.67  313.94  350.68  374.94  400.53   408.6   409.4
   413.1   414.3   415.8   428.3   442.1   442.8   445.7   447.3   448.4   451.4
   455.3   456.7   457.1   458.5   459.9   461.6   462.8   465.6   467.7   468.4
 2050.84  2050.7 2050.51 2049.74 2049.52 2049.91 2050.05 2049.99 2049.66 2049.67
 2049.68 2049.68 2049.69 2049.68 2049.76 2049.73 2049.71 2049.73 2049.75 2049.73
 2049.77 2049.75 2049.74 2049.75 2049.74 2049.75 2049.74 2049.73 2049.74 2049.75
                                                                                
                                                                                
                                                                                
   132.6   142.8   152.5   153.4   157.3   158.1   160.9   163.8     170   183.6
   186.1   186.4   186.7   189.2   197.7   200.6   201.8   202.8   203.4   208.3
   209.1   209.8     212  236.95  260.67  295.94  332.68  356.94  382.53   390.6
   391.4   395.1   396.3   397.8   410.3   424.1   424.8   427.7   429.3   430.4
   433.4   437.3   438.7   439.1   440.5   441.9   443.6   444.8   447.6   449.7
   450.4
 2053.44 2053.04 2052.75  2052.7 2052.57 2052.56 2052.44  2052.4 2052.14  2051.7
 2051.57 2051.57 2051.55 2051.51 2051.24 2051.18 2051.13 2051.09 2051.07  2051.1
 2051.09 2051.08 2051.07 2050.51 2049.74 2049.52 2049.91 2050.05 2049.99 2049.66
 2049.67 2049.68 2049.68 2049.69 2049.68 2049.76 2049.73 2049.71 2049.73 2049.75
 2049.73 2049.77 2049.75 2049.74 2049.75 2049.74 2049.75 2049.74 2049.73 2049.74
 2049.75
                                                                                
                                                                                
                                                                                
                                                                                
                                                                                
        
BR Coef=-1 ,-1 , 0 ,, 0 ,,,0.8,0,1.2,0,
WSPro=,,,, 1 ,,,, 0 ,,,, 0 ,,,,-1 ,-1 ,-1 , 0 , 0 , 0 , 0 , 0
Culvert=1,2.5,2.5,14,0.019,0.5,1,2,1,2046.43,275.7,2046.49,261.7,Culvert #1  , 0 ,2
   275.7   261.7
BC Culvert Barrel=1,Barrel1,0
Culvert Bottom n=0.019
Culvert=1,2.5,2.5,14,0.019,0.5,1,2,1,2046.38,279.92,2046.4,265.77,Culvert #2  , 0 ,2
  279.92  265.77
BC Culvert Barrel=1,Barrel2,0
Culvert Bottom n=0.019
Culvert=1,2.5,2.5,14,0.019,0.5,1,2,1,2046.44,283.79,2046.33,270.35,Culvert #3  , 0 ,2
  283.79  270.35
BC Culvert Barrel=1,Barrel3,0
Culvert Bottom n=0.019
Culvert=1,2.5,2.5,14,0.019,0.5,1,2,1,2046.47,288.47,2046.3,275.29,Culvert #4  , 0 ,2
  288.47  275.29
BC Culvert Barrel=1,Barrel4,0
Culvert Bottom n=0.019
Culvert=1,2.5,2.5,14,0.019,0.5,1,2,1,2046.43,293.56,2046.29,280.26,Culvert #5  , 0 ,2
  293.56  280.26
BC Culvert Barrel=1,Barrel4,0
Culvert Bottom n=0.019
Culvert=1,2.5,2.5,14,0.019,0.5,1,2,1,2046.48,298.54,2046.29,285.09,Culvert #6  , 0 ,2
  298.54  285.09
BC Culvert Barrel=1,Barrel4,0
Culvert Bottom n=0.019
Culvert=1,2.5,2.5,14,0.019,0.5,1,2,1,2046.39,303.15,2046.28,289.87,Culvert #7  , 0 ,2
  303.15  289.87
BC Culvert Barrel=1,Barrel7,0
Culvert Bottom n=0.019
Culvert=1,2.5,2.5,14,0.019,0.5,1,2,1,2046.34,307.75,2046.18,294.46,Culvert #8  , 0 ,2
  307.75  294.46
BC Culvert Barrel=1,Barrel8,0
Culvert Bottom n=0.019
Culvert=1,2.5,2.5,14,0.019,0.5,1,2,1,2046.35,312.65,2046.13,299.51,Culvert #9  , 0 ,2
  312.65  299.51
BC Culvert Barrel=1,Barrel9,0
Culvert Bottom n=0.019
Culvert=1,2.5,2.5,14,0.019,0.5,1,2,1,2046.28,317.2,2046.1,304.35,Culvert #10 , 0 ,2
   317.2  304.35
BC Culvert Barrel=1,Barrel10,0
Culvert Bottom n=0.019
Culvert=1,2.5,2.5,14,0.019,0.5,1,2,1,2046.3,322.18,2046.16,309.04,Culvert #11 , 0 ,2
  322.18  309.04
BC Culvert Barrel=1,Barrel11,0
Culvert Bottom n=0.019
Culvert=1,2.5,2.5,14,0.019,0.5,1,2,1,2046.42,326.85,2046.18,313.93,Culvert #12 , 0 ,2
  326.85  313.93
BC Culvert Barrel=1,Barrel12,0
Culvert Bottom n=0.019
Culvert=1,2.5,2.5,14,0.019,0.5,1,2,1,2046.49,331.8,2046.26,318.74,Culvert #13 , 0 ,2
   331.8  318.74
BC Culvert Barrel=1,Barrel13,0
Culvert Bottom n=0.019
Culvert=1,2.5,2.5,14,0.019,0.5,1,2,1,2046.58,336.54,2046.4,323.6,Culvert #14 , 0 ,2
  336.54   323.6
BC Culvert Barrel=1,Barrel14,0
Culvert Bottom n=0.019
Culvert=1,2.5,2.5,14,0.019,0.5,1,2,1,2046.73,341.41,2046.47,327.4,Culvert #15 , 0 ,2
  341.41   327.4
BC Culvert Barrel=1,Barrel15,0
Culvert Bottom n=0.019
BR U #Sta/Elev= 30
       0  2056.3    30.4 2057.16    67.7 2056.64    87.7 2054.78   155.6 2052.19
   236.8 2050.28   246.9 2051.16   266.7  2049.8   273.62047.789   275.2 2046.43
  341.86 2046.43   343.12047.789   345.9 2049.02   351.5 2049.72   399.9 2051.26
   544.2 2049.57     556 2050.58   572.7 2050.29   597.5 2052.27   723.1 2051.24
   747.7 2054.19   790.2 2054.96   828.4 2055.05   862.4 2053.68   887.9 2054.22
   920.5 2057.53   943.2 2063.04   979.9 2064.76   985.7 2065.33   996.3 2071.98
BR U #Mann= 5
       0    .016    67.7     .08   273.6     .04   343.1     .08   979.9      .1
BR D #Sta/Elev= 30
       0  2055.6    24.3 2055.25    66.7 2052.38   106.5 2051.61   139.5 2054.32
   151.7  2051.2   167.4 2052.04   201.4 2049.86   247.7 2049.25  260.36 2046.98
   261.7 2046.49  328.712047.159     338 2050.57   355.8 2051.84   399.9 2048.71
   454.5 2051.06     539 2048.68   729.2 2049.46   774.1 2049.86   789.6  2052.6
   815.9 2054.27   918.7 2053.67   967.4 2057.97   979.6 2061.71   991.8 2063.71
  1012.1 2064.29  1016.2 2064.54  1024.3 2068.26  1040.5  2082.1  1058.7 2093.04
BR D #Mann= 8
       0    .016    24.3     .08  260.36     .04  328.71     .08   729.2    .016
   774.1     .05   991.8    .016  1012.1      .1
BC Design=,, 0 ,, 0 ,,,,,,
BC Use User HTab Curves=0
BC User HTab FreeFlow(D)= 0

Type RM Length L Ch R = 1 ,209     ,35.8,44.4,44.1
BEGIN DESCRIPTION:
xs2
END DESCRIPTION:
XS GIS Cut Line= 6
2206151.01197768415708.6320205672206028.85396096415604.436526413
2205908.75064158415471.8224445912205713.37680091415139.951649907
2205573.35450289415065.1534137842205402.25191454415034.903541138
#Sta/Elev= 30
       0  2055.6    24.3 2055.25    66.7 2052.38   106.5 2051.61   139.5 2054.32
   151.7  2051.2   167.4 2052.04   201.4 2049.86   247.7 2049.25  260.36 2046.98
   261.7 2046.49  328.712047.159     338 2050.57   355.8 2051.84   399.9 2048.71
   454.5 2051.06     539 2048.68   729.2 2049.46   774.1 2049.86   789.6  2052.6
   815.9 2054.27   918.7 2053.67   967.4 2057.97   979.6 2061.71   991.8 2063.71
  1012.1 2064.29  1016.2 2064.54  1024.3 2068.26  1040.5  2082.1  1058.7 2093.04
#Mann= 8 ,-1,0
       0    .016       0    24.3     .08       0  260.36    .045       0
  328.71     .08       0   729.2    .016       0   774.1     .05       0
   991.8    .016       0  1012.1      .1       0
#XS Ineff= 3 ,-1
       0     254    2048  338.13     3402047.854     340  799.18    2055
Permanent Ineff=
       F       F       F
#Block Obstruct= 1 ,-1
  845.97  884.97 2074.31
Bank Sta=260.36,328.71
XS Rating Curve= 0 ,0
Exp/Cntr(USF)=0,0
Exp/Cntr=0.5,0.3

Type RM Length L Ch R = 1 ,165     ,,,
XS GIS Cut Line= 6
2206170.49488287415724.023360656 2206016.2099703415577.214962229
2206002.67384492415511.2933755442205757.63972248415119.753534987
2205553.71429476 415003.403444332205392.32545934414953.360394586
#Sta/Elev= 30
       0  2055.5    32.9 2055.58    92.1 2050.87   162.1 2051.29   179.1  2049.9
     213  2051.9   233.4 2048.35  289.81 2047.28   315.3 2046.32   357.7 2047.24
   422.5 2056.35   454.5 2053.42   526.7 2054.59   558.3 2047.22   571.9 2046.72
   603.5  2046.7   626.7 2049.16   653.3  2046.7   671.3 2050.64   693.9 2051.13
   806.9 2051.03   829.7 2048.99   853.7 2049.46   880.1 2052.69  1023.4 2053.78
  1069.3 2056.97  1098.8 2063.55  1128.1  2065.4  1140.7 2073.87  1148.9 2083.84
#Mann= 7 ,-1,0
       0    .016       0    32.9     .08       0  289.81    .045       0
   357.7     .08       0   829.7    .016       0   853.7     .05       0
  1069.3      .1       0
#XS Ineff= 2 , 0
          203.32    2055  472.43         2055.98
Permanent Ineff=
       F       F
#Block Obstruct= 1 ,-1
  927.33   962.7 2073.77
Bank Sta=289.81,357.7
XS Rating Curve= 0 ,0
Exp/Cntr(USF)=0,0
Exp/Cntr=0.3,0.1
LCMann Table=0

Chan Stop Cuts=-1
Use User Specified Reach Order=0
Composite Channel Slope=5